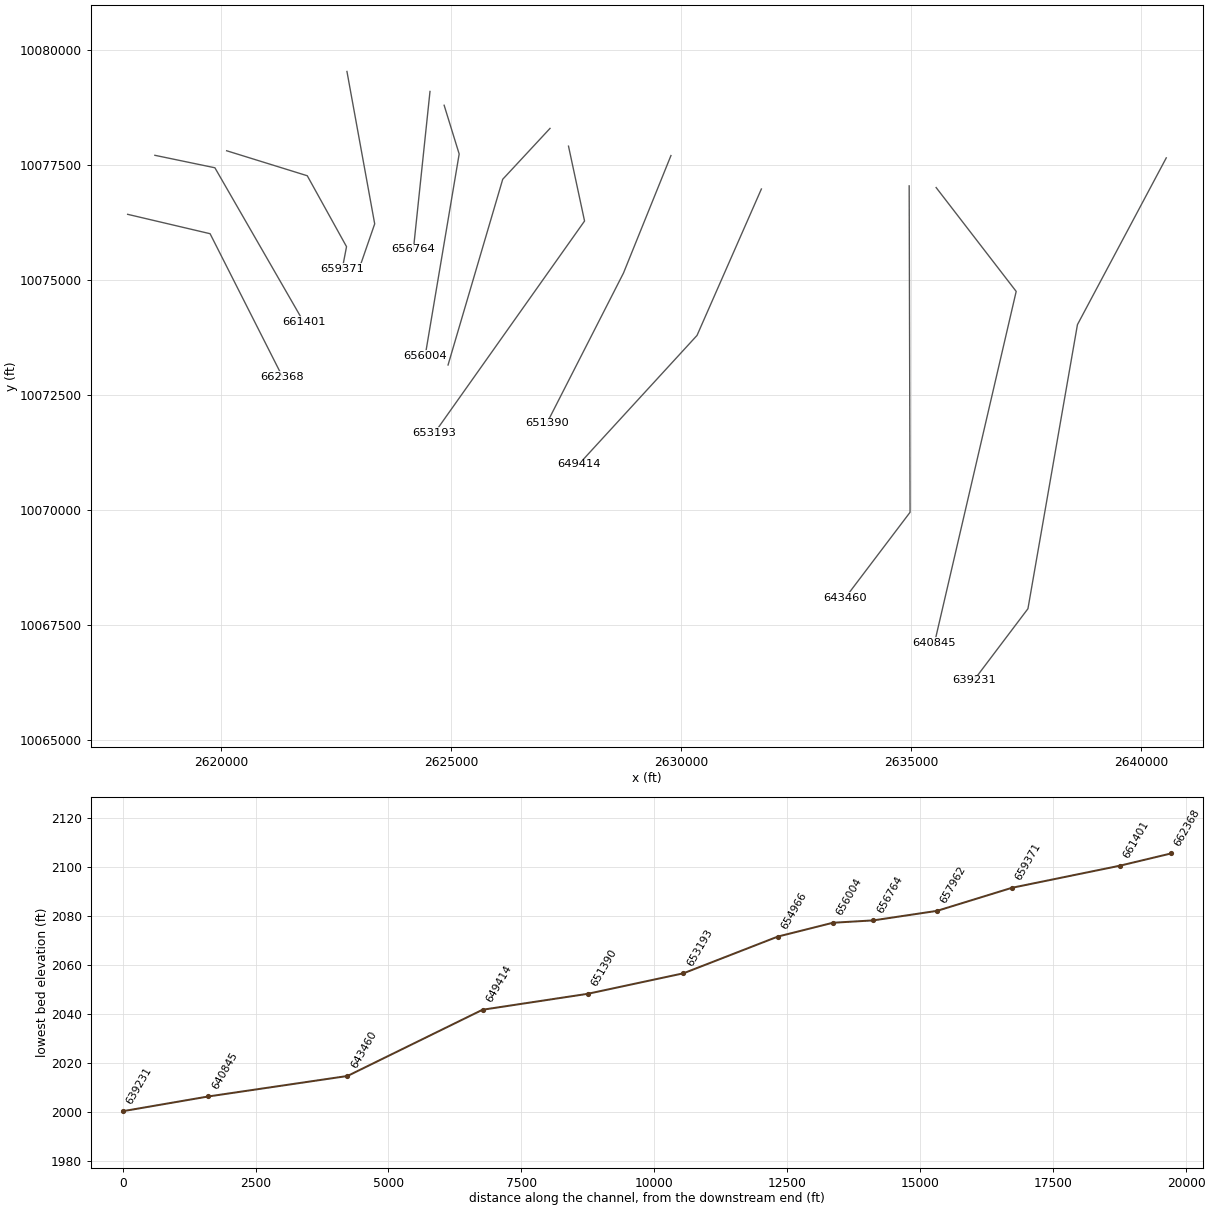
HEC-RAS study PEDERNALES RIVER.prj: PEDERNALES RIVER Base Level Engineering

--- PEDERNALES RIVER.g02 (geometry) --- (continued)

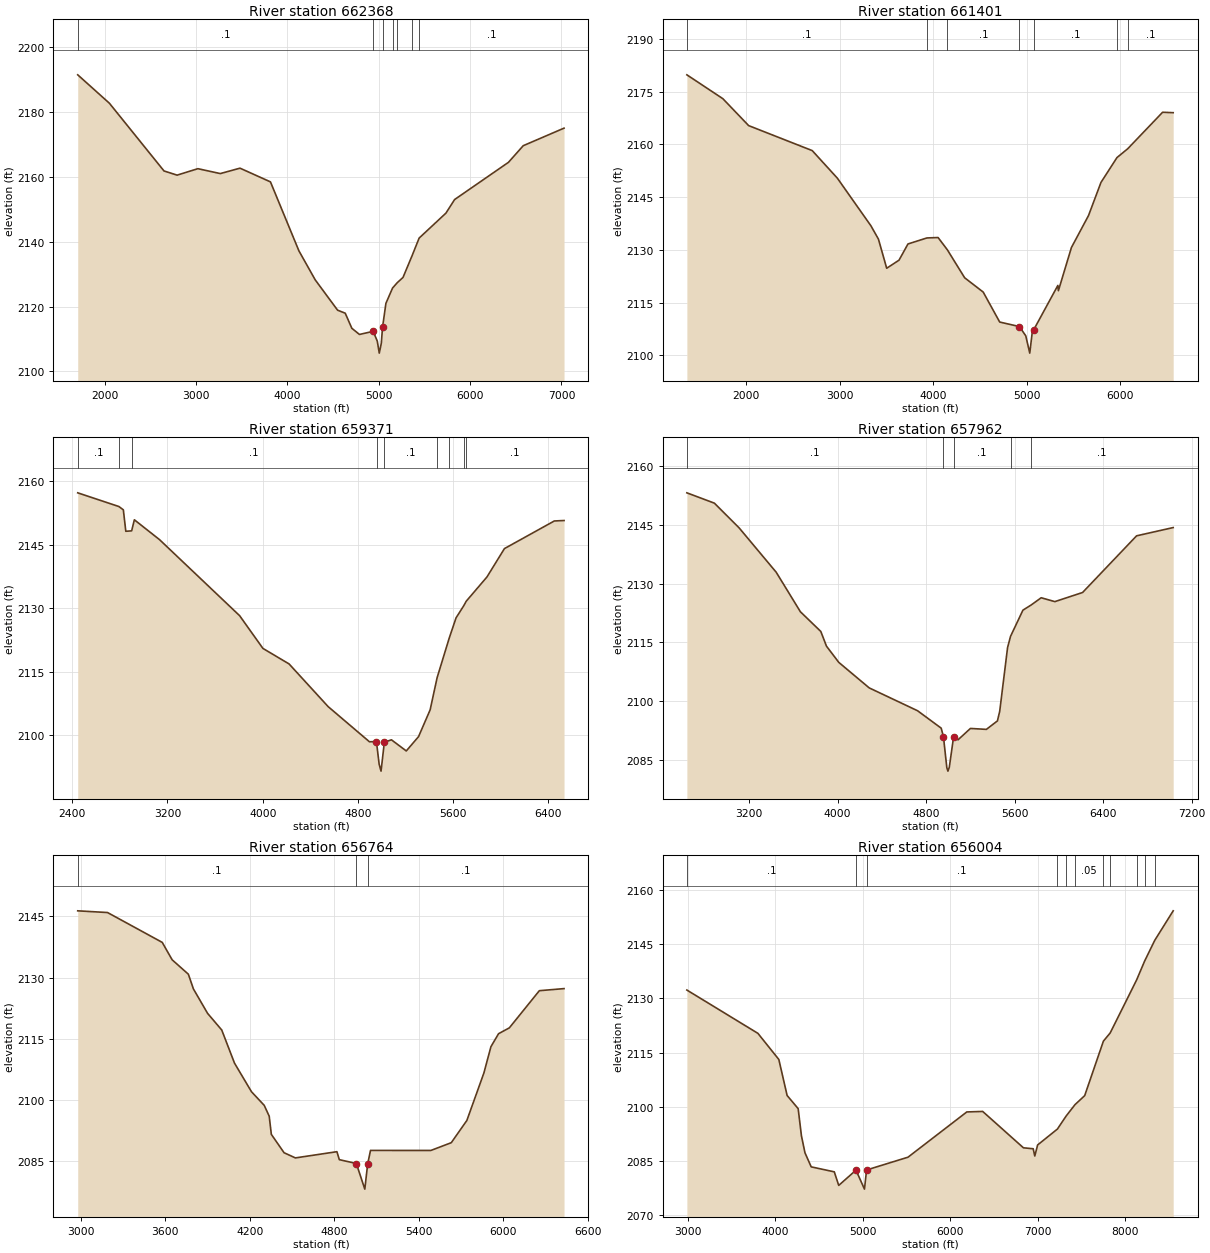
Type RM Length L Ch R = 1 ,662368  ,967,967,967
BEGIN DESCRIPTION:
PEDERNALES RIVER 15.0
END DESCRIPTION:
XS GIS Cut Line= 3
      2617958.97     10076428.75      2619752.17     10076007.29
      2621325.49     10072900.85
#Sta/Elev= 30
  1703.9 2191.45  2050.6 2182.69  2648.4 2161.81  2791.9 2160.52  3019.3 2162.51
  3264.8    2161  3480.5 2162.67  3813.9 2158.44  4125.7 2137.16    4304 2128.23
    4549 2118.88  4632.5 2117.95  4704.9  2113.3  4788.4  2111.4  4938.7 2112.36
  4983.3 2109.35  5005.3 2105.64  5027.8 2108.72  5040.8 2113.59    5078    2121
  5150.9 2125.72  5202.5 2127.37    5265 2128.98  5366.1 2135.79  5441.8 2141.12
  5735.1 2148.81  5829.8 2152.99  6419.6 2164.47  6581.5  2169.6  7028.1 2175.01
#Mann= 7 ,-1 , 0
  1703.9      .1       0  4938.7     .07       0  5040.8      .1       0
  5150.9     .05       0  5202.5     .08       0  5366.1     .05       0
  5441.8      .1       0
Bank Sta=4938.7,5040.8
XS Rating Curve= 0 ,0
Exp/Cntr=0.3,0.1

Type RM Length L Ch R = 1 ,661401  ,2030,2030,2030
BEGIN DESCRIPTION:
PEDERNALES RIVER 16.0
END DESCRIPTION:
XS GIS Cut Line= 3
      2618551.36     10077711.85      2619856.71     10077440.84
      2621788.35     10074087.83
#Sta/Elev= 30
  1362.9 2179.79    1748    2173  2023.8 2165.34  2704.1 2158.23  2972.8 2150.39
  3331.9 2136.84  3412.4 2133.04  3500.6 2124.76  3632.2 2127.05  3728.5 2131.67
    3931 2133.38  4050.3  2133.5  4149.3 2130.02  4334.8 2122.05  4533.1 2117.98
  4709.8 2109.45  4920.1 2108.17  4988.5 2105.54  5031.3 2100.61  5058.9 2106.79
  5074.7 2107.31  5331.9 2119.87  5337.6 2118.37    5477 2130.66  5659.5 2139.73
  5793.1 2149.18  5964.1 2156.24  6079.3 2158.76  6452.5 2169.14  6565.7 2169.02
#Mann= 7 ,-1 , 0
  1362.9      .1       0    3931     .05       0  4149.3      .1       0
  4920.1     .07       0  5074.7      .1       0  5964.1     .05       0
  6079.3      .1       0
Bank Sta=4920.1,5074.7
XS Rating Curve= 0 ,0
Exp/Cntr=0.3,0.1

Type RM Length L Ch R = 1 ,659371  ,1409,1409,1409
BEGIN DESCRIPTION:
PEDERNALES RIVER 17.0
END DESCRIPTION:
XS GIS Cut Line= 4
      2620112.72     10077810.65      2621866.18     10077267.17
      2622719.98     10075725.62      2622628.15     10075247.92
#Sta/Elev= 30
  2446.6 2157.22  2792.1 2153.99  2829.7 2153.21  2850.4 2148.15  2899.5 2148.25
  2922.2 2150.86  3133.5 2146.18  3806.3 2128.24  4001.9 2120.52  4221.9 2116.85
    4550 2106.78  4896.9 2098.49  4949.3 2098.55  4956.4 2098.28  4978.2 2093.19
    4994 2091.57  5021.7 2098.36  5081.2 2098.96    5206 2096.33  5309.1 2099.71
  5406.4 2106.03    5465 2113.62  5567.2    2123  5623.9 2127.72  5689.4 2130.62
  5709.2 2131.64  5883.8 2137.38  6030.3 2144.06  6449.3 2150.58    6531 2150.69
#Mann= 9 ,-1 , 0
  2446.6      .1       0  2792.1     .05       0  2899.5      .1       0
  4956.4     .07       0  5021.7      .1       0    5465     .16       0
  5567.2      .1       0  5689.4     .16       0  5709.2      .1       0
Bank Sta=4949.3,5021.7
XS Rating Curve= 0 ,0
Exp/Cntr=0.3,0.1

Type RM Length L Ch R = 1 ,657962  ,1198,1198,1198
BEGIN DESCRIPTION:
PEDERNALES RIVER 18.0
END DESCRIPTION:
XS GIS Cut Line= 3
      2622729.08     10079534.37       2623332.6     10076221.17
      2622996.87     10075251.47
#Sta/Elev= 30
  2638.7 2153.19  2887.4 2150.55  3110.8 2144.24  3445.9 2132.91  3664.2 2122.83
  3848.9 2117.79  3899.8 2114.05  4011.6 2109.89  4286.2 2103.38  4722.9 2097.55
  4936.5  2093.1  4956.9  2090.9  4987.4 2083.01  4997.3 2082.13  5009.8 2083.12
  5048.4 2090.85    5089 2090.14  5200.8 2093.03  5344.9 2092.79  5444.8 2094.96
  5465.1 2097.39  5536.3 2113.69  5563.1 2116.55    5675 2123.23  5748.8 2124.54
    5840  2126.4  5963.2 2125.41  6213.9 2127.74  6701.8 2142.21  7032.6 2144.32
#Mann= 5 ,-1 , 0
  2638.7      .1       0  4956.9     .07       0  5048.4      .1       0
  5563.1     .16       0  5748.8      .1       0
Bank Sta=4956.9,5048.4
XS Rating Curve= 0 ,0
Exp/Cntr=0.3,0.1

Type RM Length L Ch R = 1 ,656764  ,760,760,760
BEGIN DESCRIPTION:
PEDERNALES RIVER 19.0
END DESCRIPTION:
XS GIS Cut Line= 2
      2624535.47      10079100.1      2624174.79      10075667.8
#Sta/Elev= 30
  2979.7 2146.33  3191.3 2145.91  3579.4 2138.61  3649.7 2134.35  3764.9 2130.82
  3800.6 2127.23  3901.1 2121.25  4001.7 2117.17  4092.2 2109.07  4212.8 2102.07
  4303.3 2098.73  4338.5 2096.09  4353.6 2091.64  4444.1 2087.14  4524.5 2085.88
    4819  2087.4  4836.2 2085.45  4956.9 2084.51    5017 2078.24  5037.3  2084.4
  5057.4 2087.71  5485.7  2087.7  5630.6  2089.6  5741.2 2095.04  5861.9 2106.64
  5912.1  2113.1  5966.3 2116.27  6042.8  2117.7  6255.6 2126.79  6430.9  2127.3
#Mann= 3 , 0 , 0
  2979.7      .1       0  4956.9     .07       0  5037.3      .1       0
Bank Sta=4956.9,5037.3
XS Rating Curve= 0 ,0
Exp/Cntr=0.3,0.1

Type RM Length L Ch R = 1 ,656004  ,1038,1038,1038
BEGIN DESCRIPTION:
PEDERNALES RIVER 20.0
END DESCRIPTION:
XS GIS Cut Line= 3
      2624842.85      10078799.9      2625170.09     10077740.38
       2624431.2     10073357.12
#Sta/Elev= 30
  2992.4 2132.34  3803.6 2120.36  4042.6 2113.14  4137.3 2103.17  4263.4 2099.53
  4300.7 2092.02  4341.3 2087.31  4412.3 2083.43  4675.9 2082.05  4726.6  2078.3
  4923.8 2082.52  5020.5 2077.27  5044.8 2082.57  5517.7  2086.1  6189.3 2098.62
  6370.8 2098.76    6836  2088.7  6947.5 2088.44  6965.7 2086.43  6998.3 2089.49
  7224.2 2093.89  7324.6 2097.52  7425.1 2100.64  7535.7 2103.13  7749.3  2118.2
  7827.1 2120.48  8128.5 2135.12  8219.8 2140.33  8335.8 2146.09  8546.4 2154.25
#Mann= 11 ,-1 , 0
  2992.4      .1       0  4923.8     .07       0  5044.8      .1       0
  7224.2     .05       0  7324.6     .08       0  7425.1     .05       0
  7749.3     .16       0  7827.1      .1       0  8128.5     .05       0
  8219.8     .16       0  8335.8      .1       0
Bank Sta=4923.8,5044.8
XS Rating Curve= 0 ,0
Exp/Cntr=0.3,0.1

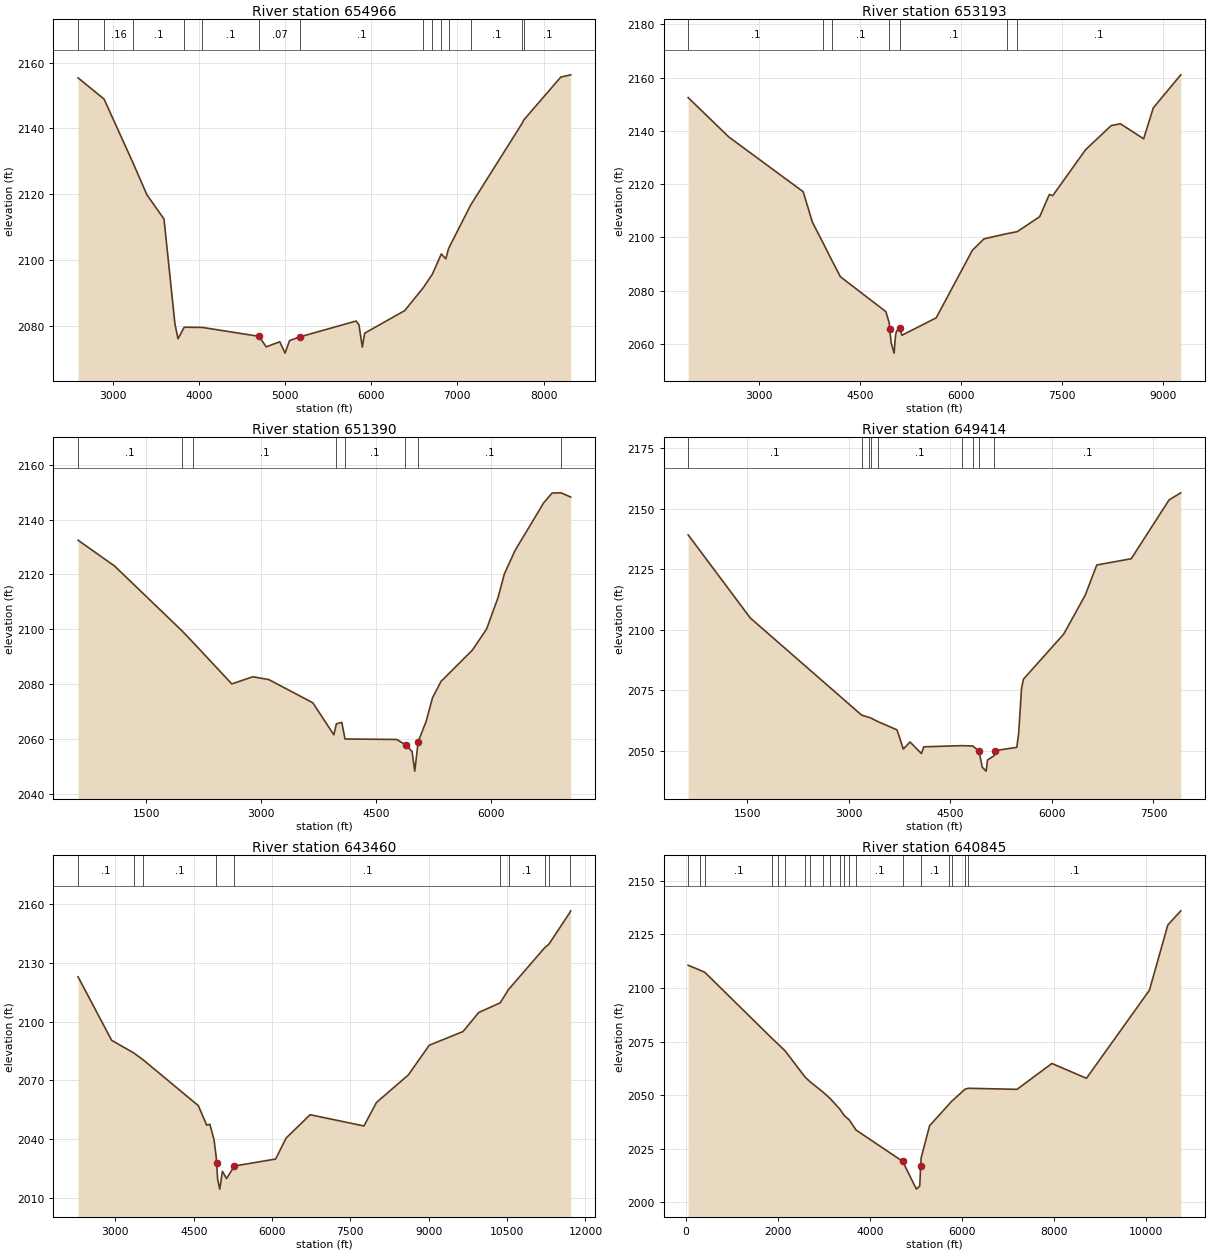
Type RM Length L Ch R = 1 ,654966  ,1773,1773,1773
BEGIN DESCRIPTION:
PEDERNALES RIVER 21.0
END DESCRIPTION:
XS GIS Cut Line= 3
      2627145.82     10078296.68      2626117.25     10077190.71
      2624928.14     10073153.11
#Sta/Elev= 30
  2595.9 2155.36  2897.8 2148.91  3231.1 2129.66  3395.5 2119.78  3593.9 2112.39
  3720.9 2080.47  3756.6 2075.95  3828.2 2079.48  4038.6 2079.42  4697.3 2076.71
  4780.7  2073.5    4938 2075.06  4999.2  2071.6  5051.7 2075.43  5176.6 2076.58
  5823.5 2081.37  5856.9 2080.25  5896.1 2073.44  5923.5 2077.67  6388.2 2084.53
  6606.1 2091.59    6710 2095.65  6813.8 2101.79  6865.6 2100.29  6897.1  2103.4
  7154.4 2116.67  7753.1  2141.6  7771.8 2142.58    8200 2155.58  8315.3 2156.28
#Mann= 14 ,-1 , 0
  2595.9      .1       0  2897.8     .16       0  3231.1      .1       0
  3828.2     .05       0  4038.6      .1       0  4697.3     .07       0
  5176.6      .1       0  6606.1     .16       0    6710      .1       0
  6813.8     .05       0  6897.1     .16       0  7154.4      .1       0
  7753.1     .16       0  7771.8      .1       0
Bank Sta=4697.3,5176.6
XS Rating Curve= 0 ,0
Exp/Cntr=0.3,0.1

Type RM Length L Ch R = 1 ,653193  ,1803,1803,1803
BEGIN DESCRIPTION:
PEDERNALES RIVER 22.0
END DESCRIPTION:
XS GIS Cut Line= 3
      2627547.97     10077910.82      2627897.15     10076282.99
       2624635.9      10071678.5
#Sta/Elev= 30
  1952.1 2152.51  2554.1 2137.75  3658.4 2117.18    3795 2105.75  3955.9 2097.84
  4080.2 2091.59    4211 2085.25  4885.4 2072.16  4935.8 2067.79  4941.9 2065.68
    4964 2060.43  5006.9 2056.59  5028.1 2063.16  5042.9 2064.86  5093.3 2065.94
  5122.9  2063.3  5631.1 2069.82  6168.9 2095.22  6341.1 2099.49  6680.3 2101.43
  6833.9 2102.19  7166.9 2107.82  7309.6 2116.15  7360.1 2115.69  7847.4 2132.95
  8227.6    2142  8364.2 2142.68  8708.8 2137.04  8851.6 2148.65  9259.4 2161.05
#Mann= 7 ,-1 , 0
  1952.1      .1       0  3955.9     .05       0  4080.2      .1       0
  4935.8     .07       0  5093.3      .1       0  6680.3     .16       0
  6833.9      .1       0
Bank Sta=4941.9,5093.3
XS Rating Curve= 0 ,0
Exp/Cntr=0.3,0.1

Type RM Length L Ch R = 1 ,651390  ,1976,1976,1976
BEGIN DESCRIPTION:
PEDERNALES RIVER 25.0
END DESCRIPTION:
XS GIS Cut Line= 3
      2629776.19     10077706.07      2628743.97     10075152.12
       2627074.4     10071882.26
#Sta/Elev= 30
   611.1 2132.49  1088.2 2123.05  1962.6 2099.53    2109 2095.25  2617.1 2080.02
  2890.8 2082.64    3100  2081.6  3673.7 2073.14  3947.8 2061.44  3981.1 2065.46
  4051.5 2065.99  4093.3 2059.92  4767.5 2059.75  4879.2 2057.85  4884.8  2057.8
  4968.1 2055.36    5003 2048.19  5048.2 2058.97  5151.5 2066.32  5234.7 2074.94
  5345.9 2080.95  5755.5 2092.38  5940.3 2100.07  6090.2  2111.6    6171  2120.1
  6312.4 2128.77  6684.6 2146.11  6795.7 2149.72  6911.4 2149.78  7037.2 2148.24
#Mann= 8 ,-1 , 0
   611.1      .1       0  1962.6     .05       0    2109      .1       0
  3981.1     .05       0  4093.3      .1       0  4879.2     .07       0
  5048.2      .1       0  6911.4     .16       0
Bank Sta=4884.8,5048.2
XS Rating Curve= 0 ,0
Exp/Cntr=0.3,0.1

Type RM Length L Ch R = 1 ,649414  ,2540,2540,2540
BEGIN DESCRIPTION:
PEDERNALES RIVER 26.0
END DESCRIPTION:
XS GIS Cut Line= 3
      2631743.19     10076979.42      2630343.43     10073796.07
      2627772.94     10070995.22
#Sta/Elev= 30
     625 2139.32  1543.4 2104.96  3189.4 2064.81  3298.9 2063.87    3321 2063.67
  3425.7 2062.19  3711.8 2058.72  3804.5  2050.8  3903.3 2053.73  4072.2 2048.94
  4107.5 2051.73  4676.1 2052.21  4832.3 2052.05  4921.4  2049.9  4928.7 2049.12
  4971.3 2043.27  5027.8 2041.68    5049 2046.31  5148.3  2048.1    5155 2050.15
  5480.6 2051.49    5509  2057.4  5551.5 2075.99  5579.9  2079.7  6174.3  2098.3
    6493 2114.43  6662.6 2126.86  7172.5 2129.45  7731.2 2153.75  7904.1 2156.68
#Mann= 9 ,-1 , 0
     625      .1       0  3189.4     .05       0  3298.9      .1       0
    3321     .08       0  3425.7      .1       0  4676.1     .05       0
  4832.3      .1       0  4928.7     .07       0  5148.3      .1       0
Bank Sta=4921.4,5155
XS Rating Curve= 0 ,0
Exp/Cntr=0.3,0.1

Type RM Length L Ch R = 1 ,643460  ,2615,2615,2615
BEGIN DESCRIPTION:
PEDERNALES RIVER 29.0
END DESCRIPTION:
XS GIS Cut Line= 3
      2634957.72     10077047.05      2634976.86     10069950.79
      2633566.61     10068089.37
#Sta/Elev= 30
  2286.1 2122.86  2929.4 2090.46    3350 2084.07  3531.2 2080.55  4589.4 2057.13
  4749.4 2047.19  4809.4 2047.64  4889.4 2039.81  4931.6 2030.83  4939.4 2027.84
  4959.4 2019.46  4999.2 2014.58  5049.4 2023.64  5129.4 2019.96  5279.4 2026.38
  6069.4 2029.92  6269.4 2040.61  6729.4 2052.53  7759.4 2046.78  7999.4 2058.77
  8609.4  2072.8  9009.4 2087.95    9657 2094.94  9956.6 2104.65 10367.9 2109.56
 10527.8 2116.37 11219.1 2137.65 11300.5 2139.48   11696  2155.4 11717.7 2156.49
#Mann= 10 ,-1 , 0
  2286.1      .1       0    3350     .16       0  3531.2      .1       0
  4931.6     .07       0  5279.4      .1       0 10367.9     .16       0
 10527.8      .1       0 11219.1     .16       0 11300.5      .1       0
   11696     .16       0
Bank Sta=4939.4,5279.4
XS Rating Curve= 0 ,0
Exp/Cntr=0.3,0.1

Type RM Length L Ch R = 1 ,640845  ,1614,1614,1614
BEGIN DESCRIPTION:
PEDERNALES RIVER 30.0
END DESCRIPTION:
XS GIS Cut Line= 3
      2635544.11     10077010.62      2637285.35     10074752.62
      2635509.69     10067114.19
#Sta/Elev= 30
    52.6 2110.62   300.9 2108.41   416.6  2107.3  1877.6 2076.42  1997.6 2073.97
  2157.5  2070.7  2589.4 2058.52  2698.7  2056.3  2972.6  2051.6    3138 2048.39
  3342.1 2043.61  3444.1 2040.45  3546.1 2038.59  3697.5 2033.77  4709.8 2019.16
  5007.3 2006.21  5080.5 2007.69  5099.9  2017.2  5110.2 2020.73  5293.5 2035.77
  5711.6  2045.7  5769.5 2047.11  6061.6 2052.78  6129.3 2053.24  7192.7 2052.75
    7948 2064.82  8698.1  2057.9 10065.4 2098.96 10464.3 2129.37 10746.1    2136
#Mann= 20 ,-1 , 0
    52.6      .1       0   300.9     .05       0   416.6      .1       0
  1877.6     .05       0  1997.6     .08       0  2157.5     .05       0
  2589.4     .08       0  2698.7     .05       0  2972.6     .08       0
    3138      .1       0  3342.1      .1       0  3444.1     .08       0
  3546.1     .05       0  3697.5      .1       0  4709.8     .07       0
  5110.2      .1       0  5711.6     .16       0  5769.5      .1       0
  6061.6     .16       0  6129.3      .1       0
Bank Sta=4709.8,5099.9
XS Rating Curve= 0 ,0
Exp/Cntr=0.3,0.1

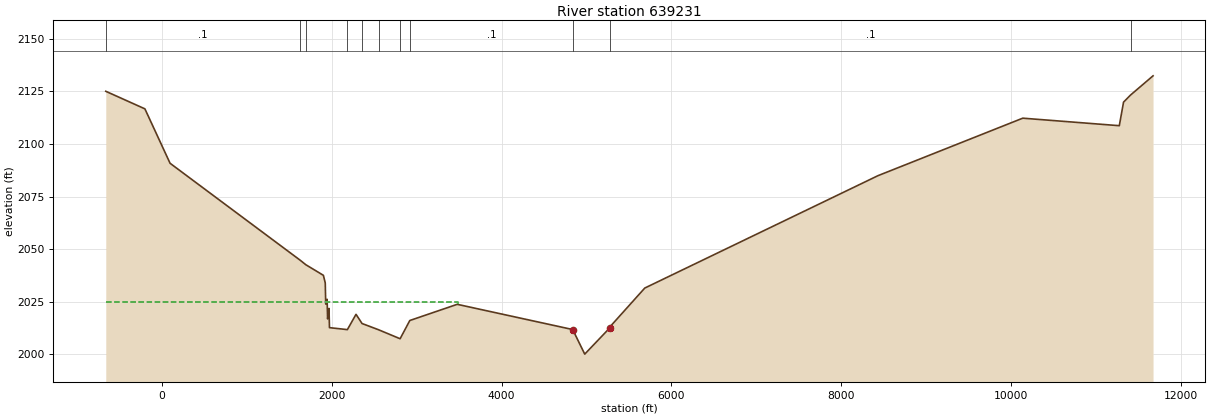
Type RM Length L Ch R = 1 ,639231  ,2540,2540,2540
BEGIN DESCRIPTION:
PEDERNALES RIVER 31.0
END DESCRIPTION:
XS GIS Cut Line= 4
      2640549.54     10077656.02      2638617.74     10074030.58
      2637540.89     10067854.43      2636365.72     10066299.61
#Sta/Elev= 30
  -658.4 2125.03  -197.9 2116.68    98.3 2090.83  1628.2 2044.82  1695.5 2042.65
  1902.8  2037.6  1924.8 2033.99  1930.5 2023.93  1946.8  2026.2  1952.4 2016.89
  1968.7 2021.87  1974.4 2012.74  2185.3  2011.8  2286.9 2019.07  2357.8  2014.7
  2551.6 2011.75  2805.9 2007.47    2920 2016.13  3478.2 2023.82  4837.1 2011.84
  4978.9 2000.16  5273.6 2012.62    5279 2013.28  5685.7 2031.55  8430.5 2084.94
 10134.5 2112.25 11270.7 2108.68 11320.7 2119.87 11403.1 2123.24 11667.9 2132.37
#Mann= 11 ,-1 , 0
  -658.4      .1       0  1628.2     .05       0  1695.5      .1       0
  2185.3     .16       0  2357.8     .05       0  2551.6      .1       0
  2805.9     .05       0    2920      .1       0  4837.1     .07       0
    5279      .1       0 11403.1     .16       0
#XS Ineff= 2 , 0
         3488.64 2024.71
Permanent Ineff=
       F       F
Bank Sta=4837.1,5273.6
XS Rating Curve= 0 ,0
Exp/Cntr=0.3,0.1