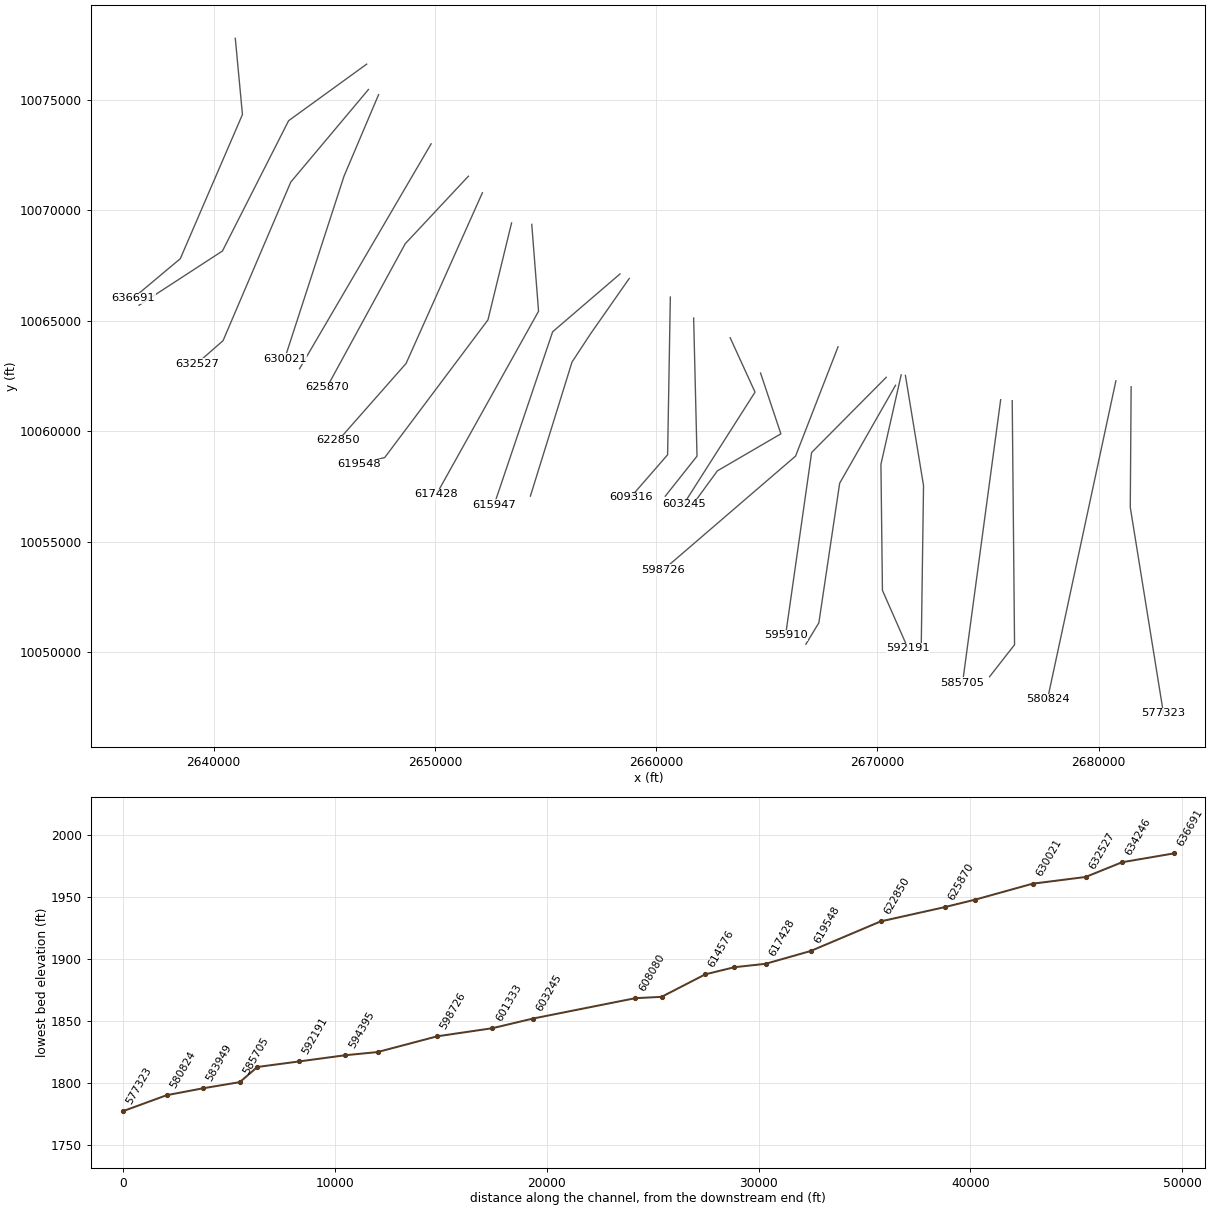
HEC-RAS study PEDERNALES RIVER.prj: PEDERNALES RIVER Base Level Engineering

--- PEDERNALES RIVER.g02 (geometry) --- (continued)

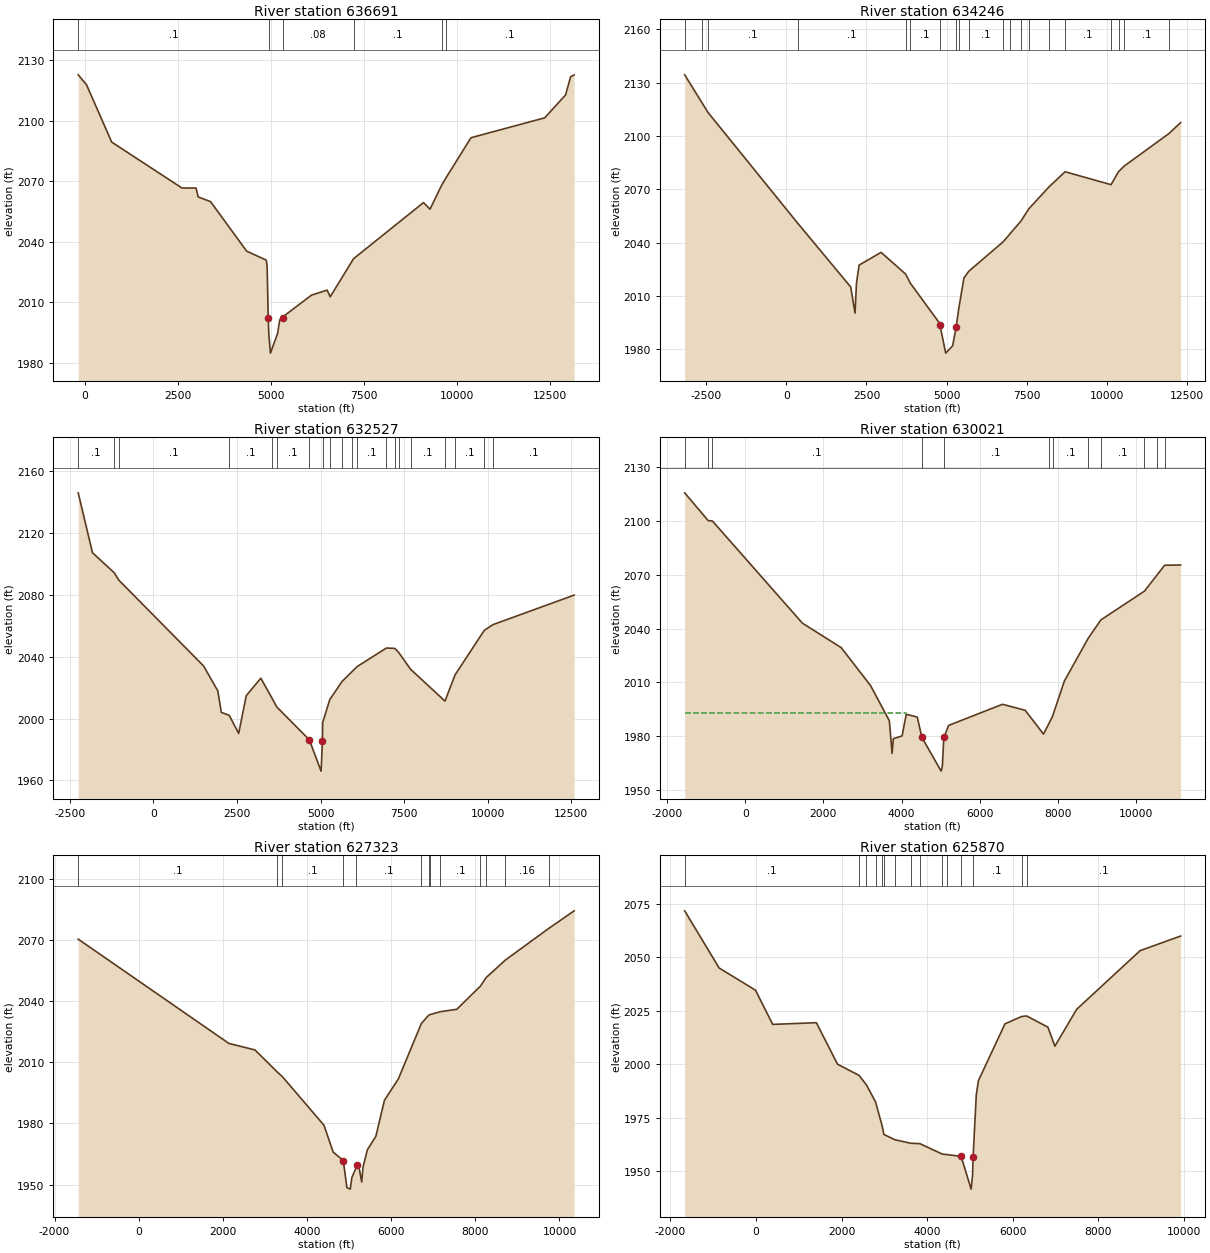
Type RM Length L Ch R = 1 ,636691  ,2445,2445,2445
BEGIN DESCRIPTION:
PEDERNALES RIVER 32.0
END DESCRIPTION:
XS GIS Cut Line= 4
      2640982.23     10077769.71       2641305.3     10074322.93
      2638496.42     10067800.68      2636369.76     10066018.11
#Sta/Elev= 30
  -179.1 2122.77    45.7 2117.83   720.8 2089.46  2609.1 2066.73  2990.7 2066.67
  3047.4 2062.29  3379.9 2059.97  4351.8 2035.42  4878.6    2031  4902.1 2027.75
  4931.1 2002.46  4947.8 1994.19  4991.1 1984.91  5182.7 1994.64  5241.7 2001.42
    5318 2002.34  5328.8 2002.93  6095.1 2013.65  6515.6 2016.12  6598.3 2012.82
  7226.5 2031.69  9107.3 2059.48  9282.9  2056.2  9596.8 2068.15  9702.5 2071.45
 10384.2 2091.61 12367.8 2101.47 12928.5 2112.82 13063.8  2121.8 13159.1 2122.72
#Mann= 6 ,-1 , 0
  -179.1      .1       0  4947.8     .07       0  5328.8     .08       0
  7226.5      .1       0  9596.8     .16       0  9702.5      .1       0
Bank Sta=4931.1,5318
XS Rating Curve= 0 ,0
Exp/Cntr=0.3,0.1

Type RM Length L Ch R = 1 ,634246  ,1719,1719,1719
BEGIN DESCRIPTION:
PEDERNALES RIVER 33.0
END DESCRIPTION:
XS GIS Cut Line= 4
      2646920.71     10076603.28        2643392.      10074043.9
      2640402.06     10068148.84      2636633.42      10065695.2
#Sta/Elev= 30
 -3169.4 2134.47 -2629.5 2118.77 -2442.1  2113.3   363.6 2050.76  2009.3 2015.02
    2143  2000.3  2187.9 2017.14  2270.9 2027.36  2955.5 2034.54  3718.9 2022.33
  3866.7 2017.21  4786.8 1994.46  4792.4 1993.56  4970.3  1977.8  5187.6 1981.95
  5298.9 1992.68  5377.1 2002.75  5538.3 2020.02  5688.9 2023.87  6760.3 2040.42
  6983.1 2045.12  7321.5 2052.25  7563.1 2059.05  8191.4 2071.37    8695  2079.9
 10127.1 2072.63 10360.2 2079.96 10540.3 2083.14 11928.1 2101.34 12296.7 2107.61
#Mann= 20 ,-1 , 0
 -3169.4      .1       0 -2629.5     .05       0 -2442.1      .1       0
   363.6      .1       0  3718.9     .05       0  3866.7      .1       0
  4786.8     .07       0  5298.9      .1       0  5377.1     .16       0
  5688.9      .1       0  6760.3     .05       0  6983.1      .1       0
  7321.5     .05       0  7563.1      .1       0  8191.4      .1       0
    8695      .1       0 10127.1     .16       0 10360.2     .16       0
 10540.3      .1       0 11928.1      .1       0
Bank Sta=4792.4,5298.9
XS Rating Curve= 0 ,0
Exp/Cntr=0.3,0.1

Type RM Length L Ch R = 1 ,632527  ,2506,2506,2506
BEGIN DESCRIPTION:
PEDERNALES RIVER 34.0
END DESCRIPTION:
XS GIS Cut Line= 4
      2646999.48     10075454.03       2643490.1     10071267.22
      2640428.57     10064090.86      2639248.32     10063057.78
#Sta/Elev= 30
 -2250.9 2146.17 -1823.8 2107.36 -1172.3 2094.38   -1039 2089.68  1497.7  2034.1
  1924.4 2017.93  2029.8 2003.97  2264.6 2002.11  2548.9 1990.38  2775.3 2014.82
  3211.2 2026.13  3547.5 2013.14  3687.7 2007.51  4661.9 1986.25  5013.9 1965.95
  5053.3 1985.28  5061.4 1997.44  5273.9 2012.31  5640.8    2024  5946.2 2030.55
  6092.6 2033.67  6967.9 2045.67  7223.1 2045.41    7335 2042.79  7689.6 2031.94
  8719.2  2011.3  9019.6 2028.24  9892.6 2057.04 10152.4  2060.8 12582.8 2079.94
#Mann= 20 ,-1 , 0
 -2250.9      .1       0 -1172.3     .05       0   -1039      .1       0
  2264.6      .1       0  3547.5     .05       0  3687.7      .1       0
  4661.9     .07       0  5061.4      .1       0  5273.9     .16       0
  5640.8      .1       0  5946.2     .05       0  6092.6      .1       0
  6967.9      .1       0  7223.1     .05       0    7335      .1       0
  7689.6      .1       0  8719.2     .16       0  9019.6      .1       0
  9892.6     .05       0 10152.4      .1       0
Bank Sta=4661.9,5053.3
XS Rating Curve= 0 ,0
Exp/Cntr=0.3,0.1

Type RM Length L Ch R = 1 ,630021  ,2698,2698,2698
BEGIN DESCRIPTION:
PEDERNALES RIVER 36.0
END DESCRIPTION:
XS GIS Cut Line= 3
      2647457.98     10075220.77      2645895.84     10071534.53
      2643216.28     10063278.14
#Sta/Elev= 30
 -1548.7 2115.82  -947.9 2100.33    -839 2100.09  1461.7  2043.1  2454.9 2029.43
  3207.5 2008.19  3685.8 1988.64  3756.2 1970.35  3788.2  1978.6  4011.7 1980.19
  4118.4 1992.29  4400.7 1990.65  4516.4 1979.44  5010.2 1960.52    5042 1963.32
  5073.6 1977.02  5082.7  1979.3  5199.7 1986.01  6579.5 1997.82  7160.1 1994.47
  7628.3  1981.2  7764.8 1986.96  7859.5 1991.11  8161.6 2010.76  8770.9 2034.62
  9095.2 2044.89 10210.8 2060.96 10527.3 2069.84 10726.2 2075.41 11135.2 2075.56
#Mann= 12 ,-1 , 0
 -1548.7      .1       0  -947.9     .05       0    -839      .1       0
  4516.4     .07       0  5073.6      .1       0  7764.8     .16       0
  7859.5      .1       0  8770.9     .16       0  9095.2      .1       0
 10210.8     .16       0 10527.3      .1       0 10726.2     .16       0
#XS Ineff= 2 , 0
         4117.05 1992.84
Permanent Ineff=
       F       F
Bank Sta=4516.4,5082.7
XS Rating Curve= 0 ,0
Exp/Cntr=0.3,0.1

Type RM Length L Ch R = 1 ,627323  ,1453,1453,1453
BEGIN DESCRIPTION:
PEDERNALES RIVER 37.0
END DESCRIPTION:
XS GIS Cut Line= 2
      2649832.53     10072996.27      2643885.65     10062821.17
#Sta/Elev= 30
 -1436.8 2070.44  2143.9 2019.25  2763.8 2016.05  3295.1  2005.2  3416.6 2002.92
  4402.8 1979.12  4621.9 1965.95  4862.4 1961.75  4948.4 1948.48    5029 1947.74
  5065.7 1953.38  5168.3  1958.3  5183.1 1959.82  5220.3 1960.12  5300.5 1951.24
  5330.4 1958.44  5433.5 1966.99  5636.9 1973.69  5840.2 1991.34  6170.8 2001.83
  6718.1 2029.03  6893.8 2033.11  6929.2 2033.45  7167.3 2034.82  7559.4    2036
  8122.8 2047.41  8257.4 2051.57  8716.4 2060.21  9740.7 2075.63 10348.7 2084.33
#Mann= 13 ,-1 , 0
 -1436.8      .1       0  3295.1     .05       0  3416.6      .1       0
  4862.4     .07       0  5168.3      .1       0  6718.1     .16       0
  6893.8      .1       0  6929.2     .16       0  7167.3      .1       0
  8122.8     .16       0  8257.4      .1       0  8716.4     .16       0
  9740.7      .1       0
Bank Sta=4862.4,5183.1
XS Rating Curve= 0 ,0
Exp/Cntr=0.3,0.1

Type RM Length L Ch R = 1 ,625870  ,3020,3020,3020
BEGIN DESCRIPTION:
PEDERNALES RIVER 38.0
END DESCRIPTION:
XS GIS Cut Line= 3
      2651516.67     10071531.92       2648662.3     10068477.06
      2645120.32     10061977.59
#Sta/Elev= 30
 -1662.7 2071.79  -858.5 2045.07    -9.4 2034.69   393.6 2018.68  1412.6 2019.48
  1907.5 2000.06  2411.2 1994.83  2583.3 1990.36  2795.4 1982.41  2951.5 1971.07
  2989.4 1967.21  3249.8 1964.73  3619.2  1963.1  3830.5 1962.91  4355.9 1958.02
  4470.7 1957.79  4793.8 1956.95    5028 1941.65  5060.6 1948.06    5073 1956.48
  5147.9 1985.74  5198.3 1992.41  5818.3 2018.94  6204.2 2022.36  6323.3 2022.64
  6820.9 2017.39  6984.2  2008.5  7491.2 2025.71  8973.3 2053.16  9920.1    2060
#Mann= 15 ,-1 , 0
 -1662.7      .1       0  2411.2     .05       0  2583.3      .1       0
  2795.4     .16       0  2951.5      .1       0  2989.4     .16       0
  3249.8      .1       0  3619.2     .05       0  3830.5      .1       0
  4355.9     .05       0  4470.7      .1       0  4793.8     .07       0
  5060.6      .1       0  6204.2     .16       0  6323.3      .1       0
Bank Sta=4793.8,5073
XS Rating Curve= 0 ,0
Exp/Cntr=0.3,0.1

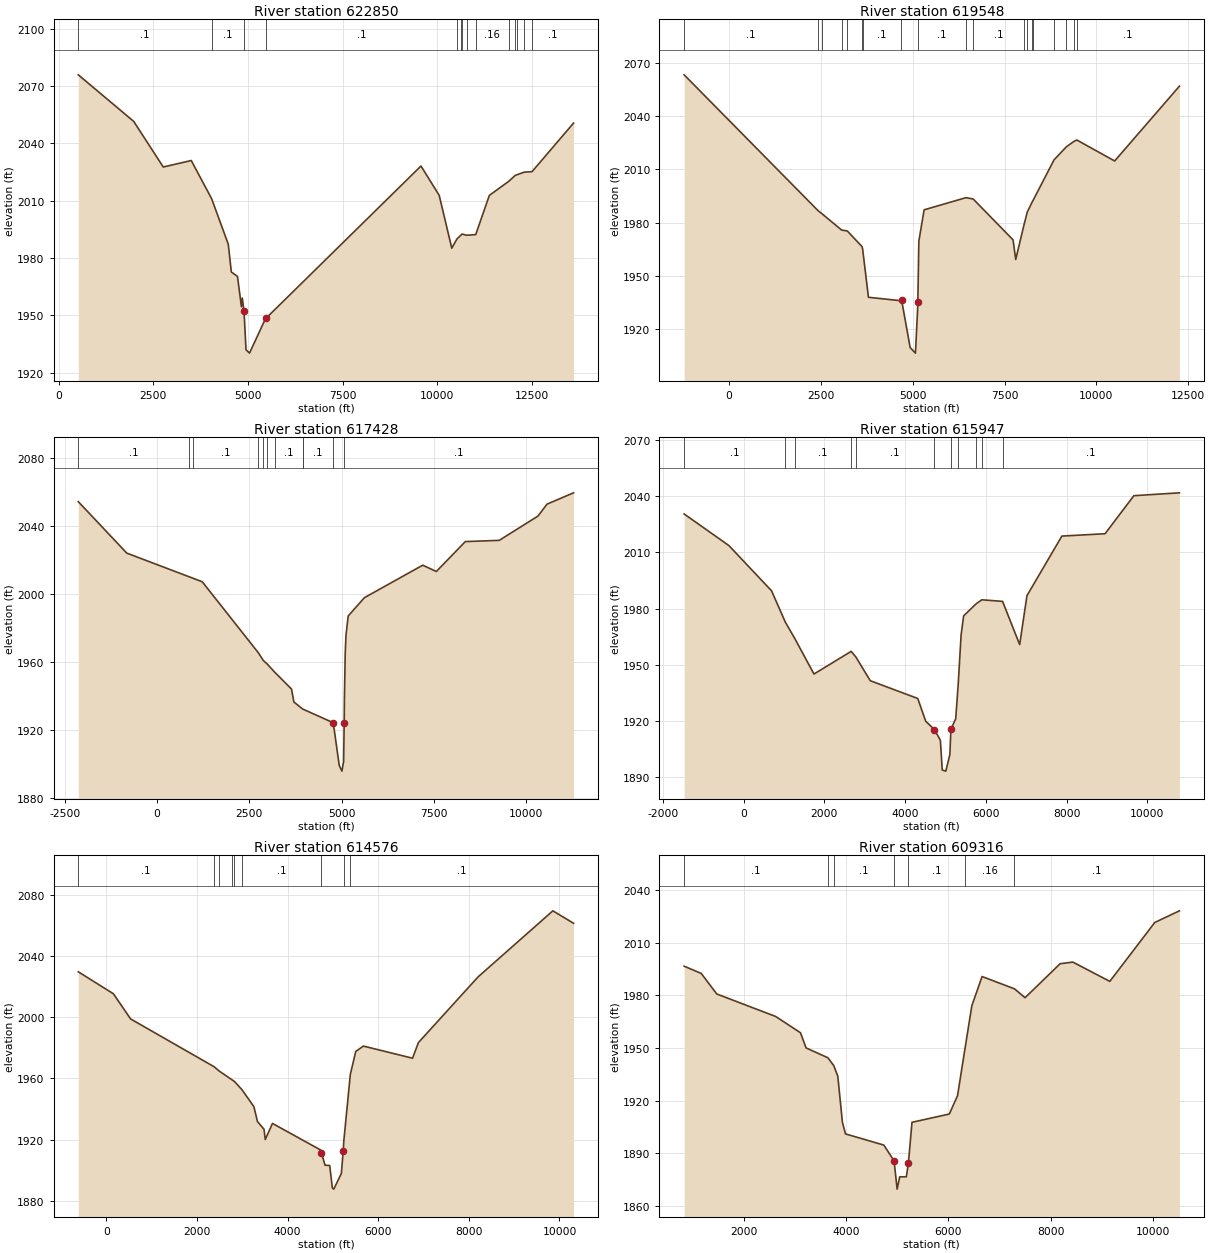
Type RM Length L Ch R = 1 ,622850  ,3302,3302,3302
BEGIN DESCRIPTION:
PEDERNALES RIVER 39.0
END DESCRIPTION:
XS GIS Cut Line= 3
      2652150.61     10070784.28      2648700.67     10063060.66
      2645644.09     10059588.04
#Sta/Elev= 30
   516.4 2075.77  1979.8 2051.41    2761 2027.54  3501.1 2030.93  4039.2 2010.96
  4478.9 1987.16  4559.5 1972.61    4722 1970.32  4825.8 1954.47    4849    1959
  4895.4 1951.95  4947.3 1931.96  5039.9 1930.16  5478.4 1948.88  5485.4 1948.59
  9570.5 2028.06 10051.5 2012.73 10384.5 1985.07 10519.5 1989.87 10632.2 1992.02
 10655.8 1992.47 10774.5 1991.83 11016.7 1992.17 11376.9 2012.69 11894.3 2020.12
 12055.9 2023.07 12094.6 2023.39 12298.2 2024.85 12504.8 2025.11 13601.7 2050.52
#Mann= 14 ,-1 , 0
   516.4      .1       0  4039.2      .1       0  4895.4     .07       0
  5478.4      .1       0 10519.5     .16       0 10632.2      .1       0
 10655.8     .16       0 10774.5      .1       0 11016.7     .16       0
 11894.3      .1       0 12055.9     .16       0 12094.6      .1       0
 12298.2     .16       0 12504.8      .1       0
Bank Sta=4895.4,5485.4
XS Rating Curve= 0 ,0
Exp/Cntr=0.3,0.1

Type RM Length L Ch R = 1 ,619548  ,2120,2120,2120
BEGIN DESCRIPTION:
PEDERNALES RIVER 40.0
END DESCRIPTION:
XS GIS Cut Line= 4
      2653468.94     10069419.68      2652401.32     10065031.83
      2647735.61     10058804.22      2646593.33     10058504.18
#Sta/Elev= 30
 -1219.2 2063.29  2428.9 1986.62  2537.2 1984.87  3068.8 1975.74  3221.7 1975.25
  3623.8 1966.37  3638.3  1965.1  3796.9 1937.84  4690.8 1935.88    4697 1936.52
  4932.5 1909.46    5076 1906.35  5132.5 1929.91  5140.8 1935.21  5168.6  1969.5
  5311.7 1987.15  6451.8 1994.03  6647.8 1993.26  7732.9 1970.21    7805 1959.17
  8020.9 1977.89    8120 1985.93  8245.9 1991.28  8282.5 1992.69  8847.4 2015.33
  9183.5  2022.7    9386  2025.7  9467.2 2026.54 10497.9 2014.71 12259.2 2056.88
#Mann= 19 ,-1 , 0
 -1219.2      .1       0  2428.9     .16       0  2537.2      .1       0
  3068.8     .05       0  3221.7      .1       0  3623.8     .16       0
  3638.3      .1       0  4690.8     .07       0  5132.5      .1       0
  6451.8     .16       0  6647.8      .1       0  8020.9     .16       0
    8120      .1       0  8245.9     .16       0  8282.5      .1       0
  8847.4     .16       0  9183.5      .1       0    9386     .16       0
  9467.2      .1       0
Bank Sta=4697,5140.8
XS Rating Curve= 0 ,0
Exp/Cntr=0.3,0.1

Type RM Length L Ch R = 1 ,617428  ,1481,1481,1481
BEGIN DESCRIPTION:
PEDERNALES RIVER 41.0
END DESCRIPTION:
XS GIS Cut Line= 3
      2654381.23     10069352.38       2654688.4     10065423.64
      2650073.34     10057139.45
#Sta/Elev= 30
 -2133.9 2054.44  -819.3  2024.2   857.6  2010.4   966.7  2009.5    1225 2007.38
  2746.7 1965.62  2881.4 1961.08  2978.3 1959.21    3186  1954.3  3644.9 1944.31
    3710 1936.69  3947.6 1932.57  3957.3 1932.48  4776.6 1924.51  4938.9 1899.45
  5011.7 1896.07  5057.7 1901.82 5072.73 1924.61  5079.5 1939.05  5101.2 1965.55
  5122.9 1976.25  5182.4 1987.28  5621.3 1998.02  7202.3 2017.11  7570.4 2013.39
  8355.7 2030.98  9275.9 2031.71 10326.4 2045.99 10569.9 2052.98 11289.8 2059.64
#Mann= 11 ,-1 , 0
 -2133.9      .1       0   857.6     .16       0   966.7      .1       0
  2746.7     .05       0  2881.4      .1       0  2978.3     .16       0
    3186      .1       0  3947.6     .05       0  3957.3      .1       0
  4776.6     .07       0 5072.73      .1       0
Bank Sta=4776.6,5072.73
XS Rating Curve= 0 ,0
Exp/Cntr=0.3,0.1

Type RM Length L Ch R = 1 ,615947  ,1371,1371,1371
BEGIN DESCRIPTION:
PEDERNALES RIVER 42.0
END DESCRIPTION:
XS GIS Cut Line= 3
      2658366.42     10067108.11      2655324.49     10064493.67
      2652683.81     10056677.77
#Sta/Elev= 30
 -1470.1 2030.42  -362.5 2013.58   694.2 1989.44  1033.6 1972.82  1271.2 1963.92
  1744.4 1945.07    2665 1957.15  2781.5 1954.17  3137.5 1941.52  4314.2 1932.02
  4510.9 1919.89  4725.8 1915.49  4873.6 1909.74  4919.8 1893.89  5008.7  1893.3
  5108.5 1902.15  5134.7  1915.6  5253.6 1921.24  5314.4 1939.37  5386.4 1965.75
  5449.3 1976.08  5760.7 1982.55  5899.9 1984.65  6413.7 1983.81  6836.9 1960.76
  7016.7 1986.83  7881.5 2018.63    8951 2019.88  9663.9 2040.16 10790.9 2041.69
#Mann= 11 ,-1 , 0
 -1470.1      .1       0  1033.6     .16       0  1271.2      .1       0
    2665     .05       0  2781.5      .1       0  4725.8     .07       0
  5134.7      .1       0  5314.4     .16       0  5760.7      .1       0
  5899.9     .16       0  6413.7      .1       0
Bank Sta=4725.8,5134.7
XS Rating Curve= 0 ,0
Exp/Cntr=0.3,0.1

Type RM Length L Ch R = 1 ,614576  ,2062,2062,2062
BEGIN DESCRIPTION:
PEDERNALES RIVER 43.0
END DESCRIPTION:
XS GIS Cut Line= 4
      2658785.51     10066904.76       2657044.3     10064409.97
       2656200.2     10063123.84      2654319.15      10057059.5
#Sta/Elev= 30
  -619.3 2029.66   154.7 2015.31   535.9 1998.83  2378.4 1967.58  2493.9 1964.69
  2762.3 1959.26  2826.8 1957.95  2991.7  1952.6  3255.8 1941.49  3334.7 1931.77
  3479.4  1926.7    3507 1919.97  3666.2 1930.52  4728.9 1913.14  4746.8 1911.16
  4826.7 1903.18  4929.6    1903  4987.6 1888.29  5018.8 1887.56  5186.5 1897.81
  5228.1  1912.8  5238.9 1918.56  5384.6 1962.64  5504.5 1977.59  5672.6  1981.1
  6757.1 1973.16  6887.5  1983.4  8205.3 2026.37  9854.2 2069.53 10310.8  2061.4
#Mann= 9 ,-1 , 0
  -619.3      .1       0  2378.4     .16       0  2493.9      .1       0
  2762.3     .16       0  2826.8     .05       0  2991.7      .1       0
  4728.9     .07       0  5238.9     .16       0  5384.6      .1       0
Bank Sta=4746.8,5228.1
XS Rating Curve= 0 ,0
Exp/Cntr=0.3,0.1

Type RM Length L Ch R = 1 ,609316  ,1236,1236,1236
BEGIN DESCRIPTION:
PEDERNALES RIVER 46.0
END DESCRIPTION:
XS GIS Cut Line= 3
      2660644.49     10066067.51      2660521.13     10058930.31
      2658852.35      10057010.6
#Sta/Elev= 30
   834.5 1996.63  1168.3 1992.51  1472.8 1980.77  2626.6 1967.91  3108.6 1958.67
  3218.6    1950  3643.7 1944.41  3759.9  1939.9  3838.7 1933.83  3928.7 1907.61
  3988.7 1900.96  4738.9 1894.57  4938.9 1885.58  4998.6 1869.45  5048.9 1876.48
  5178.9 1876.49  5218.9  1884.4  5288.9 1907.57    6019  1912.3  6179.1 1922.72
  6315.7 1947.88  6459.1 1974.09  6659.1 1990.72  7292.5 1983.72  7499.3 1978.65
  8184.7 1998.03  8432.5 1998.97  9156.1 1987.97 10035.2 2021.56 10516.4 2028.21
#Mann= 7 ,-1 , 0
   834.5      .1       0  3643.7     .05       0  3759.9      .1       0
  4938.9     .07       0  5218.9      .1       0  6315.7     .16       0
  7292.5      .1       0
Bank Sta=4938.9,5218.9
XS Rating Curve= 0 ,0
Exp/Cntr=0.3,0.1

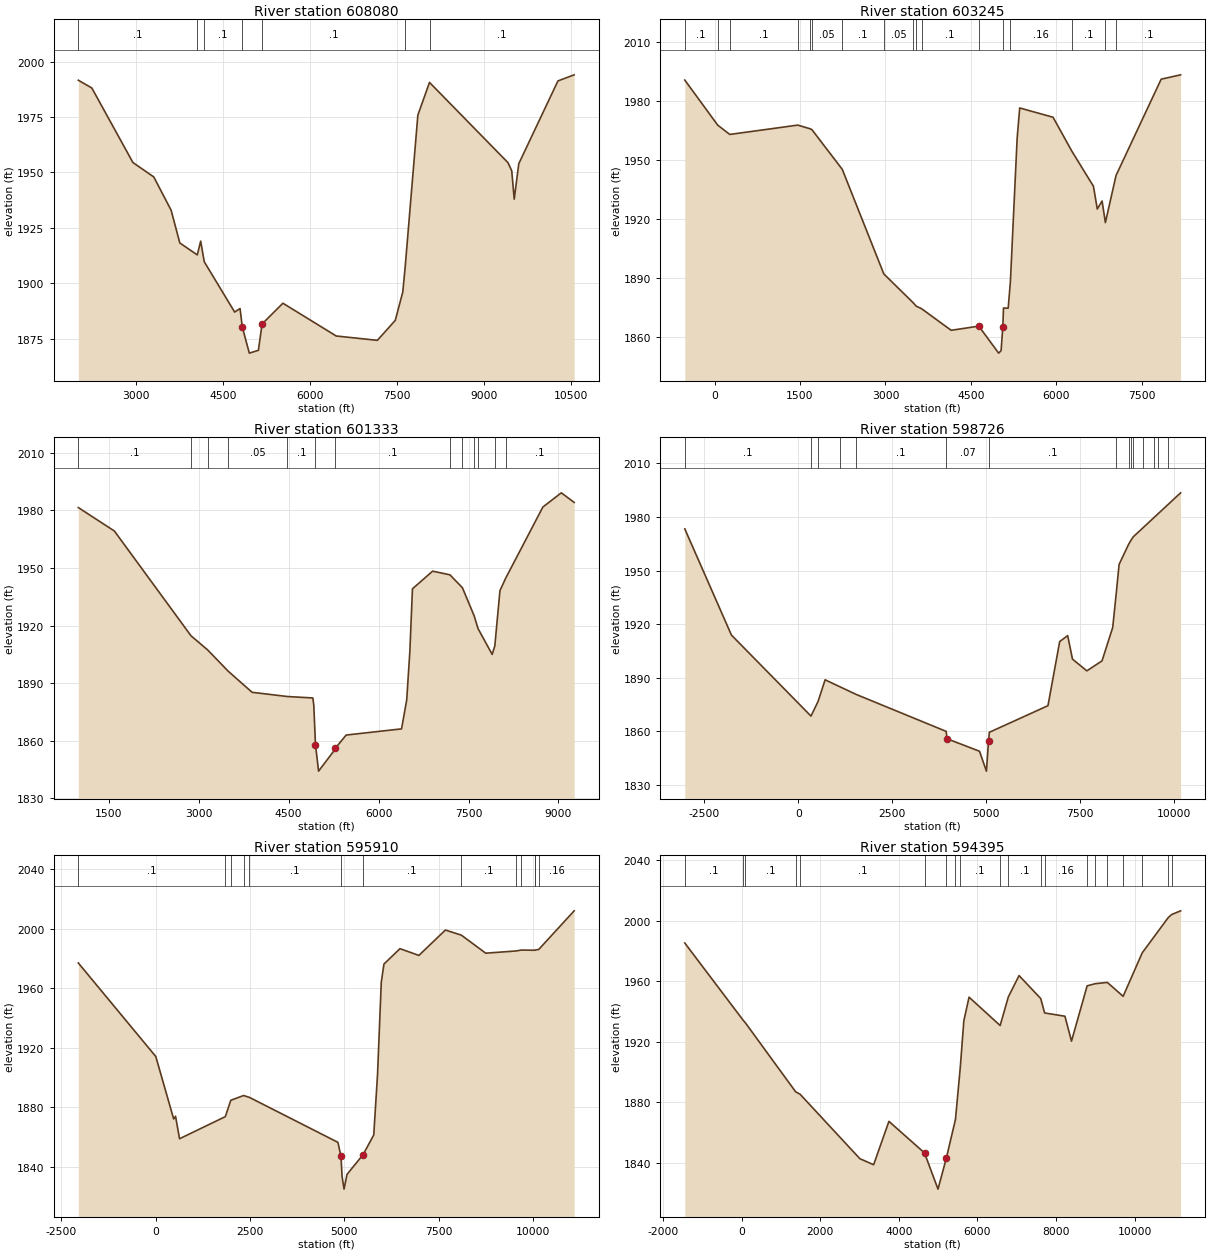
Type RM Length L Ch R = 1 ,608080  ,4835,4835,4835
BEGIN DESCRIPTION:
PEDERNALES RIVER 47.0
END DESCRIPTION:
XS GIS Cut Line= 3
      2661697.51     10065116.42      2661850.06       10058868.
      2660413.39     10057054.11
#Sta/Elev= 30
  1998.3 1991.61  2231.1 1988.12  2941.3 1954.45  3301.4 1947.95  3601.5 1932.89
  3751.5 1918.13  4052.7 1912.75  4111.6 1918.97  4173.4 1909.65  4698.7 1886.93
  4791.8 1888.54  4821.8 1882.05  4831.8 1880.09  4951.6  1868.4  5108.6 1869.67
  5171.9 1881.56    5532 1890.93  6452.3 1876.14  7163.3 1874.17  7472.6 1883.19
  7602.7 1896.02  7644.1 1907.39  7862.7 1975.86    8064 1990.62    9420 1954.38
  9484.2 1950.75  9527.4 1937.91    9606 1953.92 10282.3 1991.29 10562.5 1994.05
#Mann= 7 ,-1 , 0
  1998.3      .1       0  4052.7     .05       0  4173.4      .1       0
  4821.8     .07       0  5171.9      .1       0  7644.1     .16       0
    8064      .1       0
Bank Sta=4831.8,5171.9
XS Rating Curve= 0 ,0
Exp/Cntr=0.3,0.1

Type RM Length L Ch R = 1 ,603245  ,1912,1912,1912
BEGIN DESCRIPTION:
PEDERNALES RIVER 48.0
END DESCRIPTION:
XS GIS Cut Line= 3
      2663348.82      10064224.6      2664471.92     10061763.94
      2661250.85     10056699.31
#Sta/Elev= 30
  -523.1 1990.84    54.4 1967.95   266.6 1963.19  1460.9 1967.94  1670.8 1966.13
  1708.3 1965.67  2242.2 1945.44  2971.9 1892.25  3485.2 1877.67  3540.2 1875.88
  3635.7 1874.56  4154.6 1863.59  4639.8 1865.71  4988.5 1851.98    5031 1853.23
  5061.5 1865.39  5073.7 1874.92  5155.5 1874.82  5194.5 1888.26    5313 1961.19
  5358.1 1976.66  5943.8 1971.94  6277.5  1954.5  6653.4 1936.81  6720.3 1925.27
    6805 1929.34  6862.7 1918.37  7049.7 1942.31  7842.3 1991.29  8183.9 1993.51
#Mann= 17 ,-1 , 0
  -523.1      .1       0    54.4     .16       0   266.6      .1       0
  1460.9     .05       0  1670.8      .1       0  1708.3     .05       0
  2242.2      .1       0  2971.9     .05       0  3485.2      .1       0
  3540.2     .05       0  3635.7      .1       0  4639.8     .07       0
  5061.5      .1       0  5194.5     .16       0  6277.5      .1       0
  6862.7     .16       0  7049.7      .1       0
Bank Sta=4639.8,5061.5
XS Rating Curve= 0 ,0
Exp/Cntr=0.3,0.1

Type RM Length L Ch R = 1 ,601333  ,2607,2607,2607
BEGIN DESCRIPTION:
PEDERNALES RIVER 49.0
END DESCRIPTION:
XS GIS Cut Line= 4
      2664722.07     10062626.34      2665640.29     10059876.74
      2662769.49     10058201.84      2661565.87     10056547.74
#Sta/Elev= 30
     993 1981.43  1594.3 1969.23  2872.2 1914.67  3149.1 1907.34  3491.7 1896.26
  3890.8 1885.26  4479.8 1883.06  4903.5 1882.31  4919.2 1878.64  4947.5 1858.05
  4999.2 1844.22  5271.5 1855.44  5277.2 1856.09  5459.2    1863  6382.8 1866.22
  6468.8 1881.25  6521.7 1906.77  6564.7 1939.14  6901.3 1948.33  7189.4 1946.43
  7397.4 1939.72  7593.5 1925.11  7657.7 1918.48  7894.1 1904.99  7938.1 1909.42
  8023.9 1938.21  8121.9 1944.82  8739.5 1981.71    9047 1989.11  9261.2 1984.11
#Mann= 13 ,-1 , 0
     993      .1       0  2872.2     .16       0  3149.1      .1       0
  3491.7     .05       0  4479.8      .1       0  4947.5     .07       0
  5271.5      .1       0  7189.4     .16       0  7397.4      .1       0
  7593.5     .16       0  7657.7      .1       0  7938.1     .16       0
  8121.9      .1       0
Bank Sta=4947.5,5277.2
XS Rating Curve= 0 ,0
Exp/Cntr=0.3,0.1

Type RM Length L Ch R = 1 ,598726  ,2816,2816,2816
BEGIN DESCRIPTION:
PEDERNALES RIVER 50.0
END DESCRIPTION:
XS GIS Cut Line= 3
      2668223.68     10063813.92      2666303.37     10058868.97
      2660323.12     10053719.69
#Sta/Elev= 30
 -3023.2 1973.31 -1781.7 1913.86   335.5  1868.5   524.6 1876.74   711.1 1888.82
    1114 1884.83  1532.9 1880.68    3934 1859.94  3954.9 1855.83  4820.5 1848.82
  5004.6 1837.69  5060.8 1854.46  5082.8 1859.43  6642.8 1874.34  6954.6 1910.22
  7167.4 1913.56  7294.7 1900.42  7677.6 1893.83  8081.4 1899.43  8365.5  1918.1
  8453.9    1936  8535.6 1953.41  8786.3 1964.55  8850.7 1966.89  8910.2 1968.82
  9166.3 1973.82  9464.5 1979.65  9579.7  1981.9  9830.6  1986.8 10173.2  1993.5
#Mann= 15 ,-1 , 0
 -3023.2      .1       0   335.5     .05       0   524.6      .1       0
    1114     .05       0  1532.9      .1       0    3934     .07       0
  5082.8      .1       0  8453.9     .16       0  8786.3      .1       0
  8850.7     .16       0  8910.2      .1       0  9166.3     .16       0
  9464.5      .1       0  9579.7     .16       0  9830.6      .1       0
Bank Sta=3954.9,5060.8
XS Rating Curve= 0 ,0
Exp/Cntr=0.3,0.1

Type RM Length L Ch R = 1 ,595910  ,1515,1515,1515
BEGIN DESCRIPTION:
PEDERNALES RIVER 51.0
END DESCRIPTION:
XS GIS Cut Line= 3
      2670401.72     10062433.62       2667030.6     10059033.89
      2665853.25     10050765.75
#Sta/Elev= 30
 -2047.6 1977.11     5.3 1914.19     479 1872.18   528.5 1874.01   634.6 1858.89
  1847.5 1873.76  1992.6 1884.75  2331.8 1887.97  2488.1 1886.69  4831.2 1856.48
    4912 1847.24  4942.3 1833.43  4993.5 1825.01  5073.6 1834.95  5497.8 1848.19
  5780.7 1861.41  5881.7 1902.34  5980.2 1964.07  6051.1 1976.38    6476 1986.73
  6976.8 1982.19  7679.6 1999.26  8103.9 1995.81  8747.3  1983.7  9552.9 1985.18
  9689.6 1985.79 10050.7 1985.67 10064.8 1985.86 10152.1 1986.17 11091.7 2012.18
#Mann= 13 ,-1 , 0
 -2047.6      .1       0  1847.5     .05       0  1992.6      .1       0
  2331.8     .05       0  2488.1      .1       0    4912     .07       0
  5497.8      .1       0  8103.9      .1       0  9552.9     .16       0
  9689.6      .1       0 10050.7     .16       0 10064.8      .1       0
 10152.1     .16       0
Bank Sta=4912,5497.8
XS Rating Curve= 0 ,0
Exp/Cntr=0.3,0.1

Type RM Length L Ch R = 1 ,594395  ,2204,2204,2204
BEGIN DESCRIPTION:
PEDERNALES RIVER 52.0
END DESCRIPTION:
XS GIS Cut Line= 4
      2670822.65       10062074.      2668297.24     10057642.67
       2667356.8     10051329.06      2666769.43     10050358.56
#Sta/Elev= 30
 -1445.5 1985.22    47.1 1933.91    87.2 1932.76  1375.7 1886.84    1489 1885.23
  3009.2 1842.62  3359.9 1838.61  3749.2 1867.29  4654.8 1846.43  4998.3 1822.48
  5210.8 1843.04  5442.7 1868.56    5566 1903.21  5655.7 1933.78  5788.4 1949.42
  6579.6 1930.67  6787.8 1949.57    7061 1963.69  7611.3 1948.55  7711.8 1938.98
  8228.5 1936.81  8395.6 1920.32  8793.6  1956.9  8998.2 1958.32  9307.2 1959.17
  9709.5 1949.97 10195.5 1978.73 10855.2 2001.97 10940.5    2004 11172.6 2006.51
#Mann= 20 ,-1 , 0
 -1445.5      .1       0    47.1     .16       0    87.2      .1       0
  1375.7     .05       0    1489      .1       0  4654.8     .07       0
  5210.8      .1       0  5442.7     .16       0    5566      .1       0
  6579.6     .16       0  6787.8      .1       0  7611.3     .16       0
  7711.8     .16       0  8793.6      .1       0  8998.2     .16       0
  9307.2      .1       0  9709.5     .16       0 10195.5     .16       0
 10855.2      .1       0 10940.5     .16       0
Bank Sta=4654.8,5210.8
XS Rating Curve= 0 ,0
Exp/Cntr=0.3,0.1

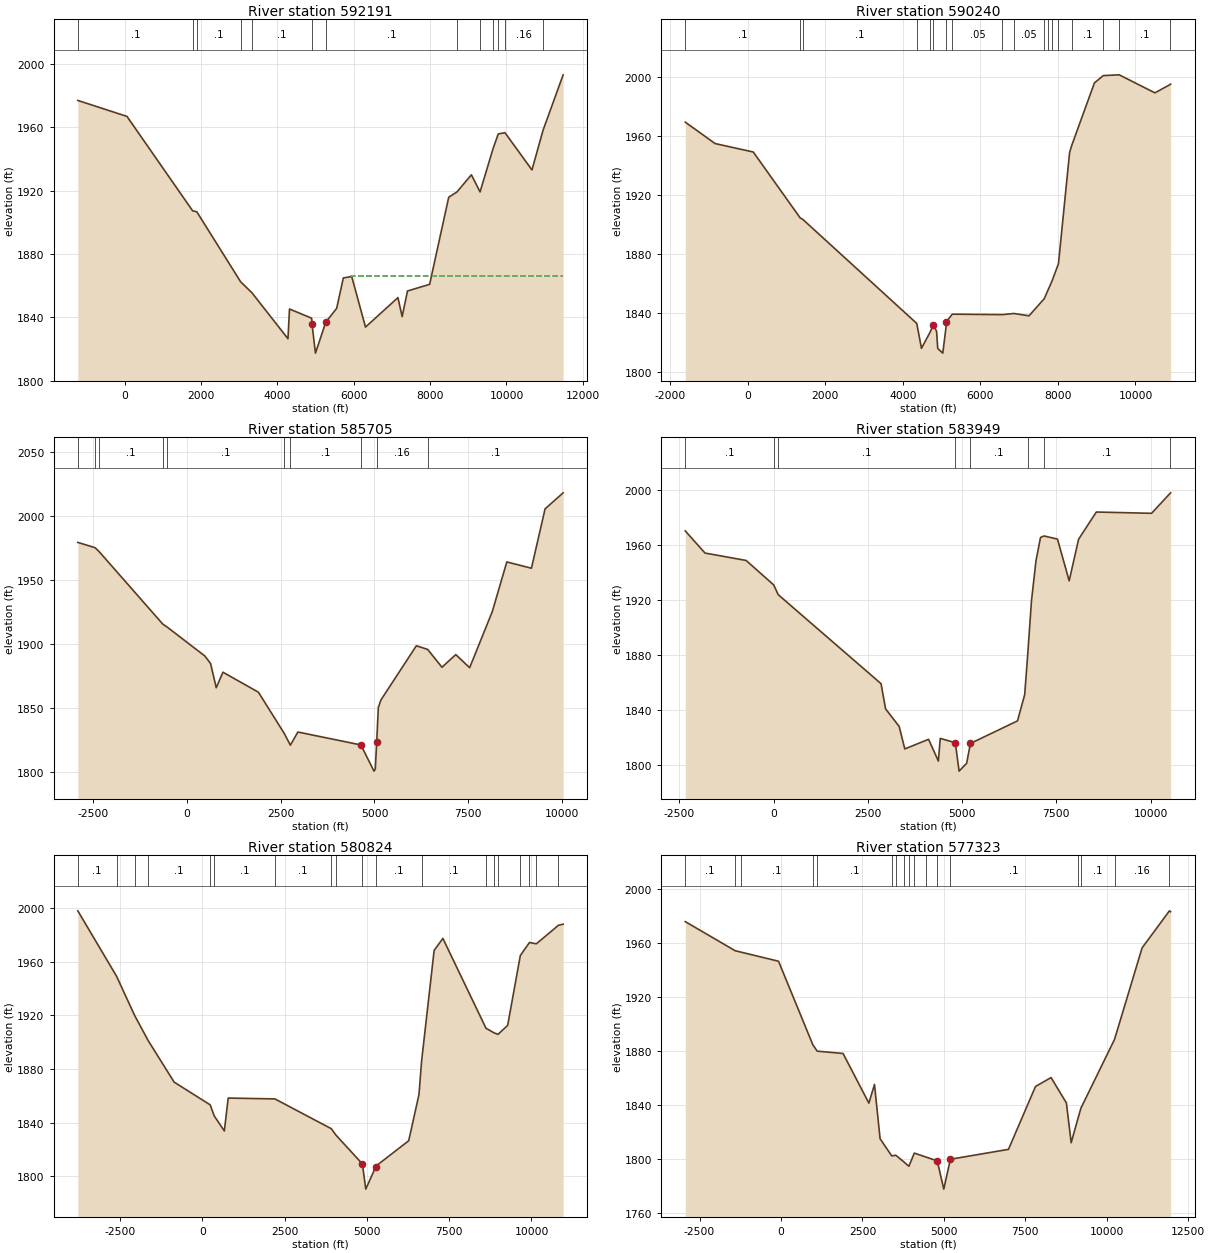
Type RM Length L Ch R = 1 ,592191  ,1951,1951,1951
BEGIN DESCRIPTION:
PEDERNALES RIVER 53.0
END DESCRIPTION:
XS GIS Cut Line= 4
      2671077.46     10062545.83      2670162.12     10058498.27
       2670230.1     10052795.68      2671381.16     10050179.03
#Sta/Elev= 30
 -1226.8 1976.95    61.4 1966.85  1782.5 1907.21  1888.9  1906.7    3039 1862.42
  3334.1 1855.53  4277.6 1826.53  4317.6 1845.29  4897.7 1839.48  4907.7 1835.71
  4997.4 1817.43  5267.7 1836.98  5552.6 1845.68  5727.7 1864.89  5947.7 1865.78
  6307.8 1833.86  7157.8 1852.48  7267.8 1840.45  7407.8 1856.66  7987.9 1860.85
  8487.9 1915.83  8705.5 1919.22  9081.4 1930.01  9308.4 1919.18  9646.5 1946.33
  9784.7 1955.79  9961.2 1956.59 10668.2 1933.06 10957.7 1958.07 11484.6 1993.11
#Mann= 13 ,-1 , 0
 -1226.8      .1       0  1782.5     .05       0  1888.9      .1       0
    3039     .05       0  3334.1      .1       0  4897.7     .07       0
  5267.7      .1       0  8705.5     .16       0  9308.4      .1       0
  9646.5     .16       0  9784.7      .1       0  9961.2     .16       0
 10957.7      .1       0
#XS Ineff= 2 , 0
                         5938.64         1866.33
Permanent Ineff=
       F       F
Bank Sta=4907.7,5267.7
XS Rating Curve= 0 ,0
Exp/Cntr=0.3,0.1

Type RM Length L Ch R = 1 ,590240  ,830,830,830
BEGIN DESCRIPTION:
PEDERNALES RIVER 54.0
END DESCRIPTION:
XS GIS Cut Line= 3
      2671268.77     10062517.68      2672087.75     10057535.94
      2671981.45     10050069.01
#Sta/Elev= 30
 -1609.4 1969.36  -840.5 1954.87   144.2 1949.14  1351.3 1904.62  1425.8 1903.43
  4360.6 1833.09  4481.5 1816.25    4699 1826.92  4791.6 1832.32  4871.6 1827.69
  4901.6 1816.12  5031.3    1813  5111.6 1829.91  5121.6 1834.13  5276.1 1839.37
  6569.9 1839.06  6865.9 1839.83  7254.8 1838.26  7647.8 1849.87  7746.2 1855.74
  7844.6 1861.58  8014.4 1873.52  8301.9 1948.83  8357.9 1953.67    8942 1995.93
    9170 2000.86  9580.5 2001.39 10502.1 1989.19 10895.6 1994.85 10906.9 1995.09
#Mann= 18 ,-1 , 0
 -1609.4      .1       0  1351.3     .05       0  1425.8      .1       0
  4360.6     .16       0    4699      .1       0  4791.6     .07       0
  5111.6      .1       0  5276.1     .05       0  6569.9      .1       0
  6865.9     .05       0  7647.8     .16       0  7746.2      .1       0
  7844.6     .16       0  8014.4     .16       0  8357.9      .1       0
    9170     .16       0  9580.5      .1       0 10895.6     .16       0
Bank Sta=4791.6,5121.6
XS Rating Curve= 0 ,0
Exp/Cntr=0.3,0.1

Type RM Length L Ch R = 1 ,585705  ,1756,1756,1756
BEGIN DESCRIPTION:
PEDERNALES RIVER 56.0
END DESCRIPTION:
XS GIS Cut Line= 2
      2675574.53     10061423.18      2673852.41     10048617.15
#Sta/Elev= 30
 -2898.7 1979.56 -2438.8 1975.42 -2333.9 1972.47  -636.4 1915.71    -518 1913.36
   485.8 1890.73   636.5 1884.86   787.2 1865.97   965.2 1878.11    1910 1862.48
  2595.4 1830.37  2760.8 1821.12  2959.9 1831.37    4638 1821.28  4986.6 1800.81
  5021.4  1802.4  5059.7 1823.89  5064.7 1827.18  5102.1 1850.46  5172.8 1856.48
  6114.6 1898.78    6416  1895.9  6797.2 1881.98  7164.5 1891.88  7533.7 1881.61
  8136.5 1925.49  8522.6 1964.29  9178.5 1959.37  9541.7 2005.77 10022.6 2018.29
#Mann= 10 ,-1 , 0
 -2898.7      .1       0 -2438.8     .16       0 -2333.9      .1       0
  -636.4     .05       0    -518      .1       0  2595.4     .05       0
  2760.8      .1       0    4638     .07       0  5064.7     .16       0
    6416      .1       0
Bank Sta=4638,5059.7
XS Rating Curve= 0 ,0
Exp/Cntr=0.3,0.1

Type RM Length L Ch R = 1 ,583949  ,1695,1695,1695
BEGIN DESCRIPTION:
PEDERNALES RIVER 57.0
END DESCRIPTION:
XS GIS Cut Line= 3
      2676095.93     10061377.34      2676201.59     10050336.36
      2675073.18     10048890.83
#Sta/Elev= 30
 -2344.5 1970.44 -1820.9 1954.36  -730.8 1948.98       1  1931.2   120.6 1924.11
  2849.3 1859.36  2969.3 1841.01  3329.4 1828.31  3479.4 1811.94  4109.4 1818.93
  4369.4 1803.12  4419.4 1819.58  4819.4 1816.46  4919.2 1795.79  5119.4 1801.47
  5219.5 1815.91  6469.5 1832.33  6659.5 1851.45  6737.9 1879.86  6839.5 1919.59
  6959.5  1948.8  7079.5 1965.71  7173.7 1966.78  7529.6 1964.51  7839.6 1934.15
  8089.6 1964.42  8559.6 1984.19 10026.3 1983.26 10503.3 1997.39 10530.8 1998.15
#Mann= 8 ,-1 , 0
 -2344.5      .1       0       1     .05       0   120.6      .1       0
  4819.4     .07       0  5219.5      .1       0  6737.9     .16       0
  7173.7      .1       0 10503.3     .16       0
Bank Sta=4819.4,5219.5
XS Rating Curve= 0 ,0
Exp/Cntr=0.3,0.1

Type RM Length L Ch R = 1 ,580824  ,2068,2068,2068
BEGIN DESCRIPTION:
PEDERNALES RIVER 59.0
END DESCRIPTION:
XS GIS Cut Line= 2
      2680781.58     10062275.23      2677689.53     10047862.68
#Sta/Elev= 30
 -3778.5 1997.97 -2600.6 1949.13 -2055.5 1920.06   -1641 1901.13  -851.9 1870.15
   241.9  1853.2   365.4 1844.92     672 1833.72   789.3 1858.25  2208.4 1857.62
  3920.1 1835.39  4064.4 1830.55  4865.3  1809.1  4967.3  1790.3  5269.8  1806.9
  5274.9 1807.47  6271.5 1826.41  6583.5 1860.89  6662.3 1885.68  7043.8 1968.46
  7309.7 1977.39  8618.6 1910.37  8870.2 1906.83  8984.1  1905.8  9276.6 1912.47
  9661.9 1964.64  9938.8 1974.33 10148.2 1973.37 10820.6  1987.2   10962 1988.01
#Mann= 19 ,-1 , 0
 -3778.5      .1       0 -2600.6     .05       0 -2055.5      .1       0
   -1641      .1       0   241.9     .05       0   365.4      .1       0
  2208.4      .1       0  3920.1     .16       0  4064.4      .1       0
  4865.3     .07       0  5274.9      .1       0  6662.3      .1       0
  8618.6      .1       0  8870.2     .16       0  8984.1      .1       0
  9661.9      .1       0  9938.8     .16       0 10148.2     .16       0
 10820.6      .1       0
Bank Sta=4865.3,5269.8
XS Rating Curve= 0 ,0
Exp/Cntr=0.3,0.1

Type RM Length L Ch R = 1 ,577323  ,3116,3116,3116
BEGIN DESCRIPTION:
PEDERNALES RIVER 61.0
END DESCRIPTION:
XS GIS Cut Line= 3
       2681470.6     10062005.67       2681431.5     10056553.61
      2682931.75     10047230.75
#Sta/Elev= 30
 -2936.8 1975.83 -1406.4 1954.25 -1233.1 1953.23   -74.8 1946.45   977.7  1884.5
  1111.8 1879.74  1905.3 1878.01  2697.6 1841.21  2869.8 1855.06    3042 1814.79
    3399 1802.03  3522.8 1802.55  3769.5 1797.65  3926.3 1794.34  4091.9 1804.12
  4442.6 1801.24  4796.5 1798.33  4996.5 1777.39  5199.4 1799.55    6982 1806.89
  7811.2 1853.52  8288.6 1860.15  8759.3 1841.34  8906.5 1811.81  9106.3 1829.07
  9205.2 1837.45 10236.5 1888.44 11083.4 1956.37 11921.9 1983.84 11958.2 1983.17
#Mann= 17 ,-1 , 0
 -2936.8      .1       0 -1406.4     .05       0 -1233.1      .1       0
   977.7     .05       0  1111.8      .1       0    3399     .16       0
  3522.8      .1       0  3769.5     .16       0  3926.3      .1       0
  4091.9     .05       0  4442.6      .1       0  4796.5     .07       0
  5199.4      .1       0  9106.3     .16       0  9205.2      .1       0
 10236.5     .16       0 11921.9      .1       0
Bank Sta=4796.5,5199.4
XS Rating Curve= 0 ,0
Exp/Cntr=0.3,0.1