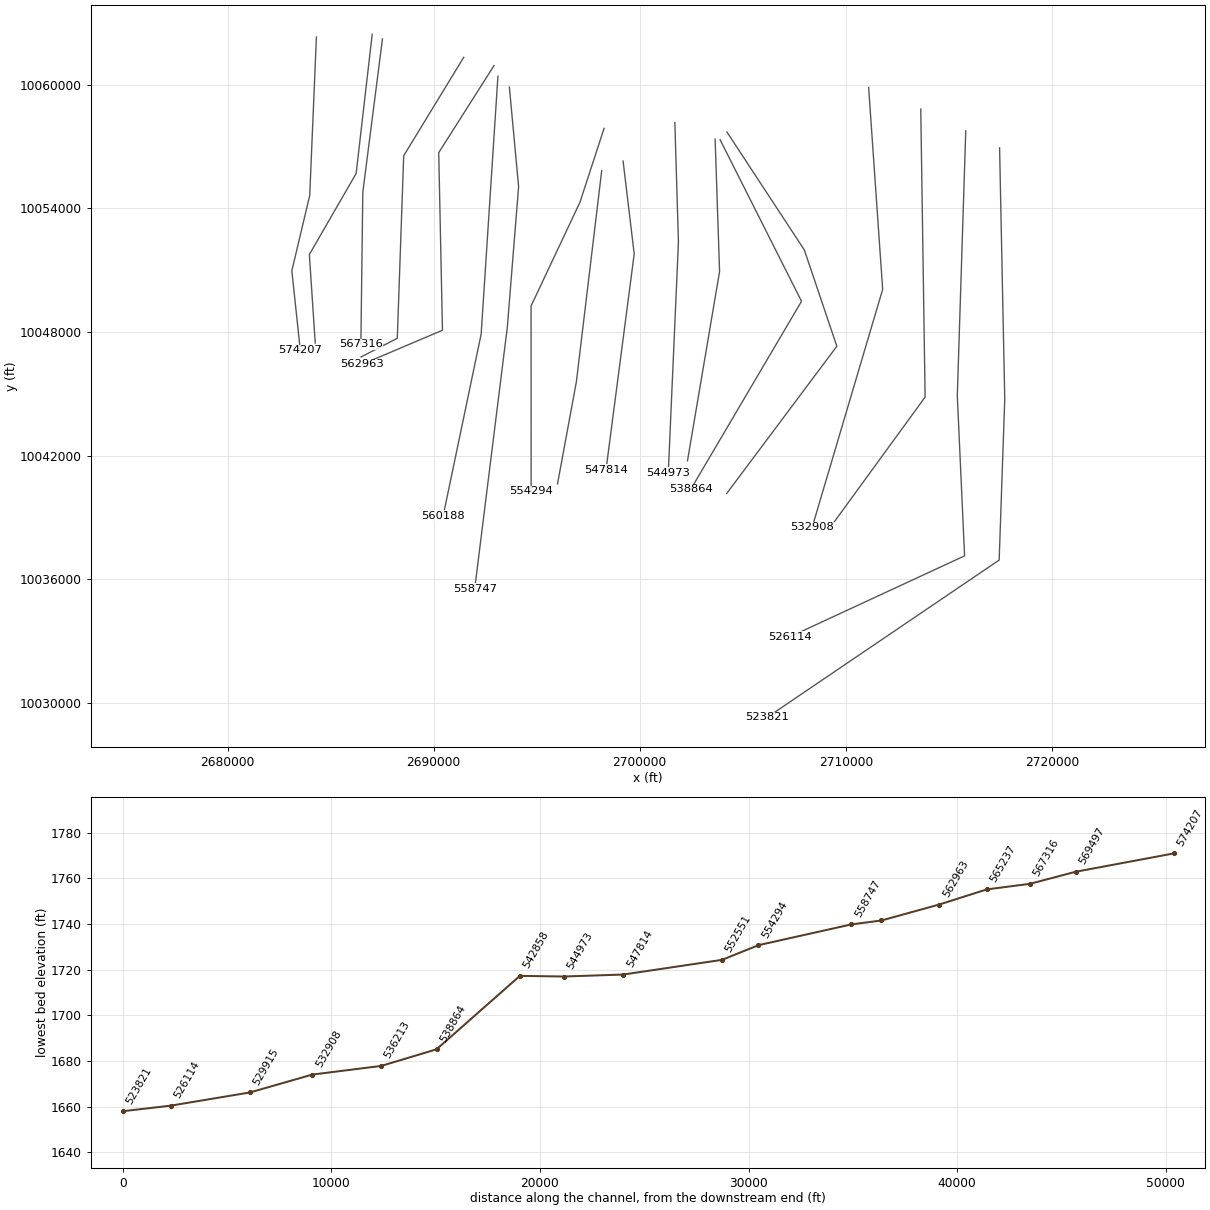
HEC-RAS study PEDERNALES RIVER.prj: PEDERNALES RIVER Base Level Engineering

--- PEDERNALES RIVER.g02 (geometry) --- (continued)

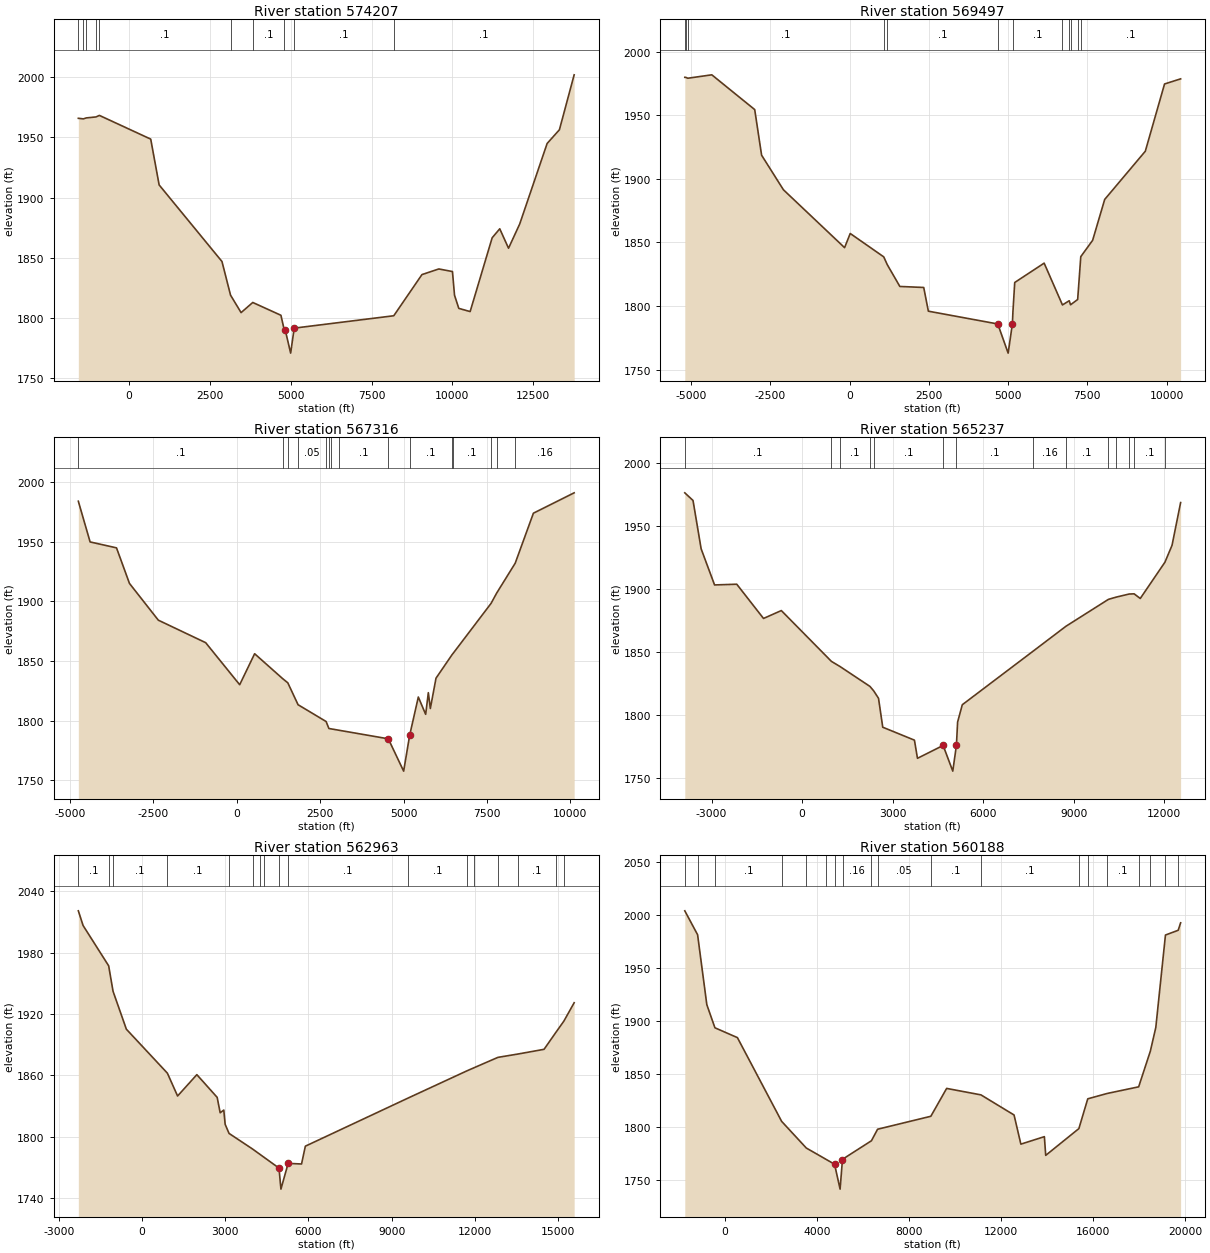
Type RM Length L Ch R = 1 ,574207  ,4710,4710,4710
BEGIN DESCRIPTION:
PEDERNALES RIVER 62.0
END DESCRIPTION:
XS GIS Cut Line= 4
      2684314.31     10062308.73      2683989.41     10054622.24
      2683121.55     10050965.85        2683532.      10047117.5
#Sta/Elev= 30
 -1560.1 1965.71 -1403.6 1965.23 -1314.7 1966.03 -1015.2 1966.84    -909 1968.11
   676.9 1948.45   937.1 1910.44  2878.9 1846.91  3143.3 1819.03  3469.4 1804.54
  3830.2 1812.94  4700.5 1802.33  4810.6 1789.28  4830.6 1790.47  5000.5 1770.93
  5110.9 1791.66  8187.3 1801.93    9058 1836.06  9579.9 1840.75 10001.2 1838.59
 10064.3 1819.01 10196.1 1808.06   10547 1805.39 11227.6 1866.59 11462.2 1874.07
 11733.7 1857.94 12079.3 1878.07   12926 1944.81 13305.7  1956.2 13761.4 2001.77
#Mann= 10 ,-1 , 0
 -1560.1      .1       0 -1403.6     .16       0 -1314.7      .1       0
 -1015.2     .16       0    -909      .1       0  3143.3     .05       0
  3830.2      .1       0  4810.6     .07       0  5110.9      .1       0
  8187.3      .1       0
Bank Sta=4830.6,5110.9
XS Rating Curve= 0 ,0
Exp/Cntr=0.3,0.1

Type RM Length L Ch R = 1 ,569497  ,2181,2181,2181
BEGIN DESCRIPTION:
PEDERNALES RIVER 63.0
END DESCRIPTION:
XS GIS Cut Line= 4
      2687021.13     10062445.25      2686242.39     10055690.86
      2683971.53     10051757.29      2684257.18     10047463.61
#Sta/Elev= 30
 -5200.5 1979.81 -5164.5 1979.76 -5105.7  1979.1 -4348.1 1981.78 -2994.5 1954.44
 -2777.2 1918.56 -2088.5 1891.37  -158.9 1845.84      19 1856.98  1077.2 1838.59
  1187.1 1832.51  1584.9 1815.32  2338.3 1814.52  2484.4 1795.87  4674.6 1785.81
  5001.8 1762.88  5136.2 1785.92  5151.3 1794.76  5209.5 1818.45  6137.9 1833.66
    6715 1800.79  6929.4 1804.08  6970.2 1800.89  7195.4 1805.07  7293.7 1838.75
  7667.6 1851.62  8048.4 1883.77  9329.8 1921.69  9936.7 1974.59 10443.8  1978.6
#Mann= 12 ,-1 , 0
 -5200.5      .1       0 -5164.5     .16       0 -5105.7      .1       0
  1077.2     .05       0  1187.1      .1       0  4674.6     .07       0
  5151.3      .1       0    6715     .05       0  6929.4     .16       0
  6970.2     .05       0  7195.4     .16       0  7293.7      .1       0
Bank Sta=4674.6,5136.2
XS Rating Curve= 0 ,0
Exp/Cntr=0.3,0.1

Type RM Length L Ch R = 1 ,567316  ,2079,2079,2079
BEGIN DESCRIPTION:
PEDERNALES RIVER 64.0
END DESCRIPTION:
XS GIS Cut Line= 3
      2687518.67     10062216.83      2686565.74     10054783.22
      2686471.48     10047411.86
#Sta/Elev= 30
 -4753.5  1983.8 -4400.3 1949.68 -3608.8 1944.72 -3220.6 1914.93 -2354.6 1884.11
    -936 1865.27    84.4 1830.02   532.5 1855.99  1375.7 1835.05  1526.9 1831.64
  1835.2 1813.25  2675.4 1799.19    2759 1793.33  2835.7 1792.96  3058.8 1791.88
  4540.6 1784.69  5000.4 1757.61  5180.6 1787.57  5440.6 1819.71  5660.7 1805.19
  5740.7 1823.36  5800.7  1810.1  5970.7 1835.49  6455.2 1855.31  6483.4 1856.28
  7622.8 1898.24  7788.7 1906.77  8345.7 1931.88  8890.9 1973.76 10112.9 1990.84
#Mann= 15 ,-1 , 0
 -4753.5      .1       0  1375.7     .05       0  1526.9      .1       0
  1835.2     .05       0  2675.4     .16       0    2759      .1       0
  2835.7     .16       0  3058.8      .1       0  4540.6     .07       0
  5180.6      .1       0  6455.2     .16       0  6483.4      .1       0
  7622.8     .05       0  7788.7      .1       0  8345.7     .16       0
Bank Sta=4540.6,5180.6
XS Rating Curve= 0 ,0
Exp/Cntr=0.3,0.1

Type RM Length L Ch R = 1 ,565237  ,2274,2274,2274
BEGIN DESCRIPTION:
PEDERNALES RIVER 65.0
END DESCRIPTION:
XS GIS Cut Line= 4
      2691461.75     10061326.37      2688549.92      10056551.8
      2688239.06     10047693.44       2686480.7     10046787.85
#Sta/Elev= 30
 -3887.5 1976.39   -3615 1970.31 -3345.6 1931.85 -2900.5 1903.16 -2165.4 1903.74
 -1278.5 1876.52    -688 1882.79   973.5 1842.37    1253 1838.37  2248.7 1822.51
  2374.6 1818.92  2533.5 1813.04  2673.6 1790.06  3724.2 1779.77  3824.3 1765.33
  4674.8 1775.57  4994.8 1755.15  5115.1 1775.56  5155.1 1794.19  5310.4 1807.93
    7665 1850.65  8745.2  1870.3 10153.8  1891.7 10401.5 1893.42 10839.5 1895.94
 11005.7 1896.09 11208.7  1892.4 12026.9 1921.25 12261.5 1934.62 12546.6 1968.64
#Mann= 14 ,-1 , 0
 -3887.5      .1       0   973.5     .05       0    1253      .1       0
  2248.7     .05       0  2374.6      .1       0  4674.8     .07       0
  5115.1      .1       0    7665     .16       0  8745.2      .1       0
 10153.8     .16       0 10401.5      .1       0 10839.5     .05       0
 11005.7      .1       0 12026.9     .16       0
Bank Sta=4674.8,5115.1
XS Rating Curve= 0 ,0
Exp/Cntr=0.3,0.1

Type RM Length L Ch R = 1 ,562963  ,2775,2775,2775
BEGIN DESCRIPTION:
PEDERNALES RIVER 66.0
END DESCRIPTION:
XS GIS Cut Line= 4
       2692933.6     10060927.29       2690249.6     10056702.32
       2690430.7     10048084.23      2686518.05     10046422.82
#Sta/Elev= 30
 -2296.5 2020.94 -2124.4 2006.54 -1202.6 1967.11 -1044.8 1942.19  -565.2 1905.09
   914.5 1862.03    1282 1839.67  1976.5 1860.58  2708.9 1838.36  2817.5 1823.27
  2947.6  1825.9  2997.6  1811.9  3137.5 1803.07  3983.2 1787.83  4248.6 1782.63
  4398.2  1779.7    4938 1769.14  5007.8 1748.53    5268 1773.75  5751.1 1773.13
  5888.2 1790.56  9597.2 1837.73 11723.1 1864.42 11986.2 1867.53 12830.6  1877.5
 13544.9 1880.73 14494.1 1885.37 14910.7 1901.57 15208.5 1912.96 15579.7 1930.97
#Mann= 17 ,-1 , 0
 -2296.5      .1       0 -1202.6     .16       0 -1044.8      .1       0
   914.5      .1       0  3137.5      .1       0  3983.2      .1       0
  4248.6     .05       0  4398.2      .1       0    4938     .07       0
    5268      .1       0  9597.2      .1       0 11723.1     .16       0
 11986.2     .16       0 12830.6      .1       0 13544.9      .1       0
 14910.7     .16       0 15208.5      .1       0
Bank Sta=4938,5268
XS Rating Curve= 0 ,0
Exp/Cntr=0.3,0.1

Type RM Length L Ch R = 1 ,560188  ,1441,1441,1441
BEGIN DESCRIPTION:
PEDERNALES RIVER 67.0
END DESCRIPTION:
XS GIS Cut Line= 3
      2693122.11     10060408.73      2692308.03     10047898.31
      2690464.12     10039078.07
#Sta/Elev= 30
 -1739.2 2004.03 -1182.7 1981.49  -782.2 1915.55  -429.8 1893.71   547.7 1884.43
  2469.2 1805.46  3540.3 1780.31  4378.7 1769.88  4769.5 1765.02  5009.8 1741.53
  5110.3 1768.91  5120.3 1769.76  6372.9 1787.18  6638.9 1798.02  8953.6 1810.25
  9640.4 1836.53   11131 1830.43 12569.8 1811.46   12866 1783.96 13887.6 1791.03
 13945.7 1773.38 15386.9 1798.62 15773.1 1826.71 16620.5 1831.78 17984.9 1838.02
   18493 1871.68 18730.1 1894.01 19149.6  1981.2 19702.4 1985.67 19808.6  1992.7
#Mann= 19 ,-1 , 0
 -1739.2      .1       0 -1182.7      .1       0  -429.8      .1       0
  2469.2      .1       0  3540.3     .05       0  4378.7      .1       0
  4769.5     .07       0  5120.3     .16       0  6372.9      .1       0
  6638.9     .05       0  8953.6      .1       0   11131      .1       0
 15386.9     .16       0 15773.1      .1       0 16620.5      .1       0
 17984.9     .05       0   18493     .16       0 19149.6      .1       0
 19702.4     .16       0
Bank Sta=4769.5,5110.3
XS Rating Curve= 0 ,0
Exp/Cntr=0.3,0.1

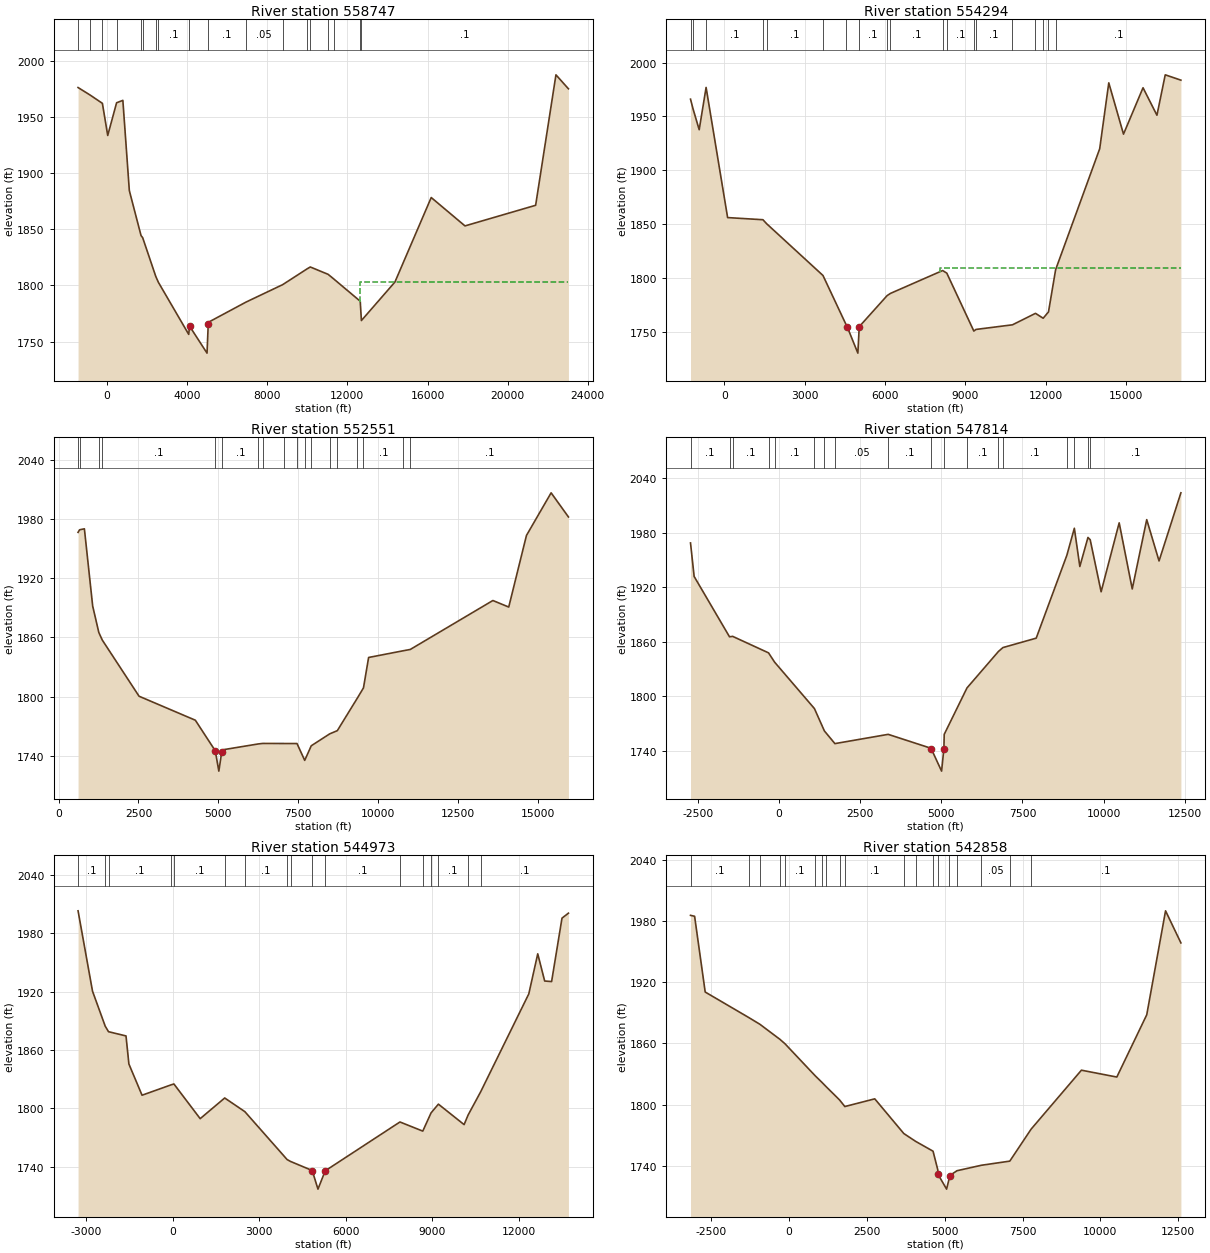
Type RM Length L Ch R = 1 ,558747  ,4453,4453,4453
BEGIN DESCRIPTION:
PEDERNALES RIVER 68.0
END DESCRIPTION:
XS GIS Cut Line= 4
      2693676.89     10059885.24      2694125.32     10055050.97
      2693577.48      10048229.8      2691996.42     10035549.54
#Sta/Elev= 30
 -1443.2 1976.19  -846.9 1969.57  -228.2 1962.12    37.6 1933.54     480 1962.63
   793.1 1964.76  1116.2 1884.44  1700.6 1844.42  1780.9 1842.62  2435.9 1808.08
  2566.5 1802.84  4081.2 1756.48  4121.3 1763.85  4993.9 1739.81    5054 1765.37
  5064.4  1767.3  6937.1 1785.21  8767.2 1800.73  9989.9 1814.81 10148.7 1816.48
 11037.2 1809.94 11307.5    1806 12640.7 1786.01 12699.6  1768.8 14372.7 1803.08
 16184.5  1878.3 17869.5 1853.04 21396.6 1871.39   22410  1987.5 23033.4 1975.06
#Mann= 18 ,-1 , 0
 -1443.2      .1       0  -846.9     .16       0  -228.2     .16       0
     480      .1       0  1700.6     .16       0  1780.9      .1       0
  2435.9     .05       0  2566.5      .1       0  4081.2     .07       0
  5064.4      .1       0  6937.1     .05       0  8767.2      .1       0
  9989.9     .05       0 10148.7      .1       0 11037.2     .16       0
 11307.5      .1       0 12640.7     .16       0 12699.6      .1       0
#XS Ineff= 2 , 0
                        12642.05         1802.88
Permanent Ineff=
       F       F
Bank Sta=4121.3,5054
XS Rating Curve= 0 ,0
Exp/Cntr=0.3,0.1

Type RM Length L Ch R = 1 ,554294  ,1743,1743,1743
BEGIN DESCRIPTION:
PEDERNALES RIVER 69.0
END DESCRIPTION:
XS GIS Cut Line= 4
      2698272.83     10057880.77      2697100.42     10054290.14
      2694729.86     10049261.53       2694733.2     10040268.29
#Sta/Elev= 30
   -1270 1966.04 -1176.1 1957.09  -945.8 1937.73  -687.6  1976.9     117 1856.31
  1437.7 1854.32  1572.9 1850.67  3681.4 1802.66  4558.9 1756.36  4587.2 1755.09
  4985.3 1730.71  5036.6 1755.23    6079 1784.01  6202.9 1786.05  8153.8 1807.24
  8309.4 1804.84  9320.1 1751.17  9399.7 1752.66 10763.9 1756.94 11624.8 1767.57
 11911.5 1763.05 12110.7 1768.89   12378 1808.08 14024.4 1920.05 14364.4 1981.16
 14914.4 1933.63 15644.4 1976.61 16164.4 1951.15 16474.4 1988.59 17059.8 1983.66
#Mann= 19 ,-1 , 0
   -1270      .1       0 -1176.1     .16       0  -687.6      .1       0
  1437.7     .05       0  1572.9      .1       0  3681.4      .1       0
  4558.9     .07       0  5036.6      .1       0    6079     .05       0
  6202.9      .1       0  8153.8     .05       0  8309.4      .1       0
  9320.1     .16       0  9399.7      .1       0 10763.9     .16       0
 11624.8      .1       0 11911.5     .16       0 12110.7     .16       0
   12378      .1       0
#XS Ineff= 2 , 0
                         8068.18         1810.01
Permanent Ineff=
       F       F
Bank Sta=4587.2,5036.6
XS Rating Curve= 0 ,0
Exp/Cntr=0.3,0.1

Type RM Length L Ch R = 1 ,552551  ,4737,4737,4737
BEGIN DESCRIPTION:
PEDERNALES RIVER 70.0
END DESCRIPTION:
XS GIS Cut Line= 3
      2698158.44     10055830.66      2696926.87     10045572.29
      2696013.68     10040630.49
#Sta/Elev= 30
   607.5 1966.79     656 1969.38   805.8 1970.39  1065.7 1891.87  1257.9 1865.07
  1367.2 1857.35    2518 1800.35  4280.6 1775.99  4905.1 1744.93    5016 1724.28
  5106.5 1743.62  5126.6 1745.88  6254.9 1751.91  6392.9  1752.4  7067.3 1752.33
  7464.5 1752.28  7706.1  1735.2  7910.2 1750.01  8488.3 1762.13    8727 1765.38
  9355.5 1798.51  9546.1 1808.82    9707 1839.71 10791.2 1846.52 11012.6 1847.86
 13598.6 1897.56 14095.4 1890.92 14650.2 1963.64 15422.7 2006.93   15965 1982.44
#Mann= 18 ,-1 , 0
   607.5     .16       0     656      .1       0  1257.9     .05       0
  1367.2      .1       0  4905.1     .07       0  5126.6      .1       0
  6254.9     .05       0  6392.9      .1       0  7067.3      .1       0
  7464.5     .05       0  7706.1     .05       0  7910.2      .1       0
  8488.3     .05       0    8727      .1       0  9355.5     .05       0
  9546.1      .1       0 10791.2     .05       0 11012.6      .1       0
Bank Sta=4905.1,5106.5
XS Rating Curve= 0 ,0
Exp/Cntr=0.3,0.1

Type RM Length L Ch R = 1 ,547814  ,2841,2841,2841
BEGIN DESCRIPTION:
PEDERNALES RIVER 71.0
END DESCRIPTION:
XS GIS Cut Line= 3
      2699194.61     10056294.47      2699734.67     10051786.79
      2698366.75      10041318.6
#Sta/Elev= 30
 -2719.8 1968.78 -2608.3 1931.94 -1519.3 1865.57 -1422.2 1866.05  -317.6  1847.9
  -130.1 1837.65  1094.7 1786.65    1402 1762.03  1725.7  1748.1  3365.7 1758.28
  4677.3 1743.06  4688.7 1742.67  5009.8 1717.84  5080.7 1742.51  5090.7 1758.24
  5791.4 1809.32  6759.7 1849.41  6897.9 1853.72    7923 1864.08  8866.3  1955.2
    9097 1984.92  9265.9 1942.89    9516  1974.8  9584.6 1972.35  9921.5  1915.1
 10477.2  1990.9 10879.5 1918.17 11325.3 1994.41 11704.8 1948.99 12377.3  2023.9
#Mann= 18 ,-1 , 0
 -2719.8      .1       0 -1519.3     .05       0 -1422.2      .1       0
  -317.6     .05       0  -130.1      .1       0  1094.7     .16       0
    1402      .1       0  1725.7     .05       0  3365.7      .1       0
  4677.3     .07       0  5090.7     .16       0  5791.4      .1       0
  6759.7     .05       0  6897.9      .1       0  8866.3     .16       0
    9097      .1       0    9516     .16       0  9584.6      .1       0
Bank Sta=4688.7,5080.7
XS Rating Curve= 0 ,0
Exp/Cntr=0.3,0.1

Type RM Length L Ch R = 1 ,544973  ,2115,2115,2115
BEGIN DESCRIPTION:
PEDERNALES RIVER 72.0
END DESCRIPTION:
XS GIS Cut Line= 3
      2701707.08      10058164.9      2701880.61     10052368.05
      2701389.41     10041180.88
#Sta/Elev= 30
 -3279.7 2003.14 -2778.3 1920.48 -2338.3 1884.54 -2224.1 1878.85 -1617.8 1874.51
 -1517.7 1845.65 -1061.8 1813.54     -64 1824.11    42.2 1825.11   953.4 1789.43
  1803.8 1810.69  2501.5 1796.66  3967.4 1747.36  4087.1 1745.42  4836.3 1736.12
  5036.2 1716.98  5286.7 1735.79  7876.9 1786.02  8668.8 1776.63  8955.9 1795.36
  9210.4 1804.36 10101.4 1783.32 10239.2 1793.13 10675.5 1817.06 12343.5 1917.71
 12653.8 1958.94 12894.1 1930.97 13134.3 1930.41 13494.6 1995.64 13717.7 2000.73
#Mann= 17 ,-1 , 0
 -3279.7      .1       0 -2338.3     .05       0 -2224.1      .1       0
     -64     .05       0    42.2      .1       0  1803.8     .05       0
  2501.5      .1       0  3967.4     .05       0  4087.1      .1       0
  4836.3     .07       0  5286.7      .1       0  7876.9     .05       0
  8668.8     .16       0  8955.9     .05       0  9210.4      .1       0
 10239.2     .16       0 10675.5      .1       0
Bank Sta=4836.3,5286.7
XS Rating Curve= 0 ,0
Exp/Cntr=0.3,0.1

Type RM Length L Ch R = 1 ,542858  ,3994,3994,3994
BEGIN DESCRIPTION:
PEDERNALES RIVER 77.0
END DESCRIPTION:
XS GIS Cut Line= 3
      2703661.31     10057354.89      2703877.05     10050933.53
      2702320.29     10041748.21
#Sta/Elev= 30
 -3158.7 1985.38 -3027.5 1984.48 -2687.3 1910.29 -1289.3  1885.3  -930.9 1878.69
  -283.8 1863.85  -125.6  1859.6   845.2 1828.21  1058.4 1821.87  1194.6  1817.6
  1626.2  1804.6  1794.3 1798.14  2755.8 1805.67  3687.7 1771.71  4067.6 1764.03
  4626.5 1754.41  4777.3 1736.37  4783.1 1731.93  5061.1 1717.25  5145.2 1727.73
  5162.8 1730.58  5396.5 1735.28  6174.6  1740.6  7090.7 1744.68  7776.1 1776.05
  9389.5 1833.74   10526 1827.02 11486.5    1888 12090.2 1989.81 12582.6 1958.41
#Mann= 19 ,-1 , 0
 -3158.7      .1       0 -1289.3     .05       0  -930.9      .1       0
  -283.8     .05       0  -125.6      .1       0   845.2     .05       0
  1058.4      .1       0  1194.6     .05       0  1626.2     .05       0
  1794.3      .1       0  3687.7     .05       0  4067.6      .1       0
  4626.5      .1       0  4777.3     .07       0  5145.2      .1       0
  5396.5      .1       0  6174.6     .05       0  7090.7      .1       0
  7776.1      .1       0
Bank Sta=4783.1,5162.8
XS Rating Curve= 0 ,0
Exp/Cntr=0.3,0.1

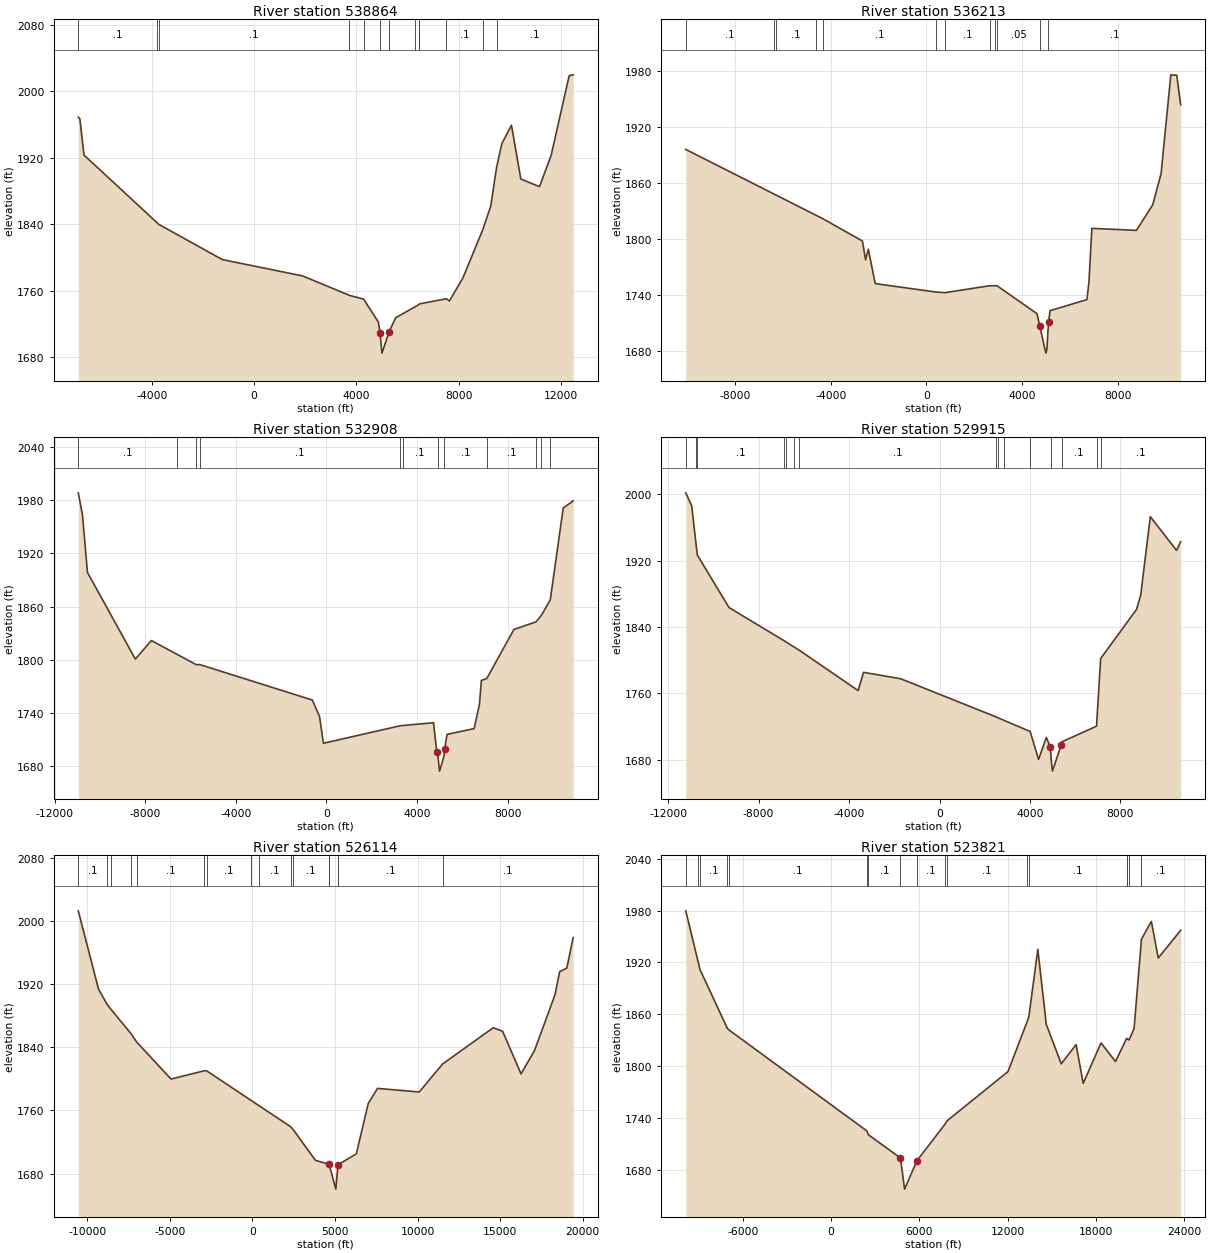
Type RM Length L Ch R = 1 ,538864  ,2651,2651,2651
BEGIN DESCRIPTION:
PEDERNALES RIVER 78.0
END DESCRIPTION:
XS GIS Cut Line= 3
      2703904.78     10057323.04      2707852.92     10049487.98
       2702475.7     10040360.54
#Sta/Elev= 30
 -6883.3 1968.98   -6821 1966.88 -6659.3 1923.28 -3813.7 1842.32 -3736.1    1840
 -1243.9 1797.56  1895.7 1777.94  3725.1 1754.58  4283.4 1750.03  4862.3 1722.26
  4926.7 1708.71  5000.7 1685.07  5278.1 1710.76  5539.6  1727.7  6290.6 1740.72
  6430.9 1743.16    6469  1744.3  7523.6 1750.47  7638.2 1747.76  8162.6 1775.09
    8944 1833.36  9258.4 1861.83  9487.9  1908.7  9689.8 1936.76 10068.5 1959.26
 10435.5 1894.52 11165.6 1885.28 11624.3 1923.19 12327.1 2018.83 12483.9 2019.83
#Mann= 13 ,-1 , 0
 -6883.3      .1       0 -3813.7     .05       0 -3736.1      .1       0
  3725.1     .05       0  4283.4      .1       0  4926.7     .07       0
  5278.1      .1       0  6290.6     .05       0  6430.9      .1       0
    6469     .05       0  7523.6      .1       0    8944     .16       0
  9487.9      .1       0
Bank Sta=4926.7,5278.1
XS Rating Curve= 0 ,0
Exp/Cntr=0.3,0.1

Type RM Length L Ch R = 1 ,536213  ,3305,3305,3305
BEGIN DESCRIPTION:
PEDERNALES RIVER 79.0
END DESCRIPTION:
XS GIS Cut Line= 4
      2704233.99      10057703.2      2707991.98     10051975.31
      2709567.07      10047306.4      2704227.35     10040168.04
#Sta/Elev= 30
-10062.9 1896.06 -6380.1 1848.36 -6281.1 1847.08 -4617.5 1825.53 -4325.3 1821.75
 -2676.7 1797.92 -2545.6  1777.8 -2430.2 1789.25 -2141.7 1752.29   397.9 1743.26
     775  1742.6  2651.9 1750.03  2860.3 1749.99  2953.1 1749.97    4624 1720.05
  4738.7 1706.77  4994.8 1677.79  5038.8 1682.58    5087 1704.01  5109.6 1711.03
  5165.9 1723.24  6710.2 1735.14  6795.7 1754.38  6916.6 1811.49  8781.8 1809.34
  9461.2 1836.69  9810.9 1870.13 10217.8 1976.02 10467.9 1975.52 10629.7 1943.96
#Mann= 12 ,-1 , 0
-10062.9      .1       0 -6380.1     .05       0 -6281.1      .1       0
 -4617.5     .05       0 -4325.3      .1       0   397.9     .05       0
     775      .1       0  2651.9     .05       0  2860.3      .1       0
  2953.1     .05       0  4738.7     .07       0    5087      .1       0
Bank Sta=4738.7,5109.6
XS Rating Curve= 0 ,0
Exp/Cntr=0.3,0.1

Type RM Length L Ch R = 1 ,532908  ,2993,2993,2993
BEGIN DESCRIPTION:
PEDERNALES RIVER 88.0
END DESCRIPTION:
XS GIS Cut Line= 3
      2711109.42     10059868.93      2711791.08     10050067.58
      2708370.05     10038524.07
#Sta/Elev= 30
-10964.1 1988.56-10778.5 1963.53-10557.9 1898.54 -8442.8 1800.63 -7735.5 1821.61
 -6592.1 1805.89 -5745.3 1794.25 -5604.8 1794.48  -624.4 1754.36  -304.3 1735.67
  -133.8 1705.48  3259.2 1725.26  3371.3 1725.52  4730.8 1728.69  4874.2 1695.85
  4914.3 1693.55  4997.5 1673.99  5195.9 1691.02  5222.3 1698.51  5327.2 1715.52
  6525.2 1722.06  6760.4 1749.57  6845.2  1776.5  7083.1 1778.65  8281.1 1834.09
  9258.5 1842.71    9486 1849.73  9888.8 1867.56 10462.1 1971.42 10900.7 1979.48
#Mann= 12 ,-1 , 0
-10964.1      .1       0 -6592.1      .1       0 -5745.3     .05       0
 -5604.8      .1       0  3259.2     .05       0  3371.3      .1       0
  4914.3     .07       0  5195.9      .1       0  7083.1      .1       0
  9258.5     .16       0    9486      .1       0  9888.8      .1       0
Bank Sta=4874.2,5222.3
XS Rating Curve= 0 ,0
Exp/Cntr=0.3,0.1

Type RM Length L Ch R = 1 ,529915  ,3801,3801,3801
BEGIN DESCRIPTION:
PEDERNALES RIVER 89.0
END DESCRIPTION:
XS GIS Cut Line= 3
      2713639.53     10058814.15      2713850.36     10044840.19
      2709196.26     10038447.95
#Sta/Elev= 30
  -11221 2001.98-10957.8 1986.09-10774.5 1941.95-10712.6 1927.05 -9310.4 1863.57
 -6867.6 1823.39 -6780.5  1821.9 -6452.5  1816.3 -6210.9 1812.18 -3599.7 1763.36
 -3359.7 1785.36 -1719.5 1777.62  2473.9 1731.86    2575 1730.66  2851.8 1727.39
  4006.9 1714.02  4378.5 1680.23  4721.6 1706.76  4901.6 1694.94  4943.4 1677.67
  4993.3 1666.15  5380.7 1698.08  5401.6 1701.41  6940.6 1720.37  7124.3 1802.02
  8709.4 1861.22  8895.6 1878.54  9318.3 1973.23 10477.3  1932.6 10661.6 1942.86
#Mann= 15 ,-1 , 0
  -11221      .1       0-10774.5     .16       0-10712.6      .1       0
 -6867.6     .05       0 -6780.5      .1       0 -6452.5     .05       0
 -6210.9      .1       0  2473.9     .05       0    2575      .1       0
  2851.8     .05       0  4006.9      .1       0  4943.4     .07       0
  5401.6      .1       0  6940.6     .16       0  7124.3      .1       0
Bank Sta=4901.6,5380.7
XS Rating Curve= 0 ,0
Exp/Cntr=0.3,0.1

Type RM Length L Ch R = 1 ,526114  ,2293,2293,2293
BEGIN DESCRIPTION:
PEDERNALES RIVER 100.0
END DESCRIPTION:
XS GIS Cut Line= 4
      2715822.46     10057755.21      2715412.22     10044902.31
      2715765.71     10037136.89      2707305.06     10033215.81
#Sta/Elev= 30
-10540.7 2012.96   -9316 1913.77 -8804.1 1894.67 -8548.1 1887.76 -7363.7 1857.76
 -7001.9 1846.66 -4925.7  1799.8 -2909.7 1810.35 -2770.3 1810.28  -105.6 1773.15
   425.3 1765.75  2318.3 1739.38  2480.7 1735.45  3818.9 1696.74  4640.1 1692.03
  5049.9 1660.37  5179.9 1691.25  6291.4 1705.08  7012.2 1768.85  7572.8 1787.99
 10100.2 1783.44 11508.9 1818.84 14581.6 1864.88   15148 1860.32 16261.3 1806.36
 17075.6 1835.84 18316.6 1906.58 18597.1 1935.85 19031.6 1940.42 19417.3 1979.07
#Mann= 15 ,-1 , 0
-10540.7      .1       0 -8804.1     .05       0 -8548.1      .1       0
 -7363.7     .05       0 -7001.9      .1       0 -2909.7     .05       0
 -2770.3      .1       0  -105.6     .05       0   425.3      .1       0
  2318.3     .05       0  2480.7      .1       0  4640.1     .05       0
  4640.1     .07       0  5179.9      .1       0 11508.9      .1       0
Bank Sta=4640.1,5179.9
XS Rating Curve= 0 ,0
Exp/Cntr=0.3,0.1

Type RM Length L Ch R = 1 ,523821  ,2110,2110,2110
BEGIN DESCRIPTION:
PEDERNALES RIVER 101.0
END DESCRIPTION:
XS GIS Cut Line= 4
      2717464.34     10056932.82      2717714.57      10044747.6
      2717443.65     10036931.29      2706180.05     10029295.79
#Sta/Elev= 30
   -9875 1979.63 -9064.8 1922.75 -8905.1 1911.54 -7044.7  1843.6 -6934.5 1841.86
  2422.3 1725.28  2528.5 1720.83  4708.1 1693.91    4988 1657.93  5822.4 1690.65
  7752.2 1733.43  7876.7 1736.96 12014.1 1793.82 13310.8 1851.48 13433.5 1857.65
 14038.8 1935.13 14613.8 1848.31 15629.2 1802.84 16638.5 1824.99 17120.7 1780.19
 18330.7 1826.89 19316.1 1805.42   20072 1832.18 20076.1 1832.13 20239.6 1830.35
   20577 1843.61 21079.3 1946.86   21750 1967.43 22218.3 1925.09 23741.5 1957.11
#Mann= 17 ,-1 , 0
   -9875      .1       0 -9064.8     .05       0 -8905.1      .1       0
 -7044.7     .05       0 -6934.5      .1       0  2422.3     .05       0
  2528.5      .1       0  4708.1     .07       0  5822.4      .1       0
  7752.2     .16       0  7876.7      .1       0 13310.8     .05       0
 13433.5      .1       0   20072     .05       0 20076.1      .1       0
 20239.6     .16       0 21079.3      .1       0
Bank Sta=4708.1,5822.4
XS Rating Curve= 0 ,0
Exp/Cntr=0.3,0.1