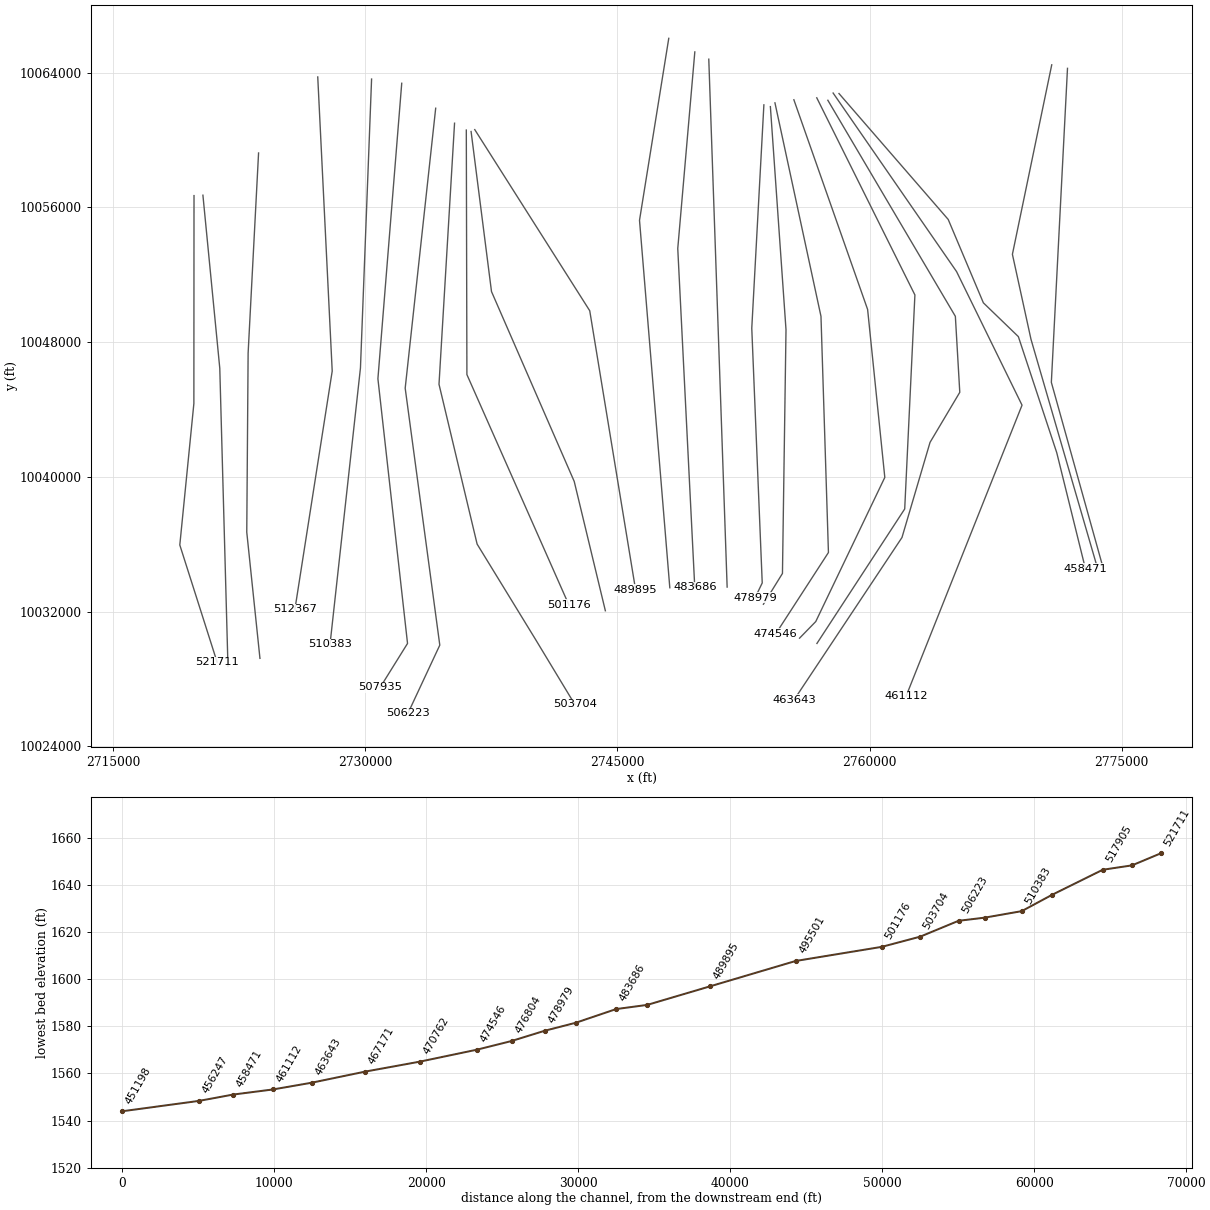
HEC-RAS study PEDERNALES RIVER.prj: PEDERNALES RIVER Base Level Engineering

--- PEDERNALES RIVER.g02 (geometry) --- (continued)

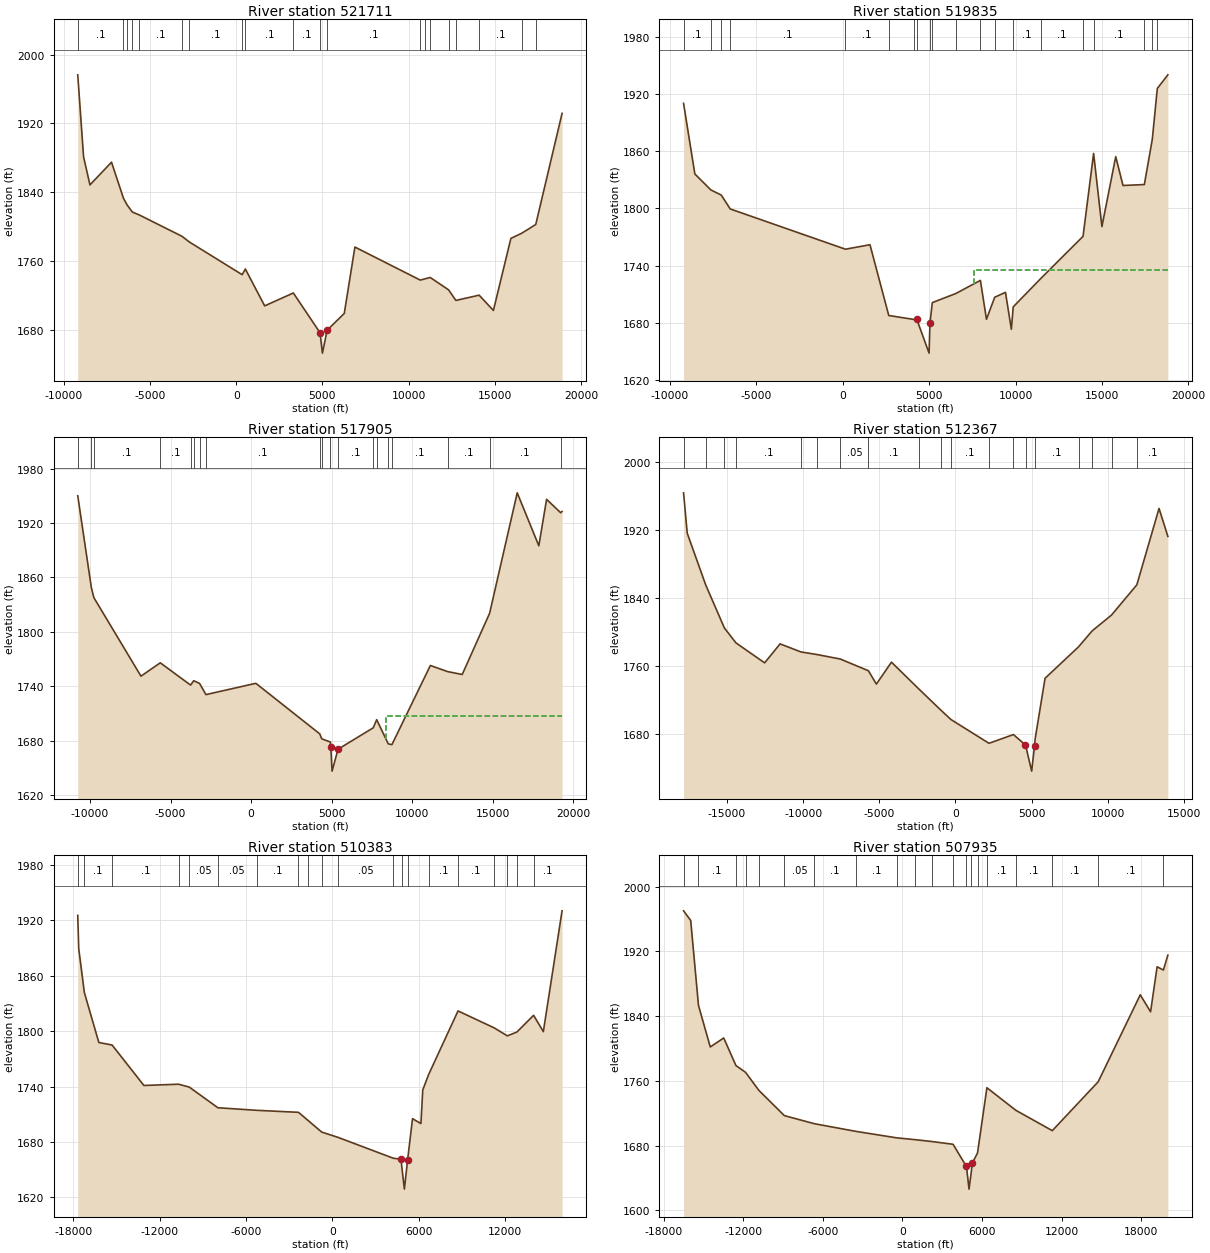
Type RM Length L Ch R = 1 ,521711  ,1876,1876,1876
BEGIN DESCRIPTION:
PEDERNALES RIVER 102.0
END DESCRIPTION:
XS GIS Cut Line= 4
      2719810.99      10056700.5      2719802.73     10044355.93
      2718965.82     10035959.88      2721184.46     10029007.74
#Sta/Elev= 30
 -9185.7 1976.47 -8848.9 1881.34 -8478.9 1848.69 -7228.9 1875.05 -6537.1 1833.27
 -6321.8 1825.38   -6022 1817.17 -5627.3 1813.88 -3145.1 1789.05 -2718.9 1782.44
   344.9 1744.46   531.8    1751  1651.1 1708.23  3313.9  1723.2  4859.5  1677.1
  4999.9 1653.38  5272.6 1680.01  6266.4 1699.43  6883.1 1776.53 10670.8 1738.17
 10930.8 1739.54 11249.6 1741.22 12314.5 1726.84 12737.5 1714.55 14084.9 1720.66
 14912.8 1702.92 15926.5 1786.57 16554.6 1792.55 17368.1 1802.73 18894.1 1931.76
#Mann= 20 ,-1 , 0
 -9185.7      .1       0 -6537.1     .05       0 -6321.8     .16       0
   -6022     .16       0 -5627.3      .1       0 -3145.1     .05       0
 -2718.9      .1       0   344.9      .1       0   531.8      .1       0
  3313.9      .1       0  4859.5     .07       0  5272.6      .1       0
 10670.8     .05       0 10930.8      .1       0 11249.6     .05       0
 12314.5      .1       0 12737.5     .05       0 14084.9      .1       0
 16554.6     .05       0 17368.1      .1       0
Bank Sta=4859.5,5272.6
XS Rating Curve= 0 ,0
Exp/Cntr=0.3,0.1

Type RM Length L Ch R = 1 ,519835  ,1930,1930,1930
BEGIN DESCRIPTION:
PEDERNALES RIVER 103.0
END DESCRIPTION:
XS GIS Cut Line= 3
       2720340.6     10056724.81      2721343.85     10046451.21
      2721831.15     10028747.18
#Sta/Elev= 30
 -9214.3 1910.01 -8560.1 1836.03 -7636.1 1819.32 -7033.4 1813.94 -6513.1 1799.38
   157.2 1757.19  1575.8 1761.89  2663.3 1687.73  4146.8 1683.52  4286.9 1683.64
  4996.9 1648.31  5047.1 1679.81  5184.4 1701.23  6534.3 1710.68  7967.8 1724.51
  8318.4 1683.77  8795.3 1706.86  9418.8 1712.01  9758.9 1673.34  9866.2 1696.74
 11468.9 1726.62 13909.2 1770.68 14520.2 1857.53 15000.9 1780.87 15801.2 1854.18
 16221.4 1823.95 17457.3 1824.95 17917.4 1872.38   18208 1925.62 18818.9  1939.9
#Mann= 20 ,-1 , 0
 -9214.3      .1       0 -7636.1     .05       0 -7033.4      .1       0
 -6513.1      .1       0   157.2      .1       0  2663.3     .05       0
  4146.8      .1       0  4286.9     .07       0  5047.1      .1       0
  5184.4      .1       0  6534.3      .1       0  7967.8     .16       0
  8795.3      .1       0  9866.2      .1       0 11468.9      .1       0
 13909.2      .1       0 14520.2      .1       0 17457.3      .1       0
 17917.4     .16       0   18208      .1       0
#XS Ineff= 2 , 0
                            7625         1735.36
Permanent Ineff=
       F       F
Bank Sta=4286.9,5047.1
XS Rating Curve= 0 ,0
Exp/Cntr=0.3,0.1

Type RM Length L Ch R = 1 ,517905  ,3349,3349,3349
BEGIN DESCRIPTION:
PEDERNALES RIVER 104.0
END DESCRIPTION:
XS GIS Cut Line= 4
      2723651.26     10059231.27      2723029.86     10047348.16
      2722948.97     10036721.45      2723733.32     10029230.26
#Sta/Elev= 30
-10762.3  1950.1 -9916.1 1848.59 -9762.5 1837.75 -6839.4 1751.15 -5641.9  1765.9
   -3760 1741.34 -3564.8 1746.16   -3202 1743.15 -2805.5 1730.83   290.3 1743.28
    4259  1687.5  4376.6 1682.15  4921.6 1678.48  4941.6 1673.42  5021.3 1646.44
  5401.6 1671.19  5411.6 1670.83  7577.6 1694.21  7790.2 1703.19  8508.2  1676.5
  8736.2 1675.67 11121.8 1762.94 12190.9 1756.21   13099 1753.02 14799.2 1820.52
 16512.7 1953.35 17853.5 1894.93 18334.9 1946.15 19209.6  1931.4 19296.2 1932.81
#Mann= 19 ,-1 , 0
-10762.3      .1       0 -9916.1     .05       0 -9762.5      .1       0
 -5641.9      .1       0   -3760     .05       0 -3564.8      .1       0
   -3202     .16       0 -2805.5      .1       0    4259     .16       0
  4376.6      .1       0  4921.6     .07       0  5411.6      .1       0
  7577.6     .05       0  7790.2      .1       0  8508.2     .16       0
  8736.2      .1       0 12190.9      .1       0 14799.2      .1       0
 19209.6      .1       0
#XS Ineff= 2 , 0
                         8366.48         1707.13
Permanent Ineff=
       F       F
Bank Sta=4941.6,5401.6
XS Rating Curve= 0 ,0
Exp/Cntr=0.3,0.1

Type RM Length L Ch R = 1 ,512367  ,1984,1984,1984
BEGIN DESCRIPTION:
PEDERNALES RIVER 106.0
END DESCRIPTION:
XS GIS Cut Line= 3
      2727171.49     10063744.17      2728032.09     10046283.97
      2725814.36     10032150.41
#Sta/Elev= 30
-17846.5 1963.38  -17607 1915.93-16389.8 1854.86-15168.7 1804.36-14406.7 1786.72
-12524.8 1763.22-11511.3 1785.57-10149.5 1776.11 -9069.9 1772.96 -7562.5 1767.74
 -5712.7 1753.92 -5190.7 1738.22 -4200.6 1764.03 -2415.6 1732.68  -969.3 1707.73
  -300.7 1696.57  2199.8 1668.52  3805.3 1678.79  4591.7 1666.56  4596.7 1666.79
  4999.7 1635.76  5192.3 1665.91  5222.7 1672.83  5879.5 1745.03  8077.5 1782.06
  8963.3 1800.73 10244.1 1819.51 11904.9 1855.11 13361.1 1945.01 13941.4 1912.05
#Mann= 19 ,-1 , 0
-17846.5     .16       0-16389.8      .1       0-15168.7      .1       0
-14406.7      .1       0-10149.5      .1       0 -9069.9     .05       0
 -7562.5     .05       0 -5712.7      .1       0 -2415.6      .1       0
  -969.3     .05       0  -300.7      .1       0  2199.8      .1       0
  3805.3     .05       0  4596.7     .07       0  5222.7      .1       0
  8077.5     .05       0  8963.3      .1       0 10244.1      .1       0
 11904.9      .1       0
Bank Sta=4591.7,5192.3
XS Rating Curve= 0 ,0
Exp/Cntr=0.3,0.1

Type RM Length L Ch R = 1 ,510383  ,2448,2448,2448
BEGIN DESCRIPTION:
PEDERNALES RIVER 107.0
END DESCRIPTION:
XS GIS Cut Line= 3
      2730374.06     10063619.87      2729711.86      10046466.9
      2727901.25     10030059.35
#Sta/Elev= 30
-17700.7 1925.43-17634.5 1889.55-17241.1 1841.79-16233.5 1787.69-15313.7 1784.98
-13101.1 1741.16-10687.9 1742.54   -9943 1739.36   -7957 1717.03 -5261.9 1714.25
 -2354.1 1712.08 -1684.5 1703.21  -737.3 1690.67   385.2 1685.01  4247.7  1662.3
  4790.4 1661.37  4810.5 1655.65  5008.9 1628.88    5233 1660.69  5575.1  1705.2
  6158.6 1699.89  6286.2  1736.3  6697.7 1753.11  8738.2 1821.91 11260.3  1803.5
 12165.7 1794.91 12827.1 1799.01   13993 1817.17   14670 1799.51 15972.2 1930.35
#Mann= 20 ,-1 , 0
-17700.7      .1       0-17241.1      .1       0-15313.7      .1       0
-10687.9      .1       0   -9943     .05       0   -7957     .05       0
 -5261.9      .1       0 -2354.1      .1       0 -1684.5     .05       0
  -737.3      .1       0   385.2     .05       0  4247.7      .1       0
  4810.5     .07       0    5233     .16       0  6697.7      .1       0
  8738.2      .1       0 11260.3      .1       0 12165.7      .1       0
 12827.1      .1       0   13993      .1       0
Bank Sta=4790.4,5233
XS Rating Curve= 0 ,0
Exp/Cntr=0.3,0.1

Type RM Length L Ch R = 1 ,507935  ,1712,1712,1712
BEGIN DESCRIPTION:
PEDERNALES RIVER 108.0
END DESCRIPTION:
XS GIS Cut Line= 4
      2732167.49     10063370.05      2730750.41     10045828.28
      2732512.53     10030114.74      2730882.99     10027503.19
#Sta/Elev= 30
-16489.5 1970.19-15951.4 1958.33-15364.6 1853.29-14476.6 1801.84-13463.6 1813.01
-12541.9  1778.9-11815.9 1770.44-10811.2 1748.13 -8895.2    1717 -6638.9    1707
 -3500.2 1697.51  -407.6 1689.45   973.2 1687.23  2216.5 1684.97    3818 1681.54
  4766.7 1655.56    4819 1655.15  5018.1 1626.11  5179.6 1646.26  5259.7  1658.1
  5659.1 1670.86  6365.4 1751.47  8541.1 1723.61 11292.3  1698.4 14747.8  1758.8
 17919.8 1866.36   18696 1845.34 19189.1 1901.05 19660.9 1896.97 19999.7 1915.47
#Mann= 20 ,-1 , 0
-16489.5      .1       0-15364.6      .1       0-12541.9     .16       0
-11815.9      .1       0-10811.2      .1       0 -8895.2     .05       0
 -6638.9      .1       0 -3500.2      .1       0  -407.6      .1       0
   973.2     .05       0  2216.5     .05       0    3818      .1       0
  4766.7     .07       0  5179.6      .1       0  5659.1     .16       0
  6365.4      .1       0  8541.1      .1       0 11292.3      .1       0
 14747.8      .1       0 19660.9     .16       0
Bank Sta=4819,5259.7
XS Rating Curve= 0 ,0
Exp/Cntr=0.3,0.1

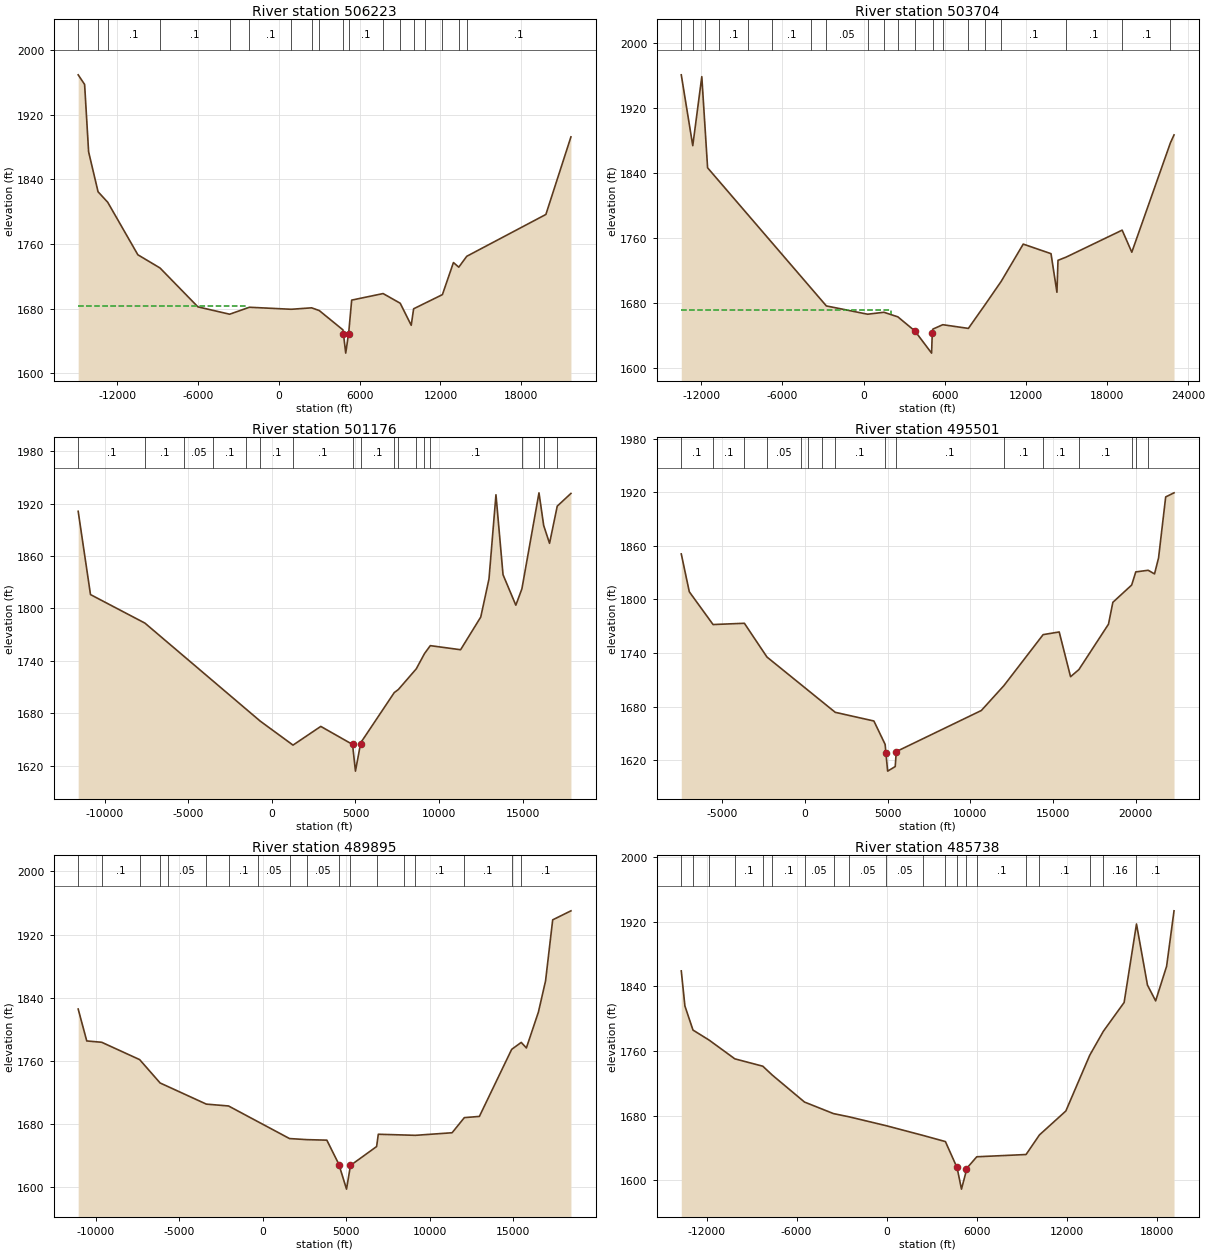
Type RM Length L Ch R = 1 ,506223  ,2519,2519,2519
BEGIN DESCRIPTION:
PEDERNALES RIVER 109.0
END DESCRIPTION:
XS GIS Cut Line= 4
      2734187.69     10061888.29      2732373.28     10045268.42
       2734431.6      10030014.2      2732535.63     10025963.32
#Sta/Elev= 30
-14896.9 1969.53-14419.5 1957.65-14121.8 1874.12-13421.1 1824.69  -12702 1811.64
-10466.2 1746.62 -8820.3 1730.25 -6008.5  1682.1 -3652.3 1672.98 -2185.9 1681.61
   915.9  1679.1  2435.1  1680.9  3002.9  1677.5  4762.8 1653.54  4793.1 1649.02
  4966.6 1624.78  5176.5 1648.95  5206.8 1653.41  5408.1 1690.45  7742.1 1698.57
  9012.7 1686.57  9829.1 1659.27 10007.8  1679.7 10834.9 1686.49 12144.1 1697.24
 12963.5 1736.98 13359.8 1731.28 13952.6 1744.74 19827.1 1796.56 21686.8 1892.66
#Mann= 18 ,-1 , 0
-14896.9     .16       0-13421.1     .16       0  -12702      .1       0
 -8820.3      .1       0 -3652.3      .1       0 -2185.9      .1       0
   915.9      .1       0  2435.1     .05       0  3002.9      .1       0
  4762.8     .07       0  5206.8      .1       0  7742.1     .05       0
  9012.7      .1       0 10007.8      .1       0 10834.9      .1       0
 12144.1      .1       0 13359.8      .1       0 13952.6      .1       0
#XS Ineff= 2 , 0
        -2363.64  1683.1
Permanent Ineff=
       F       F
Bank Sta=4793.1,5176.5
XS Rating Curve= 0 ,0
Exp/Cntr=0.3,0.1

Type RM Length L Ch R = 1 ,503704  ,2528,2528,2528
BEGIN DESCRIPTION:
PEDERNALES RIVER 110.0
END DESCRIPTION:
XS GIS Cut Line= 5
      2735309.54     10060998.94      2734384.51     10045500.92
      2736651.39     10036013.58      2740122.38     10030360.37
      2742460.65     10026499.24
#Sta/Elev= 30
-13480.3 1960.36-12630.1 1873.25-11962.4 1958.09-11736.8 1899.17-11534.4 1846.01
  -10705 1829.96 -8543.5 1788.13 -6771.6 1753.84 -3926.7 1698.79 -2754.3 1676.11
   292.8 1665.92  1502.6 1668.31  2532.6 1662.66 3791.22 1645.31  5023.8 1618.06
  5075.4 1642.32  5116.6 1647.57  5849.8 1653.02  7744.7 1648.48  9004.1 1678.23
 10174.3 1706.45 11799.7 1752.15 13853.8 1740.39 14290.7 1692.93   14370 1732.21
 14967.7 1736.13   19113 1769.32   19826 1742.19 22679.7 1876.71 22947.4 1886.45
#Mann= 20 ,-1 , 0
-13480.3     .16       0-12630.1     .16       0-11736.8      .1       0
  -10705      .1       0 -8543.5     .05       0 -6771.6      .1       0
 -3926.7     .05       0 -2754.3     .05       0   292.8     .05       0
  1502.6     .05       0  2532.6     .05       0 3791.22     .07       0
  5116.6     .16       0  5849.8      .1       0  7744.7      .1       0
  9004.1      .1       0 10174.3      .1       0 14967.7      .1       0
   19113      .1       0 22679.7     .16       0
#XS Ineff= 2 , 0
            2000 1670.59
Permanent Ineff=
       F       F
Bank Sta=3791.22,5075.4
XS Rating Curve= 0 ,0
Exp/Cntr=0.3,0.1

Type RM Length L Ch R = 1 ,501176  ,5675,5675,5675
BEGIN DESCRIPTION:
PEDERNALES RIVER 111.0
END DESCRIPTION:
XS GIS Cut Line= 3
      2736008.92     10060590.75      2736044.37     10046076.45
      2742111.85     10032398.55
#Sta/Elev= 30
-11586.1  1911.2-10849.1 1815.85 -7593.8 1783.19 -5263.9 1745.29 -3491.5 1716.46
   -1563 1685.09    -698 1671.02  1265.7 1643.52  2927.1 1664.93  4827.1 1644.28
  5000.7 1613.73  5305.1 1645.05  5314.4 1646.15  7323.6 1703.67  7568.8 1707.18
  8638.6 1730.81  9130.1 1748.25  9478.8 1757.39 11290.4 1752.71 12496.3 1790.11
 12989.1 1833.72 13406.6 1930.15 13829.5  1838.6 14594.7 1803.72   14958 1822.43
 15980.3 1932.34 16262.1 1894.87 16612.2 1874.53 17072.4 1917.09 17891.5 1931.65
#Mann= 18 ,-1 , 0
-11586.1      .1       0 -7593.8      .1       0 -5263.9     .05       0
 -3491.5      .1       0   -1563     .05       0    -698      .1       0
  1265.7      .1       0  4827.1     .07       0  5314.4      .1       0
  7323.6     .05       0  7568.8      .1       0  8638.6      .1       0
  9130.1     .16       0  9478.8      .1       0   14958      .1       0
 15980.3     .16       0 16262.1      .1       0 17072.4      .1       0
Bank Sta=4827.1,5305.1
XS Rating Curve= 0 ,0
Exp/Cntr=0.3,0.1

Type RM Length L Ch R = 1 ,495501  ,5606,5606,5606
BEGIN DESCRIPTION:
PEDERNALES RIVER 112.0
END DESCRIPTION:
XS GIS Cut Line= 4
      2736293.29     10060505.23      2737507.49     10051004.32
      2742428.26     10039732.72       2744280.7      10032054.4
#Sta/Elev= 30
 -7468.7 1851.02 -6983.3 1808.65 -5547.4 1771.93 -3654.8 1773.35 -2292.5 1735.58
  -263.4 1705.12   175.7 1698.53  1058.5 1685.27  1835.9  1673.6  4170.4 1663.89
  4851.5 1637.64  4898.4  1627.5  5002.7 1607.73  5459.9 1612.86  5521.8 1629.59
 10664.7 1675.66 12028.5 1703.54 14396.7 1760.62 15368.9 1763.63 16054.6 1713.49
 16558.8  1721.5 18347.2 1772.35 18609.4 1796.78 19747.2  1816.2 19995.9 1830.91
 20744.8 1832.72 21127.4 1828.66 21371.6 1846.49 21802.8 1914.89   22307 1919.48
#Mann= 16 ,-1 , 0
 -7468.7      .1       0 -5547.4      .1       0 -3654.8      .1       0
 -2292.5     .05       0  -263.4      .1       0   175.7     .16       0
  1058.5      .1       0  1835.9      .1       0  4851.5     .07       0
  5521.8      .1       0 12028.5      .1       0 14396.7      .1       0
 16558.8      .1       0 19747.2     .05       0 19995.9      .1       0
 20744.8      .1       0
Bank Sta=4898.4,5521.8
XS Rating Curve= 0 ,0
Exp/Cntr=0.3,0.1

Type RM Length L Ch R = 1 ,489895  ,4157,4157,4157
BEGIN DESCRIPTION:
PEDERNALES RIVER 113.0
END DESCRIPTION:
XS GIS Cut Line= 3
      2736511.93     10060617.89      2743351.53     10049864.49
      2746080.83     10033287.41
#Sta/Elev= 30
  -11069 1825.49-10554.5 1784.99 -9658.5  1783.3 -7382.9 1761.31 -6155.9 1731.68
 -5670.1 1726.98 -3385.1 1704.85 -2055.2 1702.51  -285.1  1682.5  1601.6 1661.17
  2633.5  1659.8  3840.7 1659.13  4574.5 1627.99  4579.9 1627.21  5020.2 1597.02
    5258  1627.1  6824.4 1651.03  6925.7 1666.63  8443.2  1665.7    9150 1665.26
 11350.4 1668.53 12084.7 1687.73 12986.3 1689.25 14921.9 1774.31 15496.1 1783.13
 15803.7 1776.14 16525.1 1821.57 16953.4 1861.12 17381.7 1938.61 18475.5 1950.05
#Mann= 18 ,-1 , 0
  -11069      .1       0 -9658.5      .1       0 -7382.9     .05       0
 -6155.9      .1       0 -5670.1     .05       0 -3385.1     .05       0
 -2055.2      .1       0  -285.1     .05       0  1601.6      .1       0
  2633.5     .05       0  4574.5     .07       0    5258     .16       0
  6824.4      .1       0  8443.2     .05       0    9150      .1       0
 12084.7      .1       0 14921.9     .16       0 15496.1      .1       0
Bank Sta=4579.9,5258
XS Rating Curve= 0 ,0
Exp/Cntr=0.3,0.1

Type RM Length L Ch R = 1 ,485738  ,2052,2052,2052
BEGIN DESCRIPTION:
PEDERNALES RIVER 114.0
END DESCRIPTION:
XS GIS Cut Line= 3
      2748052.29     10066036.85      2746312.11     10055235.39
       2748114.6     10033420.56
#Sta/Elev= 30
-13684.2 1859.31-13441.6 1815.86-12903.3 1786.04-11820.9 1773.52  -10115 1750.41
 -8251.9 1741.29 -7609.9 1730.14 -5471.8 1696.88   -3541  1682.6 -2495.2 1678.59
   -62.4 1667.78  2429.4 1655.56  3914.4 1647.97  4679.6 1616.12  4684.6 1616.31
  4984.2  1589.1  5275.4 1609.62  5295.5 1613.99  6002.4 1629.15  9286.3 1631.95
 10178.1 1656.19 11938.1 1685.83 13531.4 1754.93 14436.7 1784.53 15821.2 1820.21
 16644.7 1917.39 17376.5 1841.71 17920.5 1822.18   18651 1865.02 19145.7 1933.67
#Mann= 20 ,-1 , 0
-13684.2      .1       0-12903.3      .1       0-11820.9      .1       0
  -10115      .1       0 -8251.9     .05       0 -7609.9      .1       0
 -5471.8     .05       0   -3541      .1       0 -2495.2     .05       0
   -62.4     .05       0  2429.4     .05       0  3914.4      .1       0
  4684.6     .07       0  5275.4      .1       0  6002.4      .1       0
  9286.3     .16       0 10178.1      .1       0 13531.4     .16       0
 14436.7     .16       0 16644.7      .1       0
Bank Sta=4679.6,5295.5
XS Rating Curve= 0 ,0
Exp/Cntr=0.3,0.1

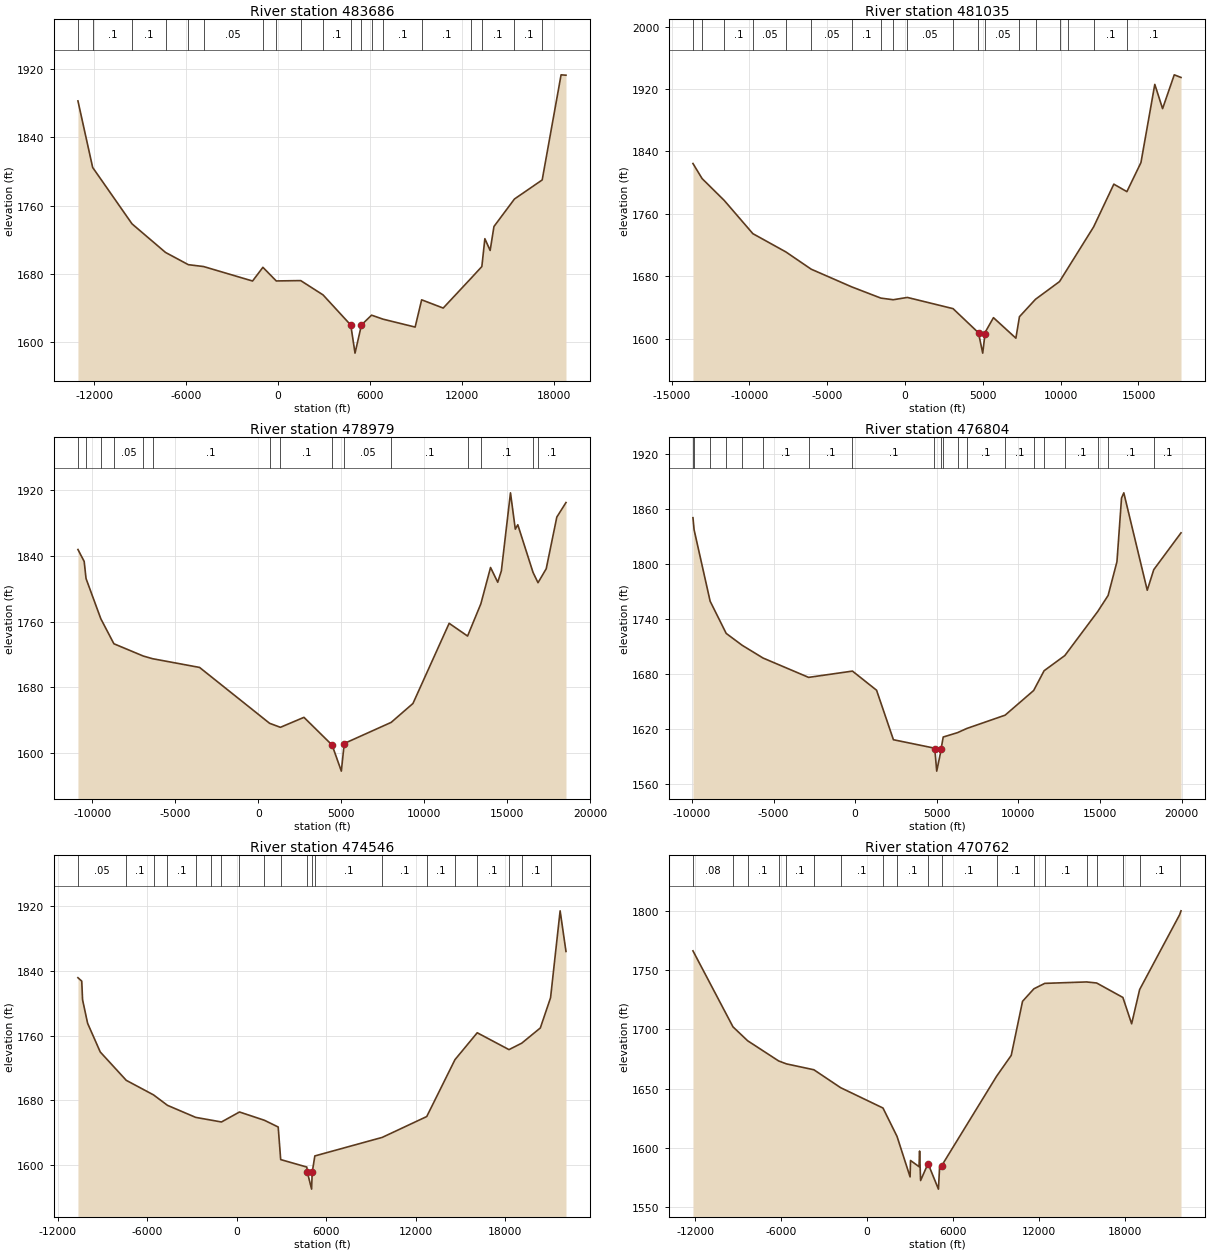
Type RM Length L Ch R = 1 ,483686  ,2651,2651,2651
BEGIN DESCRIPTION:
PEDERNALES RIVER 115.0
END DESCRIPTION:
XS GIS Cut Line= 3
      2749602.04     10065230.41      2748587.41     10053557.66
       2749599.5     10033438.57
#Sta/Elev= 30
-13058.5 1882.65-12097.7 1804.76 -9527.4 1738.69 -7340.9 1705.24 -5854.4 1690.92
 -4854.2  1688.7   -1659 1671.77    -983 1687.81    -111 1671.85  1483.7 1672.26
  2943.9  1655.5  4747.4 1620.29  4752.4 1620.31    5030 1587.32  5400.7 1616.33
  5410.7 1619.68  6112.1 1631.78  6854.7 1627.11  8955.2 1617.82  9380.2 1649.75
 10787.5  1640.1 12600.9 1674.91 13310.3 1688.73 13506.8 1721.35 13851.4 1707.56
 14100.8 1735.62   15439  1767.8 17248.9 1790.12   18483 1913.23 18802.8 1912.78
#Mann= 19 ,-1 , 0
-13058.5      .1       0-12097.7      .1       0 -9527.4      .1       0
 -7340.9      .1       0 -5854.4      .1       0 -4854.2     .05       0
    -983      .1       0    -111     .05       0  1483.7      .1       0
  2943.9      .1       0  4752.4     .07       0  5400.7      .1       0
  6112.1     .05       0  6854.7      .1       0  9380.2      .1       0
 12600.9      .1       0 13310.3      .1       0   15439      .1       0
 17248.9      .1       0
Bank Sta=4747.4,5410.7
XS Rating Curve= 0 ,0
Exp/Cntr=0.3,0.1

Type RM Length L Ch R = 1 ,481035  ,2056,2056,2056
BEGIN DESCRIPTION:
PEDERNALES RIVER 116.0
END DESCRIPTION:
XS GIS Cut Line= 2
      2750432.81      10064799.2      2751524.95     10033460.52
#Sta/Elev= 30
-13625.6 1824.46-13041.4 1805.22-11614.1 1777.11 -9776.5 1734.58 -7653.3 1711.15
 -6031.7 1689.09 -3428.5 1666.43 -1554.2 1652.03  -759.1 1649.92   149.2 1652.88
  3085.9 1638.51    4711 1607.74    4721 1607.35  4990.9 1581.52  5141.3 1606.44
  5151.3 1608.34  5681.6 1626.95  7122.5 1600.69  7352.3 1628.19  8383.1 1650.51
  9926.4 1673.19 10481.1 1690.95 12116.5 1743.23 13416.3    1798 14254.6 1788.43
 15157.3  1825.6 16047.9 1925.86 16548.2 1894.78 17298.6 1938.09 17732.1 1934.71
#Mann= 19 ,-1 , 0
-13625.6     .05       0-13041.4      .1       0-11614.1      .1       0
 -9776.5     .05       0 -7653.3      .1       0 -6031.7     .05       0
 -3428.5      .1       0 -1554.2     .16       0  -759.1      .1       0
   149.2     .05       0  3085.9      .1       0    4711     .07       0
  5151.3     .05       0  7352.3     .05       0  8383.1      .1       0
  9926.4     .05       0 10481.1      .1       0 12116.5      .1       0
 14254.6      .1       0
Bank Sta=4721,5141.3
XS Rating Curve= 0 ,0
Exp/Cntr=0.3,0.1

Type RM Length L Ch R = 1 ,478979  ,2175,2175,2175
BEGIN DESCRIPTION:
PEDERNALES RIVER 117.0
END DESCRIPTION:
XS GIS Cut Line= 4
      2753710.57     10062088.62      2752990.17     10048824.22
      2753612.17     10033705.62      2753183.15     10032821.11
#Sta/Elev= 30
  -10868 1847.81-10492.6 1833.31  -10380 1812.48 -9491.4 1763.59 -8701.6 1733.09
 -6928.9 1718.14 -6369.5  1714.9 -3541.4  1704.3   678.3 1636.29  1329.3 1631.43
  2746.7 1643.56  4442.7 1609.82  4998.4 1578.11  5172.9 1611.73  8000.7 1637.43
  9312.4 1660.44 11493.1 1757.98 12602.3 1742.48 13402.2 1781.71 13986.2 1825.94
 14418.9 1807.96 14636.8 1821.76 15187.2 1916.78 15477.5 1872.55 15627.6 1877.95
 16544.6 1819.99 16845.3  1807.4 17339.8 1824.39 17978.5 1887.27 18530.4 1904.97
#Mann= 15 ,-1 , 0
  -10868     .05       0  -10380      .1       0 -9491.4     .15       0
 -8701.6     .05       0 -6928.9     .05       0 -6369.5      .1       0
   678.3     .16       0  1329.3      .1       0  4442.7     .07       0
  5172.9     .05       0  8000.7      .1       0 12602.3     .16       0
 13402.2      .1       0 16544.6     .16       0 16845.3      .1       0
Bank Sta=4442.7,5172.9
XS Rating Curve= 0 ,0
Exp/Cntr=0.3,0.1

Type RM Length L Ch R = 1 ,476804  ,2258,2258,2258
BEGIN DESCRIPTION:
PEDERNALES RIVER 118.0
END DESCRIPTION:
XS GIS Cut Line= 4
      2754096.85     10061983.21      2755026.33     10048738.72
      2754815.48     10034270.15      2753682.94     10032442.24
#Sta/Elev= 30
 -9933.4 1850.29 -9864.5 1837.15 -8881.5 1759.19 -7898.5 1724.05 -6915.5 1711.03
 -5637.6 1697.15 -2848.9 1676.06  -162.5 1682.92  1313.7 1662.05  2346.2 1608.03
  4858.8 1598.84  4878.8 1598.42  4998.6 1573.77  5278.9 1597.83  5288.9 1600.24
  5397.3 1610.99  6272.8 1615.76  6842.8 1620.32  9187.9 1634.82 10936.7 1661.73
 11576.8 1683.31 12846.9 1699.86 14861.4 1747.91 15498.3 1765.45   16040 1802.31
   16320 1871.75   16460 1877.44 17895.7 1771.18 18294.3 1793.59 19964.1 1833.77
#Mann= 20 ,-1 , 0
 -9933.4      .1       0 -9864.5     .05       0 -8881.5     .05       0
 -7898.5     .05       0 -6915.5      .1       0 -5637.6      .1       0
 -2848.9      .1       0  -162.5      .1       0  4858.8     .07       0
  5288.9      .1       0  5397.3      .1       0  6272.8     .05       0
  6842.8      .1       0  9187.9      .1       0 10936.7     .05       0
 11576.8     .05       0 12846.9      .1       0 14861.4     .05       0
 15498.3      .1       0 18294.3      .1       0
Bank Sta=4878.8,5278.9
XS Rating Curve= 0 ,0
Exp/Cntr=0.3,0.1

Type RM Length L Ch R = 1 ,474546  ,3784,3784,3784
BEGIN DESCRIPTION:
PEDERNALES RIVER 119.0
END DESCRIPTION:
XS GIS Cut Line= 4
      2754369.17     10062206.53      2757106.88     10049533.81
      2757550.73     10035513.18      2754418.56      10030690.1
#Sta/Elev= 30
-10662.5 1831.77-10407.2 1827.54-10352.7 1804.53-10015.1 1775.46   -9166 1739.88
 -7421.3 1704.78   -5593 1686.78 -4655.5 1673.83 -2765.4 1658.94   -1734 1655.54
 -1033.6 1653.23   176.1 1665.58  1849.4 1655.33  2772.9 1646.99    2940 1606.69
  4693.8 1597.43  4725.9 1591.26  5013.8 1570.12    5054 1590.86  5231.7  1611.2
  9752.6 1634.15 12738.7 1659.95 14633.8 1730.37 16126.5 1763.66 18256.6 1742.79
 19112.5 1750.77 20359.2 1769.59 21046.3 1807.02 21687.9 1914.57 22081.1 1864.28
#Mann= 20 ,-1 , 0
-10662.5     .05       0 -7421.3      .1       0   -5593     .05       0
 -4655.5      .1       0 -2765.4      .1       0   -1734      .1       0
 -1033.6      .1       0   176.1      .1       0  1849.4      .1       0
    2940     .05       0  4693.8     .07       0    5054      .1       0
  5231.7      .1       0  9752.6      .1       0 12738.7      .1       0
 14633.8      .1       0 16126.5      .1       0 18256.6      .1       0
 19112.5      .1       0 21046.3      .1       0
Bank Sta=4725.9,5054
XS Rating Curve= 0 ,0
Exp/Cntr=0.3,0.1

Type RM Length L Ch R = 1 ,470762  ,3591,3591,3591
BEGIN DESCRIPTION:
PEDERNALES RIVER 120.0
END DESCRIPTION:
XS GIS Cut Line= 5
      2755494.79     10062390.07      2759881.02     10049942.25
      2760903.97     10039971.26      2756796.62     10031414.17
      2755833.12     10030429.02
#Sta/Elev= 30
-12156.8 1766.27 -9360.7 1702.07 -8334.4 1690.31 -6171.2 1673.28 -5623.9 1670.79
 -3711.1 1665.84 -1842.9 1650.71    1117 1633.52  2098.1 1609.52    3010 1575.32
  3040.2 1589.22  3633.3 1583.99  3673.5 1597.16  3743.8 1572.27  4263.8 1586.61
  4990.1 1565.01  5070.8 1583.73  5211.5 1584.69  9056.6 1660.46 10075.8    1678
 10864.8 1723.65 11658.1 1734.24 12419.1 1738.81 15333.4 1740.02 16041.4 1739.13
 17874.8 1726.91 18485.9 1704.68   19045 1733.61 21838.8 1796.82 21934.3 1800.09
#Mann= 19 ,-1 , 0
-12156.8     .08       0 -9360.7     .05       0 -8334.4      .1       0
 -6171.2     .05       0 -5623.9      .1       0 -3711.1      .1       0
 -1842.9      .1       0    1117     .05       0  2098.1      .1       0
  4263.8     .07       0  5211.5      .1       0  9056.6      .1       0
 11658.1      .1       0 12419.1      .1       0 15333.4     .05       0
 16041.4      .1       0 17874.8      .1       0   19045      .1       0
 21838.8      .1       0
Bank Sta=4263.8,5211.5
XS Rating Curve= 0 ,0
Exp/Cntr=0.3,0.1

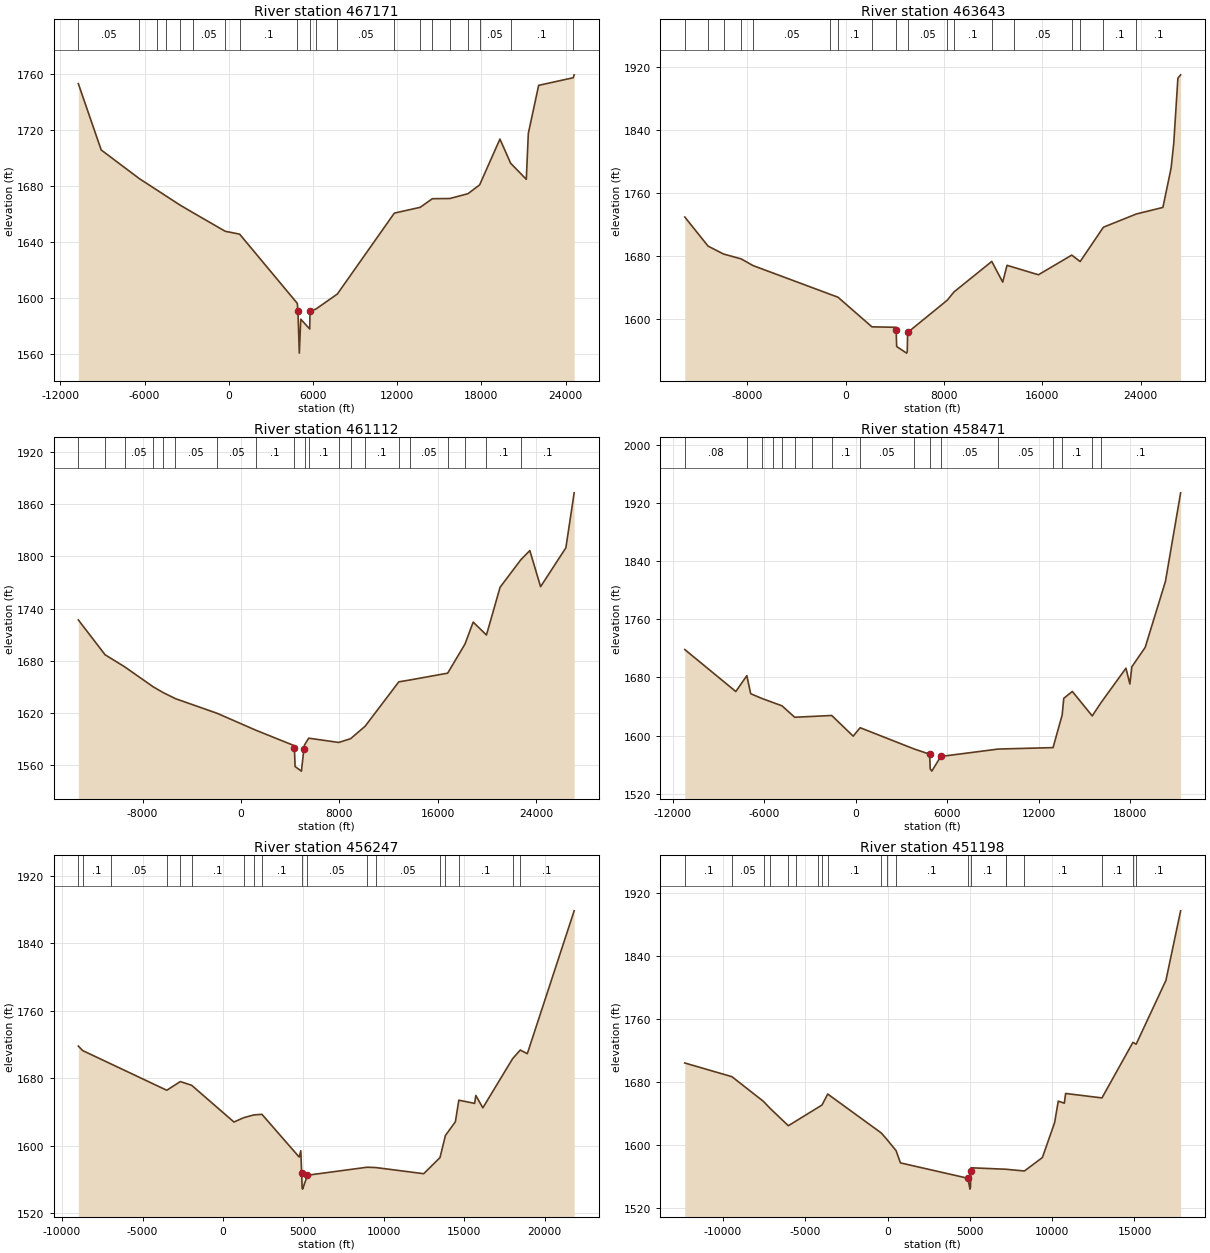
Type RM Length L Ch R = 1 ,467171  ,3528,3528,3528
BEGIN DESCRIPTION:
PEDERNALES RIVER 121.0
END DESCRIPTION:
XS GIS Cut Line= 4
      2756856.28     10062505.97      2762694.17     10050802.65
      2762087.63     10038099.17      2756866.51     10030114.61
#Sta/Elev= 30
-10723.1 1752.87 -9094.3 1705.61 -6376.4 1685.17 -5106.2 1676.92 -4490.1 1672.92
 -3476.5 1666.33 -2570.2 1661.01  -259.1 1647.65     773 1645.59  4884.3 1596.24
  4927.3 1590.62  5027.2 1560.79  5127.5 1584.97  5768.3 1578.01  5788.3 1590.53
  6215.2 1592.25  7737.9 1602.93   11798 1660.58 13646.1 1664.73 14506.2 1670.85
 15753.4 1670.99 17049.2 1674.44 17875.7 1680.68 19323.8 1713.36 20086.2 1696.14
 21202.8 1684.67 21347.5  1717.4 22083.4 1751.64 24546.5 1757.06 24613.5 1759.14
#Mann= 20 ,-1 , 0
-10723.1     .05       0 -6376.4     .05       0 -5106.2      .1       0
 -4490.1     .05       0 -3476.5      .1       0 -2570.2     .05       0
  -259.1     .05       0     773      .1       0  4884.3     .07       0
  5768.3     .16       0  6215.2      .1       0  7737.9     .05       0
   11798      .1       0 13646.1      .1       0 14506.2     .05       0
 15753.4      .1       0 17049.2      .1       0 17875.7     .05       0
 20086.2      .1       0 24546.5     .05       0
Bank Sta=4927.3,5788.3
XS Rating Curve= 0 ,0
Exp/Cntr=0.3,0.1

Type RM Length L Ch R = 1 ,463643  ,2531,2531,2531
BEGIN DESCRIPTION:
PEDERNALES RIVER 123.0
END DESCRIPTION:
XS GIS Cut Line= 6
      2757515.63     10062360.06       2765101.1      10049534.1
      2765363.81     10045023.09      2763593.96     10042050.17
      2761925.74     10036404.65      2755513.64     10026778.41
#Sta/Elev= 30
-13079.9  1728.9-11182.8 1691.92 -9924.9 1681.92 -8497.8 1675.76 -7525.6 1667.22
 -1250.5 1630.75  -615.6 1627.06  2143.5 1589.46  4105.5 1588.87  4115.5 1585.63
  4155.6 1564.49  4966.7 1556.07    5017  1557.7  5047.1 1582.27  8269.1 1623.25
  8821.4 1633.79 11893.8  1672.5 12783.1 1646.29 13134.2 1667.57 13686.5 1664.98
 15687.9 1655.58 18400.6 1680.53 19084.4 1672.38   20974 1715.96 23653.2 1732.75
   25815 1741.11 26482.4 1791.07 26697.5 1822.46 27034.3 1905.19 27256.8 1909.47
#Mann= 18 ,-1 , 0
-13079.9     .05       0-11182.8      .1       0 -9924.9      .1       0
 -8497.8      .1       0 -7525.6     .05       0 -1250.5     .05       0
  -615.6      .1       0  2143.5     .05       0  4105.5     .07       0
  5047.1     .05       0  8269.1     .05       0  8821.4      .1       0
 11893.8      .1       0 13686.5     .05       0 18400.6     .05       0
 19084.4      .1       0   20974      .1       0 23653.2      .1       0
Bank Sta=4115.5,5047.1
XS Rating Curve= 0 ,0
Exp/Cntr=0.3,0.1

Type RM Length L Ch R = 1 ,461112  ,2641,2641,2641
BEGIN DESCRIPTION:
PEDERNALES RIVER 122.0
END DESCRIPTION:
XS GIS Cut Line= 4
      2757829.51     10062788.91      2765173.27     10052188.94
      2769066.84     10044260.12      2762167.68     10026978.02
#Sta/Elev= 30
  -13229 1726.91-11053.2 1686.92 -9455.1    1673 -7131.5 1650.02   -6323 1643.43
 -5336.2 1636.52 -1931.2 1619.62  1217.8 1600.21    4343 1582.44  4351.2 1579.46
  4404.8  1558.5  4919.2 1553.23  5119.9  1578.5  5174.9 1583.35    5510 1591.07
  7959.1 1586.17  8923.1 1590.52 10101.3 1604.77 12840.2 1655.76 13712.8 1657.83
 16818.2 1665.75 18228.8 1699.24 18892.2  1724.4 19972.8 1709.61 21082.9 1764.43
 22760.4 1795.87 23502.5 1806.59 24377.6 1765.07 26434.2 1809.78 27107.9 1872.89
#Mann= 20 ,-1 , 0
  -13229      .1       0-11053.2      .1       0 -9455.1     .05       0
 -7131.5      .1       0   -6323      .1       0 -5336.2     .05       0
 -1931.2     .05       0  1217.8      .1       0    4343     .07       0
  5174.9      .1       0    5510      .1       0  7959.1     .05       0
  8923.1      .1       0 10101.3      .1       0 12840.2      .1       0
 13712.8     .05       0 16818.2      .1       0 18228.8      .1       0
 19972.8      .1       0 22760.4      .1       0
Bank Sta=4351.2,5119.9
XS Rating Curve= 0 ,0
Exp/Cntr=0.3,0.1

Type RM Length L Ch R = 1 ,458471  ,2224,2224,2224
BEGIN DESCRIPTION:
PEDERNALES RIVER 124.0
END DESCRIPTION:
XS GIS Cut Line= 6
      2758179.21      10062758.9       2764675.8     10055284.73
      2766766.82      10050335.7      2768848.42     10048329.42
       2771132.2     10041438.09      2772843.23     10034531.14
#Sta/Elev= 30
-11217.4 1718.33 -7868.8 1660.59 -7145.9 1682.42 -6890.8 1657.55 -6156.7 1651.04
 -5442.1 1645.55 -4838.5 1640.91 -4001.8 1625.16 -2866.2 1626.31 -1572.9 1627.62
  -166.1 1599.19   291.9 1610.78  3819.2 1581.65  4852.7 1574.35  4888.2 1554.28
    4994 1551.04  5583.3 1571.22  9361.6 1581.42 12952.6 1583.41 13551.5 1628.48
 13655.4 1651.23 14216.6  1660.7 15523.4 1627.05 16088.6 1644.91   17737 1692.68
 17994.2 1670.96 18123.5 1694.61   18998 1721.26 20327.9 1812.05 21324.9 1933.99
#Mann= 17 ,-1 , 0
-11217.4     .08       0 -7145.9      .1       0 -6156.7     .05       0
 -5442.1      .1       0 -4838.5      .1       0 -4001.8      .1       0
 -2866.2     .05       0 -1572.9      .1       0   291.9     .05       0
  3819.2      .1       0  4888.2     .07       0  5583.3     .05       0
  9361.6     .05       0 12952.6     .16       0 13551.5      .1       0
 15523.4     .05       0 16088.6      .1       0
Bank Sta=4852.7,5583.3
XS Rating Curve= 0 ,0
Exp/Cntr=0.3,0.1

Type RM Length L Ch R = 1 ,456247  ,5049,5049,5049
BEGIN DESCRIPTION:
PEDERNALES RIVER 125.0
END DESCRIPTION:
XS GIS Cut Line= 4
      2770833.75     10064463.87      2768494.29     10053215.16
      2769600.21      10048168.2      2773558.87     10034576.89
#Sta/Elev= 30
 -8988.3 1718.06 -8720.1 1712.75 -6974.3 1697.02 -3490.9 1665.64 -2651.9 1675.96
 -1949.3 1671.59   683.7 1627.96  1276.4 1633.04  1915.4 1636.39  2422.2 1637.12
  4734.3 1586.45  4837.5 1593.86  4887.9 1567.59  4918.6 1550.21    4949 1548.38
  5252.5 1564.88  8956.2 1574.35  9484.2    1574 12475.3 1566.69 13487.4 1585.82
 13823.4 1611.98 14442.9  1628.3 14656.8 1653.87 15640.4  1650.1 15713.3 1659.49
   16150 1644.82 17999.4 1703.12 18475.1 1713.38   18912    1709 21823.9 1878.49
#Mann= 18 ,-1 , 0
 -8988.3     .05       0 -8720.1      .1       0 -6974.3     .05       0
 -3490.9      .1       0 -2651.9      .1       0 -1949.3      .1       0
  1276.4      .1       0  1915.4     .08       0  2422.2      .1       0
  4918.6     .07       0  5252.5     .05       0  8956.2      .1       0
  9484.2     .05       0 13487.4     .16       0 13823.4      .1       0
 14656.8      .1       0 17999.4     .05       0 18475.1      .1       0
Bank Sta=4887.9,5252.5
XS Rating Curve= 0 ,0
Exp/Cntr=0.3,0.1

Type RM Length L Ch R = 1 ,451198  ,2063,2063,2063
BEGIN DESCRIPTION:
PEDERNALES RIVER 126.0
END DESCRIPTION:
XS GIS Cut Line= 3
      2771771.31     10064255.23      2770810.77     10045614.37
      2773895.44     10034583.03
#Sta/Elev= 30
-12316.2 1704.22 -9451.1 1686.81 -7534.5  1655.4 -7146.8 1646.84 -6027.3 1624.54
 -5541.9 1630.77 -4227.6 1647.65 -3981.8 1650.81 -3634.1 1664.78  -384.4  1615.4
   -61.3 1607.69   521.9 1592.78   782.7 1577.32  4878.1 1557.79    5008 1543.98
  5038.3  1546.5  5058.3 1567.33  5068.3 1571.09  7166.8 1569.26  8315.8 1567.03
  9406.2 1584.13 10146.2 1628.22 10371.8 1655.74 10739.2 1653.17 10817.8 1665.51
 13025.7 1659.86 14905.3 1730.39 15101.8 1728.08 16910.4 1809.11 17803.9 1897.52
#Mann= 20 ,-1 , 0
-12316.2      .1       0 -9451.1     .05       0 -7534.5      .1       0
 -7146.8     .05       0 -6027.3      .1       0 -5541.9     .05       0
 -4227.6      .1       0 -3981.8     .16       0 -3634.1      .1       0
  -384.4      .1       0   -61.3     .05       0   521.9      .1       0
  4878.1     .07       0  5068.3      .1       0  7166.8     .05       0
  7166.8     .05       0  8315.8      .1       0 13025.7      .1       0
 14905.3     .05       0 15101.8      .1       0
Bank Sta=4878.1,5058.3
XS Rating Curve= 0 ,0
Exp/Cntr=0.3,0.1