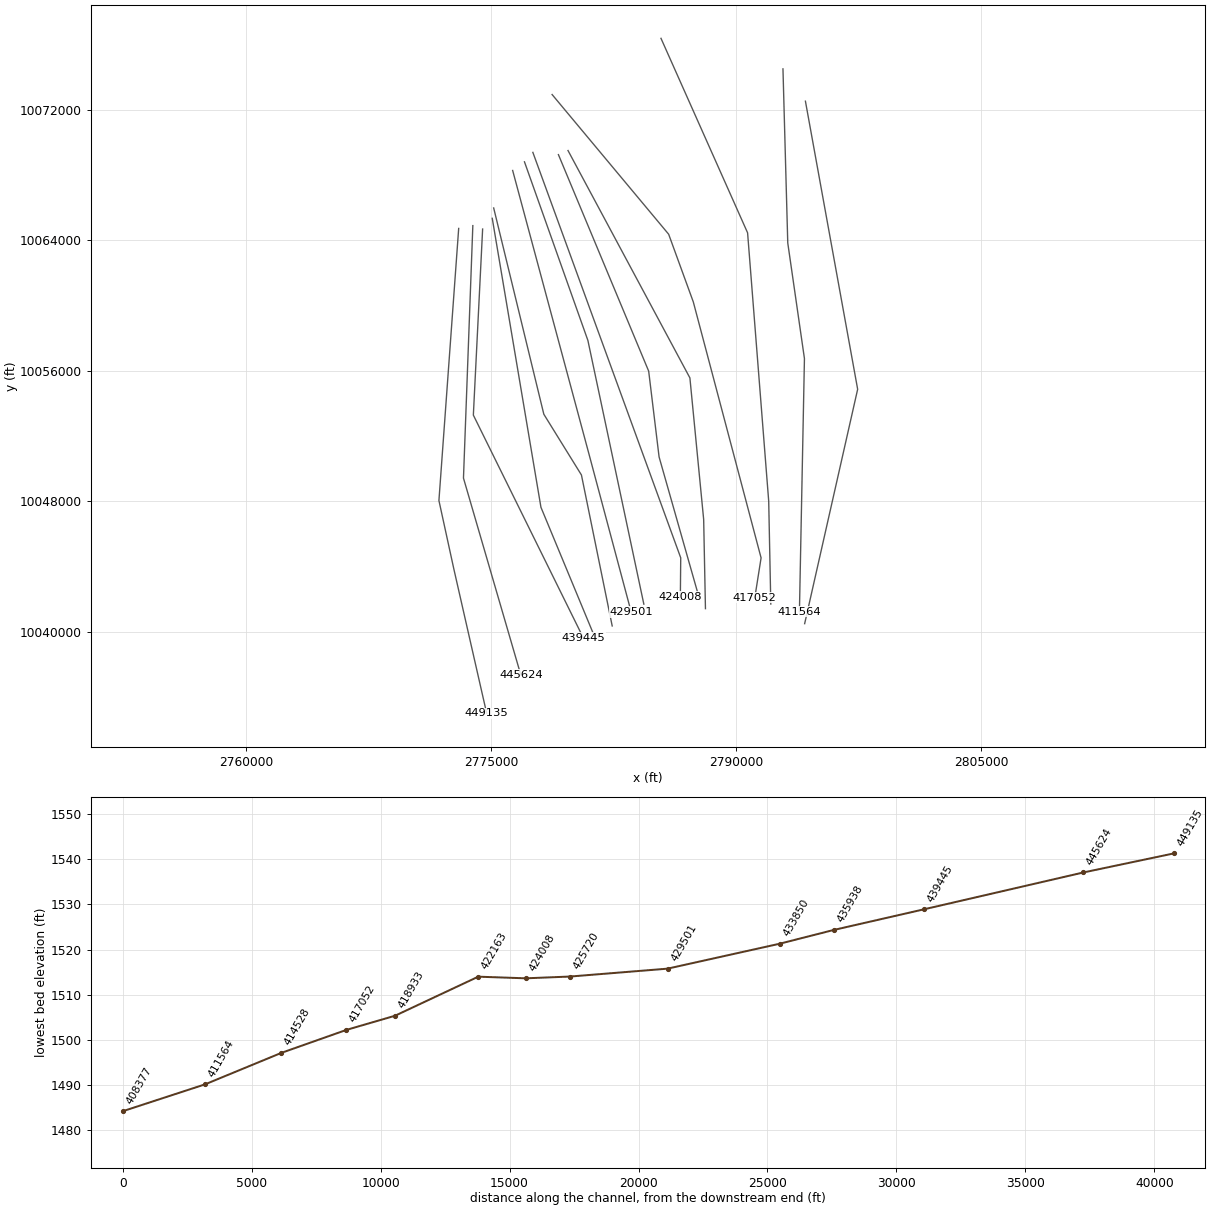
HEC-RAS study PEDERNALES RIVER.prj: PEDERNALES RIVER Base Level Engineering

--- PEDERNALES RIVER.g02 (geometry) --- (continued)

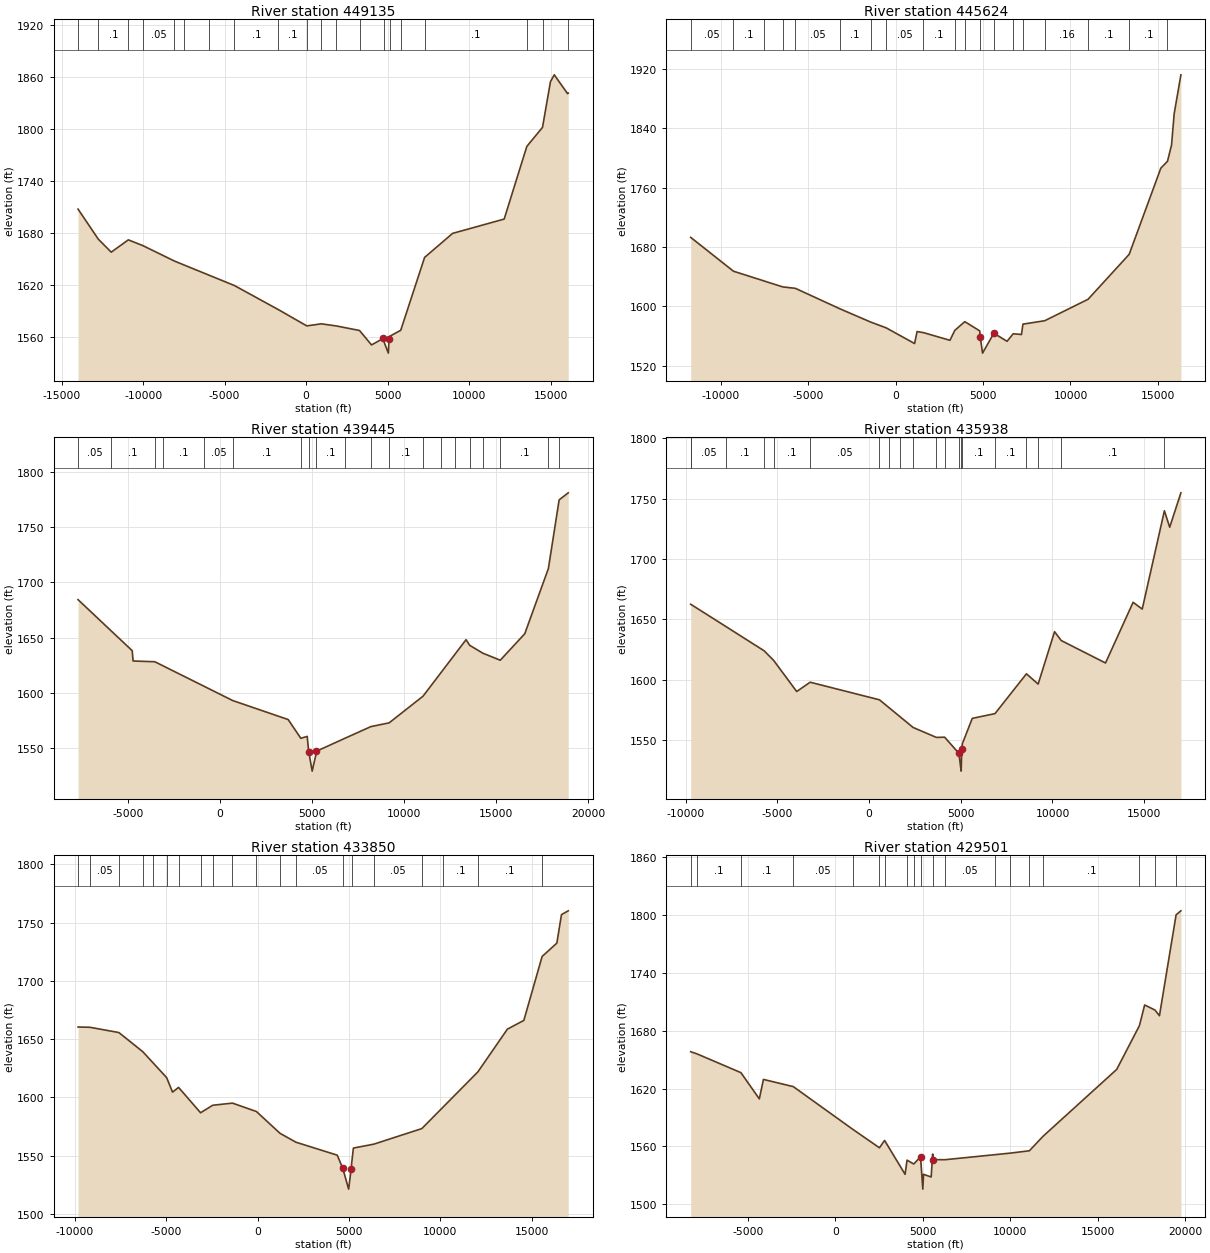
Type RM Length L Ch R = 1 ,449135  ,3511,3511,3511
BEGIN DESCRIPTION:
PEDERNALES RIVER 128.0
END DESCRIPTION:
XS GIS Cut Line= 4
       2773010.9     10064728.25      2771801.34     10048057.03
      2772720.36     10043836.06      2774725.51     10035017.46
#Sta/Elev= 30
-13994.6 1707.38-12749.9 1672.72-11958.5 1657.74  -10908 1671.95-10008.9 1665.22
 -8077.9 1647.48 -7486.1 1642.94 -5942.7  1631.1 -4398.9 1619.26   -1699 1591.46
    42.9 1572.72   931.2 1575.13  1860.8 1572.65  3276.8 1567.44  4013.3 1550.78
    4740 1558.36  4748.4 1555.88  5046.8 1541.33  5087.9 1557.48  5118.6  1560.6
    5806  1567.7  7269.4 1651.68  8989.9 1679.42 12152.9  1695.9 13542.2 1779.68
 14504.7 1801.63   14994 1854.44 15226.4 1862.23 16041.7 1840.59   16084 1841.11
#Mann= 20 ,-1 , 0
-13994.6     .05       0-12749.9      .1       0  -10908      .1       0
-10008.9     .05       0 -8077.9     .05       0 -7486.1      .1       0
 -5942.7     .05       0 -4398.9      .1       0   -1699      .1       0
    42.9     .05       0   931.2      .1       0  1860.8     .05       0
  3276.8      .1       0  4748.4     .07       0  5118.6      .1       0
    5806      .1       0  7269.4      .1       0 13542.2      .1       0
 14504.7      .1       0 16041.7     .05       0
Bank Sta=4740,5087.9
XS Rating Curve= 0 ,0
Exp/Cntr=0.3,0.1

Type RM Length L Ch R = 1 ,445624  ,6179,6179,6179
BEGIN DESCRIPTION:
PEDERNALES RIVER 129.0
END DESCRIPTION:
XS GIS Cut Line= 3
       2773876.9     10064901.49      2773303.95     10049431.57
      2776813.38     10037374.55
#Sta/Elev= 30
  -11722 1693.05 -9277.7 1647.48 -7515.4 1634.24 -6460.4 1626.34 -5734.9 1624.39
 -3206.7 1597.02 -1423.5  1578.9  -545.2 1571.19  1084.5 1550.02  1224.6 1566.15
  1591.9 1564.71  3105.9 1554.38  3383.5 1567.77  3955.1 1579.49  4808.2  1567.1
  4839.4 1558.64  4971.2  1537.1  5616.4 1563.94  6372.3 1553.02    6723 1563.17
  7195.1  1562.2  7281.4 1576.16    8528 1580.76 11003.4 1609.61 13356.5 1670.16
 15168.5 1786.32 15548.1 1795.53 15779.9 1817.44 15931.4 1859.71 16315.9 1912.04
#Mann= 19 ,-1 , 0
  -11722     .05       0 -9277.7      .1       0 -7515.4      .1       0
 -6460.4     .05       0 -5734.9     .05       0 -3206.7      .1       0
 -1423.5      .1       0  -545.2     .05       0  1591.9      .1       0
  3383.5     .05       0  3955.1      .1       0  4808.2     .07       0
  5616.4      .1       0    6723      .1       0  7281.4      .1       0
    8528     .16       0 11003.4      .1       0 13356.5      .1       0
 15548.1      .1       0
Bank Sta=4839.4,5616.4
XS Rating Curve= 0 ,0
Exp/Cntr=0.3,0.1

Type RM Length L Ch R = 1 ,439445  ,3507,3507,3507
BEGIN DESCRIPTION:
PEDERNALES RIVER 130.0
END DESCRIPTION:
XS GIS Cut Line= 3
      2774476.24     10064691.68      2773908.47     10053291.09
      2780637.43     10039646.97
#Sta/Elev= 30
 -7701.7 1684.34 -5917.4 1656.29 -4760.1 1638.09 -4710.1 1628.75 -3531.4 1628.07
 -3101.6  1624.5  -834.7 1605.66   701.1 1592.89    3713 1575.67  4400.1 1558.67
  4747.2 1560.42  4831.4 1545.44    4837 1545.86  5016.4 1528.93  5226.5 1544.31
  5248.8 1546.97  6812.8 1558.83  8200.3 1569.25  9199.8 1572.71   11039 1596.87
 11993.5 1617.79 12797.5 1635.41 13374.8 1648.06 13575.4 1642.92 14299.1 1635.72
 15233.9 1629.46 16563.2 1653.42 17846.8 1712.48 18432.3 1774.79 18926.2 1781.17
#Mann= 20 ,-1 , 0
 -7701.7     .05       0 -5917.4      .1       0 -3531.4      .1       0
 -3101.6      .1       0  -834.7     .05       0   701.1      .1       0
  4400.1      .1       0  4831.4     .07       0  5226.5      .1       0
  6812.8     .05       0  8200.3     .05       0  9199.8      .1       0
   11039     .05       0 11993.5      .1       0 12797.5      .1       0
 13575.4      .1       0 14299.1      .1       0 15233.9      .1       0
 17846.8     .16       0 18432.3      .1       0
Bank Sta=4837,5248.8
XS Rating Curve= 0 ,0
Exp/Cntr=0.3,0.1

Type RM Length L Ch R = 1 ,435938  ,2088,2088,2088
BEGIN DESCRIPTION:
PEDERNALES RIVER 132.0
END DESCRIPTION:
XS GIS Cut Line= 3
      2775065.11     10065349.87      2778045.86     10047644.06
      2781398.47     10039547.39
#Sta/Elev= 30
 -9718.7 1662.52 -9706.2  1662.4 -7797.2 1644.05 -5716.5 1623.98 -5193.7 1615.94
 -3941.6 1590.26 -3209.1 1597.97   570.3 1583.39  1076.3 1577.07  1701.3 1569.26
  2402.7  1560.5  3672.5 1552.25  4122.4 1552.45  4900.3 1539.04  5021.7 1524.34
    5025 1524.84  5052.4  1542.9  5088.7 1547.09  5628.5 1568.03  6866.3 1571.96
  8580.7 1604.93    9218 1596.42 10113.2 1639.81 10476.5 1632.48 12890.7 1613.89
 14394.2 1664.13 14891.5 1658.53 16099.9 1739.93 16388.7  1726.3 16999.6 1754.79
#Mann= 20 ,-1 , 0
 -9718.7      .1       0 -9706.2     .05       0 -7797.2      .1       0
 -5716.5     .05       0 -5193.7      .1       0 -3209.1     .05       0
   570.3      .1       0  1076.3     .05       0  1701.3     .05       0
  2402.7      .1       0  3672.5     .05       0  4122.4      .1       0
  4900.3     .07       0    5025      .1       0  5088.7      .1       0
  6866.3      .1       0  8580.7     .05       0    9218      .1       0
 10476.5      .1       0 16099.9      .1       0
Bank Sta=4900.3,5052.4
XS Rating Curve= 0 ,0
Exp/Cntr=0.3,0.1

Type RM Length L Ch R = 1 ,433850  ,4349,4349,4349
BEGIN DESCRIPTION:
PEDERNALES RIVER 133.0
END DESCRIPTION:
XS GIS Cut Line= 4
      2775152.98     10065982.45      2778222.29     10053345.32
       2780524.3     10049622.89      2782406.94     10040374.12
#Sta/Elev= 30
 -9818.5 1660.36 -9173.5 1660.15 -7583.8 1655.61 -6272.4 1639.13 -5728.5 1629.86
   -4971 1616.95   -4648 1604.52   -4319 1608.57 -3114.4 1586.82 -2448.5 1593.26
 -1368.8 1595.08   -59.4 1587.88  1237.3 1569.11    2106 1561.53  4362.4 1550.44
  4667.4 1539.04  4986.6  1521.3  5124.8 1538.63  5151.9 1543.46  5246.5 1556.52
  6362.3 1559.87  8988.8 1573.22 10149.6 1591.62 12057.1 1621.86 13672.3 1658.55
 14572.5 1666.03 15572.4  1720.9 16378.1 1732.32   16631  1756.8 17001.2 1760.03
#Mann= 20 ,-1 , 0
 -9818.5      .1       0 -9173.5     .05       0 -7583.8      .1       0
 -6272.4      .1       0 -5728.5     .05       0   -4971      .1       0
   -4319      .1       0 -3114.4      .1       0 -2448.5     .05       0
 -1368.8     .05       0   -59.4      .1       0  1237.3      .1       0
    2106     .05       0  4667.4     .07       0  5151.9      .1       0
  6362.3     .05       0  8988.8     .05       0 10149.6      .1       0
 12057.1      .1       0 15572.4      .1       0
Bank Sta=4667.4,5124.8
XS Rating Curve= 0 ,0
Exp/Cntr=0.3,0.1

Type RM Length L Ch R = 1 ,429501  ,3781,3781,3781
BEGIN DESCRIPTION:
PEDERNALES RIVER 134.0
END DESCRIPTION:
XS GIS Cut Line= 3
      2776314.54     10068279.53      2781004.48     10050835.36
      2783568.56     10041230.24
#Sta/Elev= 30
 -8263.5 1658.26 -7909.4 1656.06 -5396.5 1636.58 -4343.7 1609.36 -4109.1 1629.54
 -2403.2 1622.07  1016.4 1577.52    2519 1558.65  2813.6 1566.26  3983.9 1531.13
  4094.6 1545.82  4479.9 1541.83  4866.9 1549.34  4996.8 1515.77  5038.5 1531.15
  5473.4 1528.33  5560.4 1552.15  5566.6 1546.42  6249.1 1546.25  9133.9 1551.53
  9992.8  1553.1 11086.2 1555.55 11866.6 1570.59 16073.1  1639.9 17372.6 1685.31
   17670 1706.74 18261.3 1701.46 18515.7 1695.56   19467 1800.22 19741.6 1804.36
#Mann= 19 ,-1 , 0
 -8263.5     .05       0 -7909.4      .1       0 -5396.5      .1       0
 -2403.2     .05       0  1016.4      .1       0    2519     .05       0
  2813.6      .1       0  4094.6      .1       0  4479.9     .05       0
  4866.9     .07       0  5560.4      .1       0  6249.1     .05       0
  9133.9      .1       0  9992.8     .05       0 11086.2      .1       0
 11866.6      .1       0 17372.6      .1       0 18261.3      .1       0
   19467      .1       0
Bank Sta=4866.9,5566.6
XS Rating Curve= 0 ,0
Exp/Cntr=0.3,0.1

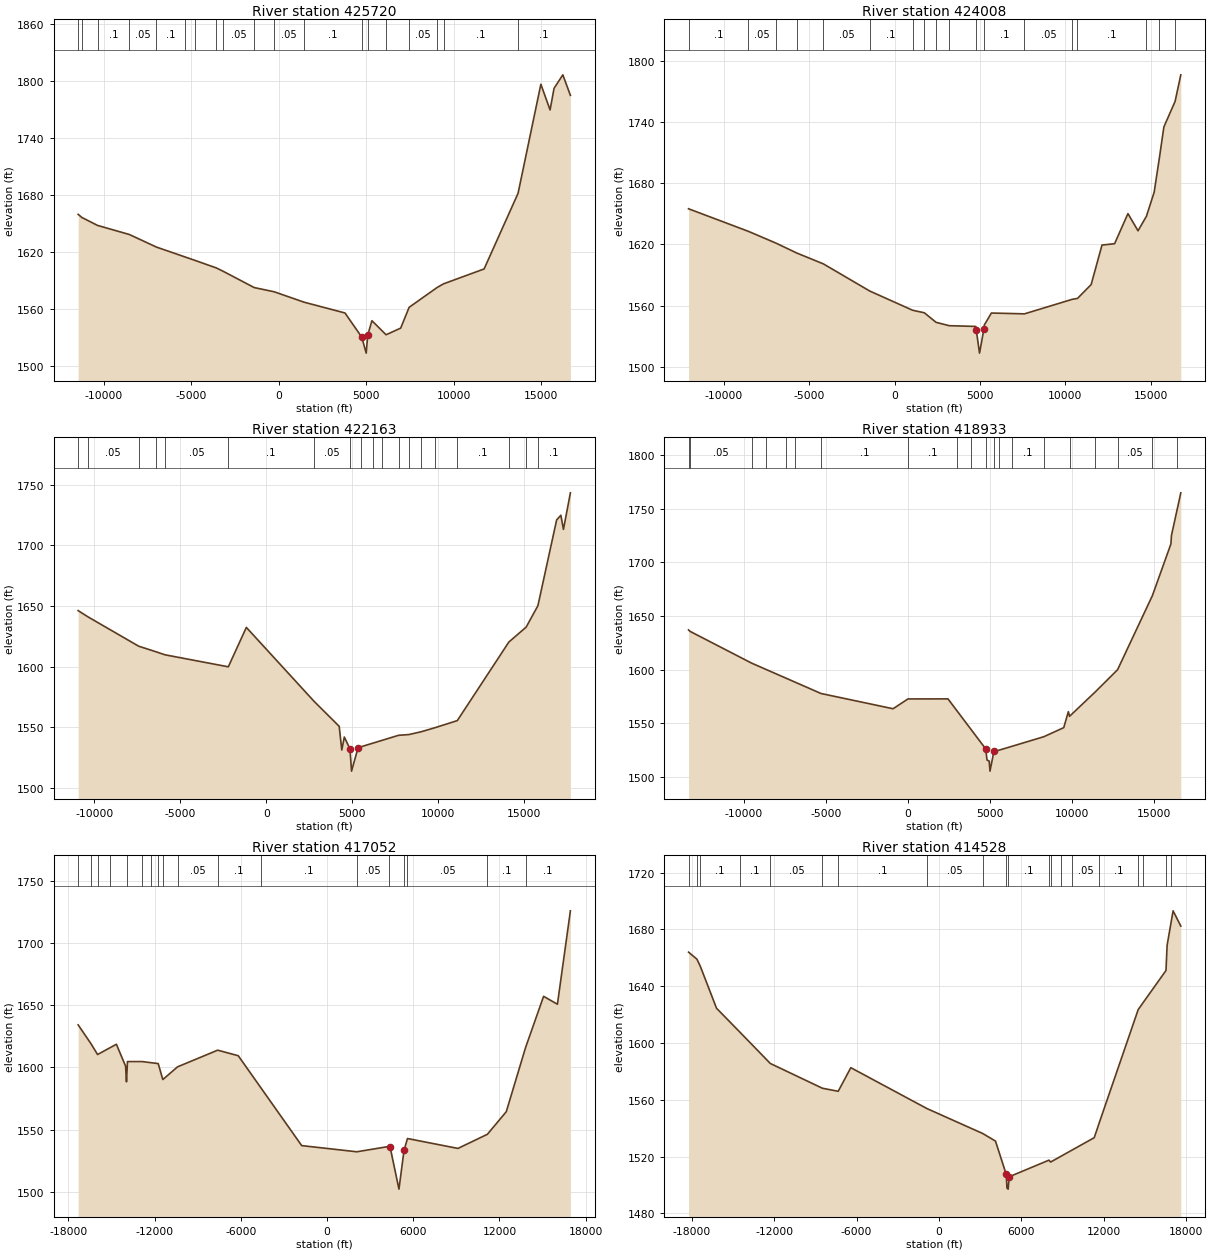
Type RM Length L Ch R = 1 ,425720  ,1712,1712,1712
BEGIN DESCRIPTION:
PEDERNALES RIVER 135.0
END DESCRIPTION:
XS GIS Cut Line= 3
      2777037.31     10068809.18      2780919.59     10057865.96
      2784343.75     10041710.01
#Sta/Elev= 30
-11456.5 1660.01-11249.3 1656.76-10345.9 1648.33 -8531.1  1638.8 -6983.4 1625.57
 -5331.9 1615.07 -4766.1 1611.47 -3559.3 1603.62 -3165.6 1600.06 -1397.3 1582.99
  -251.3 1578.52  1454.9 1567.59  3791.1 1556.24    4747 1530.88  5002.3 1514.02
  5091.3  1533.4  5096.4 1533.38  5329.4 1548.12  6137.6 1533.35  6972.2 1540.33
  7455.4  1562.2  9043.8 1582.93  9425.6 1586.94 11738.9 1602.56 13679.7 1682.14
 14982.4 1796.86 15508.3 1769.85 15735.8 1792.58 16238.1 1806.75 16669.8 1785.18
#Mann= 19 ,-1 , 0
-11456.5      .1       0-11249.3      .1       0-10345.9      .1       0
 -8531.1     .05       0 -6983.4      .1       0 -5331.9      .1       0
 -4766.1      .1       0 -3559.3      .1       0 -3165.6     .05       0
 -1397.3      .1       0  -251.3     .05       0  1454.9      .1       0
    4747     .07       0  5096.4      .1       0  6137.6      .1       0
  7455.4     .05       0  9043.8      .1       0  9425.6      .1       0
 13679.7      .1       0
Bank Sta=4747,5091.3
XS Rating Curve= 0 ,0
Exp/Cntr=0.3,0.1

Type RM Length L Ch R = 1 ,424008  ,1845,1845,1845
BEGIN DESCRIPTION:
PEDERNALES RIVER 136.0
END DESCRIPTION:
XS GIS Cut Line= 3
      2777551.19     10069388.29      2786601.61     10044548.39
      2786578.47      10042152.1
#Sta/Elev= 30
  -12074 1654.92 -8576.9 1632.88 -6957.6 1621.34 -5735.4 1611.61 -4176.8 1600.98
 -1462.3 1574.42  1052.2 1555.59  1735.9 1553.12    2424 1543.78  3191.7 1540.49
  4746.9 1539.75  4778.8  1536.3  4970.2 1513.63  5223.1 1536.87  5253.7 1541.27
  5665.7 1552.88  7602.2 1552.07   10408 1566.33   10708 1567.15 11508.3 1580.73
 12143.6  1619.4 12881.3 1620.73 13664.1 1650.19 14254.2 1633.37 14746.6 1647.61
   15198 1671.06 15499.9 1704.05   15768 1734.98 16424.2 1759.96 16759.7 1786.02
#Mann= 18 ,-1 , 0
  -12074      .1       0 -8576.9     .05       0 -6957.6      .1       0
 -5735.4      .1       0 -4176.8     .05       0 -1462.3      .1       0
  1052.2     .05       0  1735.9      .1       0    2424     .05       0
  3191.7      .1       0  4746.9     .07       0  5253.7      .1       0
  7602.2     .05       0   10408     .05       0   10708      .1       0
 14746.6     .16       0 15499.9      .1       0 16424.2     .05       0
Bank Sta=4778.8,5223.1
XS Rating Curve= 0 ,0
Exp/Cntr=0.3,0.1

Type RM Length L Ch R = 1 ,422163  ,3230,3230,3230
BEGIN DESCRIPTION:
PEDERNALES RIVER 137.0
END DESCRIPTION:
XS GIS Cut Line= 4
       2779115.4      10069250.9      2784640.43     10055983.72
      2785276.84      10050730.7      2787724.85     10042113.86
#Sta/Elev= 30
-10938.4 1646.28-10374.3  1641.2 -7422.5 1616.98 -6404.9 1612.33 -5893.5 1609.88
 -2207.6 1599.97 -1158.6 1632.45  2772.5 1571.61  4239.1 1550.92  4390.2  1531.4
  4537.8 1542.09  4863.6 1532.32  4875.3 1530.55    4957 1513.99    5337 1533.31
  5509.6 1534.06  6201.2 1537.06    6719  1539.3  7688.4  1543.5  8290.2 1544.13
  9012.4 1546.46  9798.7 1549.74   11106 1555.62 14102.9 1620.36 15111.7 1632.72
 15793.2 1650.34 16882.2 1721.03 17127.5 1724.88 17278.7 1713.25 17682.5 1743.36
#Mann= 19 ,-1 , 0
-10938.4      .1       0-10374.3     .05       0 -7422.5      .1       0
 -6404.9      .1       0 -5893.5     .05       0 -2207.6      .1       0
  2772.5     .05       0  4875.3     .07       0  5509.6     .05       0
  6201.2      .1       0    6719     .05       0  7688.4      .1       0
  8290.2     .05       0  9012.4      .1       0  9798.7      .1       0
   11106      .1       0 14102.9      .1       0 15111.7     .05       0
 15793.2      .1       0
Bank Sta=4863.6,5337
XS Rating Curve= 0 ,0
Exp/Cntr=0.3,0.1

Type RM Length L Ch R = 1 ,418933  ,1881,1881,1881
BEGIN DESCRIPTION:
PEDERNALES RIVER 144.0
END DESCRIPTION:
XS GIS Cut Line= 4
      2779702.67     10069501.08       2787162.9     10055571.46
      2788005.57     10046900.58      2788115.05     10041432.77
#Sta/Elev= 30
-13371.5 1637.06-13275.5 1635.69 -9526.2 1606.05 -8642.9 1600.13 -7432.5 1592.02
 -6876.3 1588.29 -5301.4 1577.74  -914.3 1563.52    -6.3 1572.67  2430.1 1572.72
  2958.4    1562  3849.9  1543.9  4728.6 1526.06  4808.8 1515.64  4939.6 1514.72
  4989.5 1505.32  5226.6 1523.75  5513.5 1524.75  6359.5 1528.62  8269.2 1537.43
  9480.9  1545.9  9762.2 1560.79  9835.9 1556.49   11383 1578.96 12759.5 1599.93
 14878.4 1668.98 16009.6 1717.31 16039.6 1725.03 16391.5 1749.63 16610.7 1764.96
#Mann= 20 ,-1 , 0
-13371.5      .1       0-13275.5     .05       0 -9526.2      .1       0
 -8642.9      .1       0 -7432.5      .1       0 -6876.3     .05       0
 -5301.4      .1       0    -6.3      .1       0  2958.4      .1       0
  3849.9     .05       0  4728.6     .07       0  5226.6      .1       0
  5513.5      .1       0  6359.5      .1       0  8269.2     .05       0
  9835.9      .1       0   11383     .05       0 12759.5     .05       0
 14878.4      .1       0 16391.5     .05       0
Bank Sta=4728.6,5226.6
XS Rating Curve= 0 ,0
Exp/Cntr=0.3,0.1

Type RM Length L Ch R = 1 ,417052  ,2524,2524,2524
BEGIN DESCRIPTION:
PEDERNALES RIVER 145.0
END DESCRIPTION:
XS GIS Cut Line= 5
      2778728.75     10072932.39      2785863.63     10064372.41
      2787372.15     10060223.79      2791520.23     10044543.86
      2791133.32       10042092.
#Sta/Elev= 30
-17321.2 1634.24-16431.8 1619.16  -15969  1610.4-15136.5 1615.65-14659.7 1618.65
-14020.6 1601.08-13956.8 1588.44-13888.6 1604.74-12870.9 1604.74-12279.9 1603.88
-11749.7 1603.11-11427.1 1590.28-10403.6 1600.49 -7610.3  1613.9 -6177.7 1609.43
   -4629 1584.08 -1763.2 1537.18  2074.5 1532.21  4343.3 1536.56  4391.5 1535.94
  5006.4 1502.19  5358.5 1533.37    5599 1542.87  9112.8 1534.91 11159.4 1546.27
   12475 1564.43 13821.4 1616.13 15072.8 1657.18 16034.8 1650.83 16938.3 1725.92
#Mann= 18 ,-1 , 0
-17321.2     .05       0-16431.8     .05       0  -15969      .1       0
-15136.5      .1       0-13888.6      .1       0-12870.9     .05       0
-12279.9      .1       0-11749.7     .16       0-11427.1      .1       0
-10403.6     .05       0 -7610.3      .1       0   -4629      .1       0
  2074.5     .05       0  4343.3     .07       0  5358.5     .16       0
    5599     .05       0 11159.4      .1       0 13821.4      .1       0
Bank Sta=4391.5,5358.5
XS Rating Curve= 0 ,0
Exp/Cntr=0.3,0.1

Type RM Length L Ch R = 1 ,414528  ,2964,2964,2964
BEGIN DESCRIPTION:
PEDERNALES RIVER 148.0
END DESCRIPTION:
XS GIS Cut Line= 4
      2785393.64     10076375.74      2790694.06     10064460.21
      2791986.66     10048016.65      2792114.89      10041717.2
#Sta/Elev= 30
-18228.3 1663.96-17619.8 1659.03-17379.9  1654.2-16191.2 1624.46-14483.6 1607.57
-12275.6 1585.57 -8482.7 1568.13 -7333.2 1565.99   -6415 1582.61  -880.6 1553.86
  3188.7 1536.25  4116.8 1530.93  4900.5 1507.46  4950.6 1497.92  5040.6 1497.09
  5043.9 1497.59  5111.1 1505.78    8010 1517.49  8130.3 1516.16  8866.1 1520.14
    9687 1524.57 11306.2 1533.32   11689  1544.3 14504.3 1623.46 14821.7 1627.83
 16529.2 1651.02 16611.3 1668.78 16859.1  1682.6 17046.5 1693.06   17608 1682.35
#Mann= 20 ,-1 , 0
-18228.3      .1       0-17619.8     .16       0-17379.9      .1       0
-14483.6      .1       0-12275.6     .05       0 -8482.7     .16       0
 -7333.2      .1       0  -880.6     .05       0  3188.7      .1       0
  4900.5     .07       0  5043.9      .1       0    8010      .1       0
  8130.3     .05       0  8866.1      .1       0    9687     .05       0
   11689      .1       0 14504.3     .05       0 14821.7      .1       0
 16529.2     .16       0 16859.1      .1       0
Bank Sta=4900.5,5111.1
XS Rating Curve= 0 ,0
Exp/Cntr=0.3,0.1

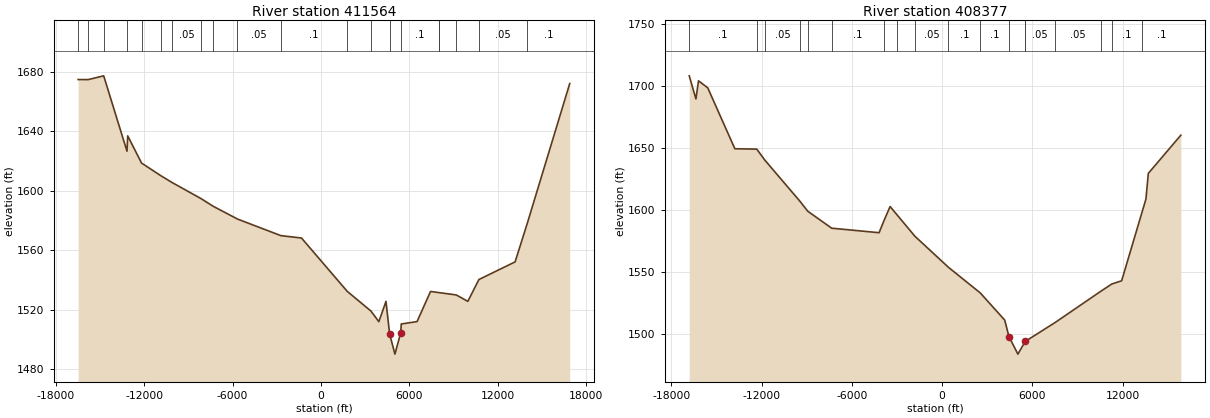
Type RM Length L Ch R = 1 ,411564  ,3187,3187,3187
BEGIN DESCRIPTION:
PEDERNALES RIVER 150.0
END DESCRIPTION:
XS GIS Cut Line= 4
      2792859.27     10074505.42      2793153.26     10063838.61
      2794173.95     10056755.62      2793866.53     10041240.98
#Sta/Elev= 30
-16476.1 1674.63-15795.3 1674.57-14741.8 1677.12-13160.9 1626.46-13113.1  1636.8
  -12174 1618.51-10884.2 1610.13-10119.5 1605.53 -8138.6 1594.61 -7337.8 1589.59
 -5670.8  1580.9 -2729.5 1569.75 -1324.5 1568.12  1783.6 1532.23  3380.2 1519.11
  3923.3 1511.93  4406.2 1525.55  4653.5 1503.65  5013.3  1490.1  5403.6 1504.43
  5443.6 1510.35  6513.8 1511.97    7429 1532.22  7991.1 1531.46  9179.1 1529.86
    9958 1525.56 10708.3 1540.22 13165.1  1552.1 13985.5 1577.84 16868.6 1671.91
#Mann= 20 ,-1 , 0
-16476.1      .1       0-15795.3      .1       0-14741.8      .1       0
-13160.9      .1       0  -12174     .05       0-10884.2      .1       0
-10119.5     .05       0 -8138.6      .1       0 -7337.8      .1       0
 -5670.8     .05       0 -2729.5      .1       0  1783.6      .1       0
  3380.2      .1       0  4653.5     .07       0  5443.6      .1       0
  7991.1     .05       0  7991.1      .1       0  9179.1     .05       0
 10708.3     .05       0 13985.5      .1       0
Bank Sta=4653.5,5403.6
XS Rating Curve= 0 ,0
Exp/Cntr=0.3,0.1

Type RM Length L Ch R = 1 ,408377  ,3423,3423,3423
BEGIN DESCRIPTION:
PEDERNALES RIVER 152.0
END DESCRIPTION:
XS GIS Cut Line= 3
      2794233.74     10072525.04      2797431.27     10054876.37
      2794186.79     10040513.25
#Sta/Elev= 30
-16801.7 1708.08-16356.4 1689.47-16185.9 1704.05-15572.5 1698.45-13770.5  1649.4
-12313.7 1649.11-11796.3 1640.52 -9437.5 1607.03 -8926.3 1599.13 -7336.6 1585.48
 -4188.3 1581.85 -3876.7 1591.16 -3457.4 1602.91 -2990.8 1596.15 -1807.1 1578.99
   423.2 1553.99  2538.8 1533.34  4160.7  1511.5  4440.3 1498.19  4470.8 1497.62
  5032.5 1484.15  5523.8 1494.39  7513.3 1509.64 10567.2 1534.93 11279.7 1540.61
 11926.6 1543.15 13291.9 1598.79 13541.9 1608.99 13698.4 1629.58 15859.3 1660.31
#Mann= 18 ,-1 , 0
-16801.7      .1       0-12313.7      .1       0-11796.3     .05       0
 -9437.5      .1       0 -8926.3     .05       0 -7336.6      .1       0
 -3876.7      .1       0 -2990.8      .1       0 -1807.1     .05       0
   423.2      .1       0  2538.8      .1       0  4440.3     .07       0
  5523.8      .1       0  5523.8     .05       0  7513.3     .05       0
 10567.2      .1       0 11279.7      .1       0 13291.9      .1       0
Bank Sta=4470.8,5523.8
XS Rating Curve= 0 ,0
Exp/Cntr=0.3,0.1