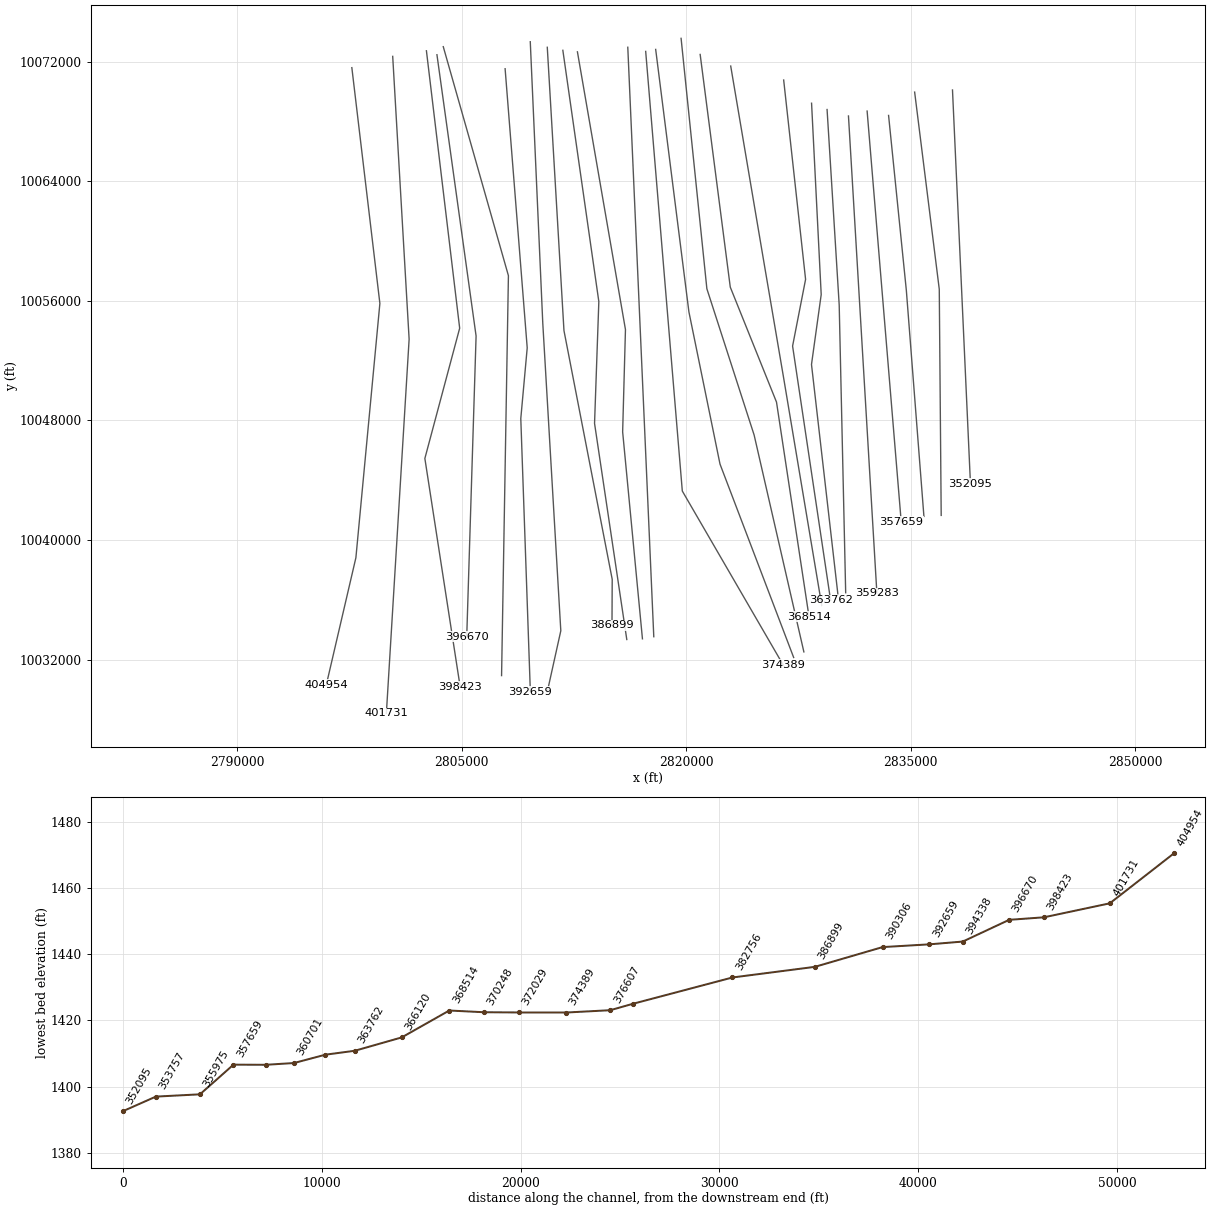
HEC-RAS study PEDERNALES RIVER.prj: PEDERNALES RIVER Base Level Engineering

--- PEDERNALES RIVER.g02 (geometry) --- (continued)

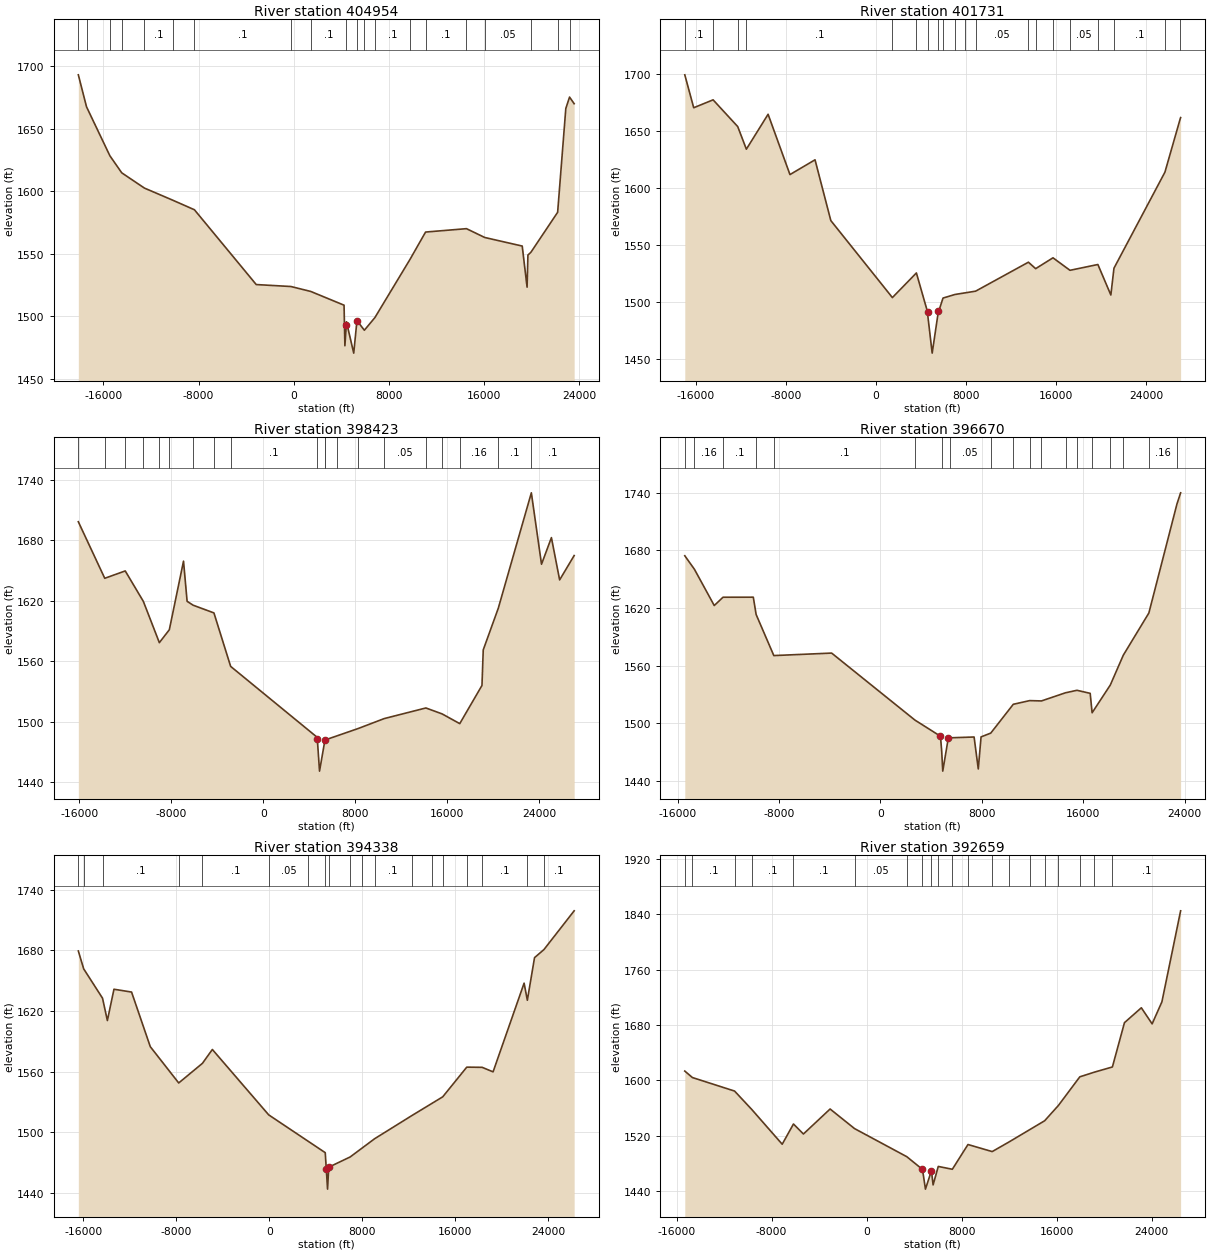
Type RM Length L Ch R = 1 ,404954  ,3223,3223,3223
BEGIN DESCRIPTION:
PEDERNALES RIVER 154.0
END DESCRIPTION:
XS GIS Cut Line= 4
      2797663.12     10071589.93       2799535.8     10055824.19
      2797933.69      10038820.2      2795953.64     10030307.92
#Sta/Elev= 30
-18115.3 1693.04-17426.5 1667.47-15460.6 1628.26-14463.6 1614.64-12558.3 1602.45
-10154.4 1592.67   -8352  1585.1 -3154.7 1525.27  -242.4 1523.71    1427 1519.77
  4230.2 1508.77  4300.6 1476.31  4421.1 1493.32  4431.1 1495.46  5043.6 1470.42
    5315 1496.43  5937.3 1488.73  6822.7 1498.84  9776.9 1545.42 11085.1 1567.27
 14524.6 1569.98 16060.8 1562.93 19213.5 1556.06 19621.3 1523.18 19692.4  1548.9
 19937.3 1551.02 22191.4 1583.08 22877.9 1666.08 23192.6 1675.23 23580.1 1669.95
#Mann= 20 ,-1 , 0
-18115.3      .1       0-17426.5     .05       0-15460.6      .1       0
-14463.6      .1       0-12558.3      .1       0-10154.4      .1       0
   -8352      .1       0  -242.4     .05       0    1427      .1       0
  4431.1     .07       0    5315      .1       0  5937.3     .05       0
  6822.7      .1       0  9776.9      .1       0 11085.1      .1       0
 14524.6     .05       0 16060.8     .05       0 19937.3     .05       0
 22191.4     .16       0 23192.6      .1       0
Bank Sta=4421.1,5315
XS Rating Curve= 0 ,0
Exp/Cntr=0.3,0.1

Type RM Length L Ch R = 1 ,401731  ,3308,3308,3308
BEGIN DESCRIPTION:
PEDERNALES RIVER 156.0
END DESCRIPTION:
XS GIS Cut Line= 3
      2800392.65     10072344.35      2801489.62     10053433.16
      2799969.35     10028412.88
#Sta/Elev= 30
-16957.7 1699.31-16165.8 1670.46-14445.3 1677.38-12258.6 1653.92-11492.8 1634.11
 -9564.7 1664.73 -7622.5 1611.86 -5397.7 1624.81 -3996.3 1571.53  1468.2 1504.03
  3598.9 1525.62  4589.5 1491.46  4609.5 1488.31    5000 1455.34  5547.7 1491.86
  5552.7 1491.19  5961.8 1503.61  7020.1 1506.75  7915.2 1508.17  8856.7 1509.66
 13541.3 1535.05 14185.2 1529.39 15722.7  1538.9 17233.1 1527.94 19707.9 1533.03
 20859.5  1506.3 21134.8 1529.78 25659.2 1613.98   27018 1660.86 27051.7 1661.82
#Mann= 20 ,-1 , 0
-16957.7      .1       0-14445.3      .1       0-12258.6      .1       0
-11492.8      .1       0  1468.2      .1       0  3598.9      .1       0
  4609.5     .07       0  5552.7      .1       0  5961.8      .1       0
  7020.1     .05       0  7915.2     .05       0  8856.7     .05       0
 13541.3      .1       0 14185.2     .05       0 15722.7     .05       0
 17233.1     .05       0 19707.9     .05       0 21134.8      .1       0
 25659.2      .1       0   27018     .16       0
Bank Sta=4589.5,5547.7
XS Rating Curve= 0 ,0
Exp/Cntr=0.3,0.1

Type RM Length L Ch R = 1 ,398423  ,1753,1753,1753
BEGIN DESCRIPTION:
PEDERNALES RIVER 157.0
END DESCRIPTION:
XS GIS Cut Line= 4
      2802645.14     10072718.76      2804866.32     10054168.52
      2802541.05     10045459.28      2804895.98     10030208.79
#Sta/Elev= 30
  -16089 1698.46-13790.4 1642.39-12008.6 1649.69-10432.2 1619.46 -9041.5 1578.55
 -8174.3 1591.34 -6939.5 1659.39 -6626.9 1619.55   -6106 1615.71 -4293.5 1608.04
   -2840 1555.01  4689.5 1484.64  4696.4 1483.36  4891.4 1451.12  5343.7 1480.74
  5357.2 1481.95  6384.3    1486  8253.8 1493.38 10519.7 1503.24 14141.4 1513.77
 15551.5 1507.89 17088.9 1498.23 19020.4 1536.09 19131.7 1571.38 20439.4 1612.68
 23315.9 1727.16 24200.6 1656.33 25061.6 1682.73 25776.2 1640.78 27039.3 1664.94
#Mann= 20 ,-1 , 0
  -16089      .1       0-13790.4      .1       0-12008.6      .1       0
-10432.2     .05       0 -9041.5      .1       0 -8174.3      .1       0
   -6106      .1       0 -4293.5      .1       0   -2840      .1       0
  4689.5     .07       0  5343.7      .1       0  5343.7      .1       0
  6384.3     .05       0  8253.8      .1       0 10519.7     .05       0
 14141.4     .05       0 15551.5     .05       0 17088.9     .16       0
 20439.4      .1       0 23315.9      .1       0
Bank Sta=4696.4,5357.2
XS Rating Curve= 0 ,0
Exp/Cntr=0.3,0.1

Type RM Length L Ch R = 1 ,396670  ,2332,2332,2332
BEGIN DESCRIPTION:
PEDERNALES RIVER 163.0
END DESCRIPTION:
XS GIS Cut Line= 3
      2803347.99     10072454.89      2805962.94     10053648.94
      2805338.26     10033544.53
#Sta/Elev= 30
-15426.2 1674.29-14663.7 1660.17-13102.9 1622.52-12412.7 1631.15-10023.6 1631.21
 -9800.7 1613.22 -8405.7  1570.5 -3845.7 1573.09  2718.4 1503.46  4736.5 1486.64
  4831.6 1471.34  4916.3 1450.35  5356.8 1484.94  5452.1 1484.98  7387.7 1485.83
  7717.9 1452.59    7938 1485.94  8703.9  1489.9 10477.7 1519.84 11772.5 1523.67
 12700.1 1523.33 14599.2 1531.82 15498.7 1534.39 16542.2 1531.24 16695.5 1511.02
 18130.4 1539.89 19154.7  1570.9 21170.3 1614.76 23387.4 1728.22 23674.8 1739.72
#Mann= 19 ,-1 , 0
-15426.2      .1       0-14663.7     .16       0-12412.7      .1       0
 -9800.7     .05       0 -8405.7      .1       0  2718.4     .05       0
  4831.6     .07       0  5452.1     .05       0  8703.9      .1       0
 10477.7     .05       0 11772.5      .1       0 12700.1      .1       0
 14599.2      .1       0 15498.7      .1       0 16695.5     .16       0
 18130.4      .1       0 19154.7      .1       0 21170.3     .16       0
 23387.4      .1       0
Bank Sta=4736.5,5356.8
XS Rating Curve= 0 ,0
Exp/Cntr=0.3,0.1

Type RM Length L Ch R = 1 ,394338  ,1679,1679,1679
BEGIN DESCRIPTION:
PEDERNALES RIVER 158.0
END DESCRIPTION:
XS GIS Cut Line= 3
      2803770.31     10072992.87      2808122.58     10057680.36
       2807665.2      10030937.8
#Sta/Elev= 30
-16424.8 1679.36-15963.5 1661.67  -14343 1632.67-13925.7 1610.55-13358.8 1641.52
-11843.7 1638.72-10233.3 1584.71   -7787  1548.8   -5745 1568.23 -4891.5 1581.93
   -42.8 1517.24  3349.6 1491.16  4821.6 1479.85  4911.6 1463.78  5021.4 1443.79
  5121.7 1465.48  6966.7 1475.61  7974.1 1484.24  9066.8  1493.6 12268.7  1516.5
 14006.5 1528.63 14931.9 1535.09   17000 1564.45 18321.4 1564.27 19263.7  1559.8
 21934.1 1647.54 22212.2 1630.61 22831.4 1672.76 23638.1 1680.72 26240.7 1719.08
#Mann= 19 ,-1 , 0
-16424.8     .16       0-15963.5     .16       0  -14343      .1       0
   -7787      .1       0   -5745      .1       0   -42.8     .05       0
  3349.6      .1       0  4821.6     .07       0  5121.7     .05       0
  6966.7     .05       0  7974.1      .1       0  9066.8      .1       0
 12268.7     .05       0 14006.5      .1       0 14931.9     .05       0
   17000     .05       0 18321.4      .1       0 22212.2     .16       0
 23638.1      .1       0
Bank Sta=4911.6,5121.7
XS Rating Curve= 0 ,0
Exp/Cntr=0.3,0.1

Type RM Length L Ch R = 1 ,392659  ,2353,2353,2353
BEGIN DESCRIPTION:
PEDERNALES RIVER 173.0
END DESCRIPTION:
XS GIS Cut Line= 4
      2807901.95     10071518.02      2809378.08     10052854.51
      2808949.21     10048126.81      2809587.08     10029869.25
#Sta/Elev= 30
-15306.8 1613.52-14665.6 1604.16-11116.6 1584.63 -9659.2 1557.84   -7107 1507.82
 -6159.7 1537.05 -5321.4 1522.59 -3074.4 1558.71 -1019.8 1530.43  3379.6 1489.82
    4701 1471.45  4951.8 1442.95  5453.8  1469.5  5594.7 1449.09  6030.1 1475.73
  7214.3 1471.65  8530.2 1507.39 10568.8 1497.19 11967.4 1510.91 13715.8 1528.76
 14984.2 1541.71 16150.1 1563.96 17945.1  1605.2 19178.6 1611.98 20687.4 1619.43
 21703.4 1683.44 23124.3 1704.94   24033 1681.72 24855.4 1713.53 26430.8 1845.02
#Mann= 20 ,-1 , 0
-15306.8      .1       0-14665.6      .1       0-11116.6     .05       0
 -9659.2      .1       0 -6159.7      .1       0 -1019.8     .05       0
  3379.6     .05       0    4701     .07       0  5453.8     .05       0
  6030.1      .1       0  7214.3      .1       0  8530.2     .05       0
 10568.8      .1       0 11967.4     .05       0 13715.8      .1       0
 14984.2     .05       0 16150.1     .05       0 17945.1      .1       0
 19178.6      .1       0 20687.4      .1       0
Bank Sta=4701,5453.8
XS Rating Curve= 0 ,0
Exp/Cntr=0.3,0.1

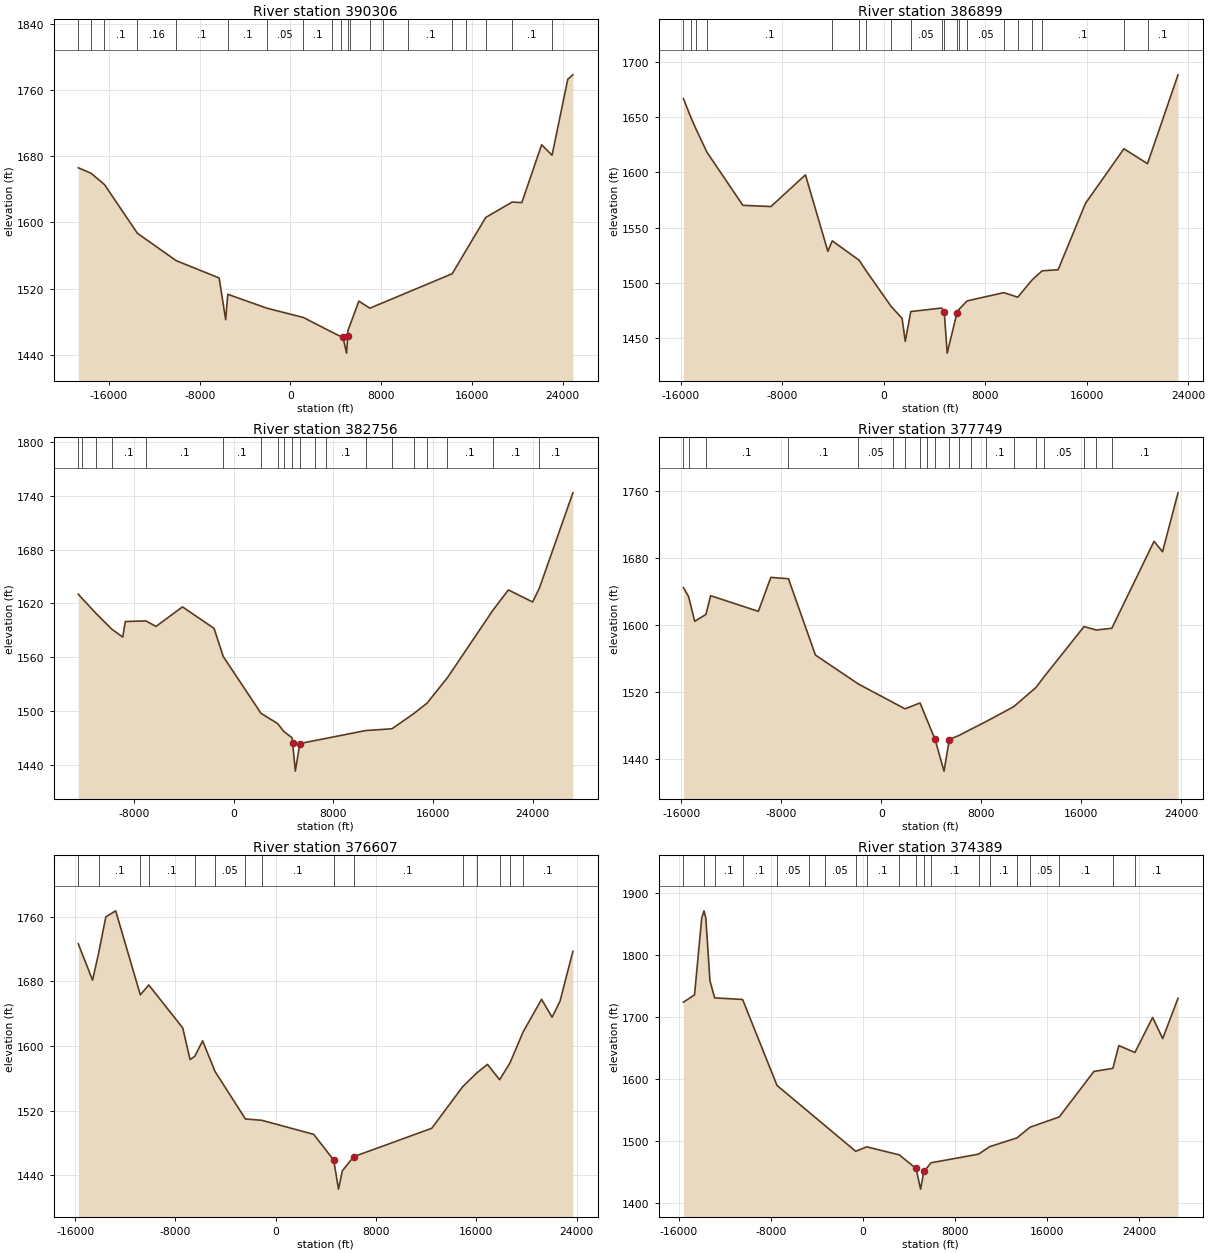
Type RM Length L Ch R = 1 ,390306  ,3407,3407,3407
BEGIN DESCRIPTION:
PEDERNALES RIVER 161.0
END DESCRIPTION:
XS GIS Cut Line= 4
      2809582.46     10073323.63      2810418.22     10054496.19
      2811622.25     10033936.43      2810717.27     10029847.03
#Sta/Elev= 30
-18716.8 1665.94-17593.3  1659.3-16406.7 1645.71-13500.6 1586.84-10075.9 1553.76
 -6290.7 1532.89 -5714.1 1482.45 -5529.4 1513.14 -2077.1 1496.38  1136.7 1485.17
  3691.9 1467.24  4494.7 1461.85  4639.4 1461.18  4949.6 1442.12  5050.1 1462.73
  5060.1 1468.97    5208 1474.41  6035.7 1504.86  7006.4 1496.39  8156.2 1502.98
 10401.5 1515.84 14267.6 1537.99   15463 1565.54 17223.8 1605.91 19555.3 1624.54
 20407.1 1623.82 22154.5 1693.73 23074.8 1681.08 24463.7 1772.87 24912.5 1778.15
#Mann= 20 ,-1 , 0
-18716.8      .1       0-17593.3      .1       0-16406.7      .1       0
-13500.6     .16       0-10075.9      .1       0 -5529.4      .1       0
 -2077.1     .05       0  1136.7      .1       0  3691.9      .1       0
  4494.7     .07       0  5060.1      .1       0    5208      .1       0
  7006.4     .05       0  8156.2     .05       0 10401.5      .1       0
 14267.6      .1       0   15463     .05       0 17223.8      .1       0
 19555.3      .1       0 23074.8      .1       0
Bank Sta=4639.4,5050.1
XS Rating Curve= 0 ,0
Exp/Cntr=0.3,0.1

Type RM Length L Ch R = 1 ,386899  ,4143,4143,4143
BEGIN DESCRIPTION:
PEDERNALES RIVER 167.0
END DESCRIPTION:
XS GIS Cut Line= 4
      2810718.33     10072952.21      2811833.35     10054006.53
      2815055.92     10037377.79      2815041.08     10034304.41
#Sta/Elev= 30
-15795.4 1667.01-15212.6 1650.16-14766.6 1638.53-13939.7 1618.39-11108.1 1570.22
 -8894.8  1569.1 -6175.8 1597.86 -4407.2 1528.45 -4063.9 1538.02   -1943 1520.41
 -1380.6 1510.65   580.3 1478.51  1442.9  1467.7  1693.3 1446.86  2127.6 1473.89
  4560.1 1477.02  4765.2 1473.86  4998.8 1436.15  5763.6 1472.35  5894.9 1475.46
  6570.7 1483.53  9466.3 1491.03 10562.2 1486.85 11672.7 1502.31 12471.4 1510.75
 13746.1 1511.84 15898.1 1571.98 18930.1 1621.51 20788.7    1608 23194.6 1688.58
#Mann= 20 ,-1 , 0
-15795.4      .1       0-15212.6      .1       0-14766.6     .05       0
-13939.7      .1       0 -4063.9      .1       0   -1943     .16       0
 -1380.6      .1       0   580.3      .1       0  2127.6     .05       0
  4560.1      .1       0  4765.2     .07       0  5763.6      .1       0
  5894.9      .1       0  6570.7     .05       0  9466.3     .05       0
 10562.2      .1       0 11672.7     .05       0 12471.4      .1       0
 18930.1      .1       0 20788.7      .1       0
Bank Sta=4765.2,5763.6
XS Rating Curve= 0 ,0
Exp/Cntr=0.3,0.1

Type RM Length L Ch R = 1 ,382756  ,5007,5007,5007
BEGIN DESCRIPTION:
PEDERNALES RIVER 169.0
END DESCRIPTION:
XS GIS Cut Line= 4
      2811758.52     10072750.07      2814162.23      10055948.5
      2813875.92     10047804.55      2816029.78     10033351.08
#Sta/Elev= 30
-12492.5 1630.28-12188.8 1625.48-11047.2 1608.52   -9823 1591.49 -8920.2 1582.34
 -8714.2 1599.69 -7066.9 1600.45 -6246.1 1594.29 -4121.2 1616.07 -1582.4 1592.06
  -846.7 1560.74  2189.1 1497.38  3522.8 1485.99  4005.5 1477.35    4695 1469.96
  4724.9 1464.83  4944.9 1432.94  5305.4  1463.7  6518.4 1467.02  7444.6 1469.55
 10583.5 1478.14 12712.8 1480.21 14449.6 1496.98 15524.3  1508.7 17163.3 1537.12
 20828.2 1612.53   22063 1634.94 24009.9  1621.5 24555.5 1637.15 27242.2  1743.2
#Mann= 20 ,-1 , 0
-12492.5      .1       0-12188.8      .1       0-11047.2     .05       0
   -9823      .1       0 -7066.9      .1       0  -846.7      .1       0
  2189.1      .1       0  3522.8      .1       0  4005.5     .05       0
    4695     .07       0  5305.4      .1       0  6518.4      .1       0
  7444.6      .1       0 10583.5     .05       0 12712.8      .1       0
 14449.6     .05       0 15524.3     .05       0 17163.3      .1       0
 20828.2      .1       0 24555.5      .1       0
Bank Sta=4724.9,5305.4
XS Rating Curve= 0 ,0
Exp/Cntr=0.3,0.1

Type RM Length L Ch R = 1 ,377749  ,1142,1142,1142
BEGIN DESCRIPTION:
PEDERNALES RIVER 171.0
END DESCRIPTION:
XS GIS Cut Line= 4
      2812732.11     10072647.22      2815941.29     10054076.34
      2815752.91      10047237.7      2817075.75     10033398.34
#Sta/Elev= 30
  -15837 1644.74-15426.1 1634.03-14930.3 1604.34-14037.7 1612.53-13656.4 1635.02
   -9840 1616.28 -8838.5 1656.94 -7429.9 1655.29 -5269.2 1563.94 -1828.2 1529.25
     927 1507.34  1898.1 1499.54  3104.5 1506.61  3629.5 1487.44 4295.75 1463.48
  5022.2 1424.99  5382.6 1457.11  5422.7 1462.83  6198.3 1467.56  7220.3  1475.4
  8398.7 1484.43 10584.3 1501.99 12382.4 1525.08 13014.3 1537.63 16229.1 1598.02
 17222.8 1593.93 18456.2 1596.03 21835.4 1700.16 22511.8 1687.61 23752.8 1758.16
#Mann= 20 ,-1 , 0
  -15837     .05       0-15426.1      .1       0-14037.7      .1       0
 -7429.9      .1       0 -1828.2     .05       0     927     .05       0
  1898.1      .1       0  3104.5      .1       0  3629.5     .05       0
 4295.75     .07       0  5382.6      .1       0  6198.3     .05       0
  7220.3      .1       0  8398.7      .1       0 10584.3      .1       0
 12382.4      .1       0 13014.3     .05       0 16229.1      .1       0
 17222.8     .05       0 18456.2      .1       0
Bank Sta=4295.75,5422.7
XS Rating Curve= 0 ,0
Exp/Cntr=0.3,0.1

Type RM Length L Ch R = 1 ,376607  ,2218,2218,2218
BEGIN DESCRIPTION:
PEDERNALES RIVER 175.0
END DESCRIPTION:
XS GIS Cut Line= 2
      2816096.61     10072954.17      2817833.24     10033538.01
#Sta/Elev= 30
-15753.4  1726.4-14611.9 1681.52-14125.6 1715.21-13554.4 1759.76-12770.1 1767.22
-10804.1 1663.34-10128.2 1675.52 -7419.4 1622.37 -6834.3 1583.22 -6457.3 1587.41
 -5833.4 1606.45 -4845.7 1568.61 -2420.2 1509.83   -1106 1508.14  3025.2 1490.81
    4622 1458.95  5006.9 1423.05  5308.1 1445.69  6212.9 1463.14 12444.4 1498.31
 14901.9 1549.58 16036.2 1566.78   16887  1577.3 17858.3 1558.34   18681 1579.05
 19733.3  1617.5 21202.4 1657.78 22043.7 1635.65 22674.3  1655.5   23701 1717.11
#Mann= 15 ,-1 , 0
-15753.4     .16       0-14125.6      .1       0-10804.1     .16       0
-10128.2      .1       0 -6457.3      .1       0 -4845.7     .05       0
 -2420.2      .1       0   -1106      .1       0    4622     .07       0
  6212.9      .1       0 14901.9      .1       0 16036.2      .1       0
 17858.3      .1       0   18681      .1       0 19733.3      .1       0
Bank Sta=4622,6212.9
XS Rating Curve= 0 ,0
Exp/Cntr=0.3,0.1

Type RM Length L Ch R = 1 ,374389  ,2360,2360,2360
BEGIN DESCRIPTION:
PEDERNALES RIVER 177.0
END DESCRIPTION:
XS GIS Cut Line= 3
      2817292.23     10072676.26      2819738.83      10043279.4
      2826480.51     10031645.27
#Sta/Elev= 30
-15577.2 1723.55-14611.3 1735.46-13989.2 1858.65-13788.6 1870.84-13633.1 1859.56
-13271.6 1758.16-12867.1 1730.55-10438.2 1727.98 -7450.2 1589.45 -4630.2 1545.66
 -3314.7 1525.23  -619.1 1483.37   344.1 1490.49  3161.6 1477.59  4624.9 1455.63
    5016 1422.35  5299.2 1450.76  5929.9 1464.83 10048.3 1478.72 11011.6 1490.78
 13378.2 1504.85 14520.8 1522.12 17052.5 1538.64 20064.9 1612.01 21713.4 1617.02
 22224.1 1653.67 23626.3 1642.59 25163.6 1699.12 26035.8 1665.01 27367.6 1729.87
#Mann= 20 ,-1 , 0
-15577.2      .1       0-13788.6      .1       0-12867.1      .1       0
-10438.2      .1       0 -7450.2     .05       0 -4630.2     .05       0
 -3314.7     .05       0  -619.1     .05       0   344.1      .1       0
  3161.6      .1       0  4624.9     .07       0  5299.2      .1       0
  5929.9      .1       0 10048.3      .1       0 11011.6      .1       0
 13378.2     .05       0 14520.8     .05       0 17052.5      .1       0
 21713.4      .1       0 23626.3      .1       0
Bank Sta=4624.9,5299.2
XS Rating Curve= 0 ,0
Exp/Cntr=0.3,0.1

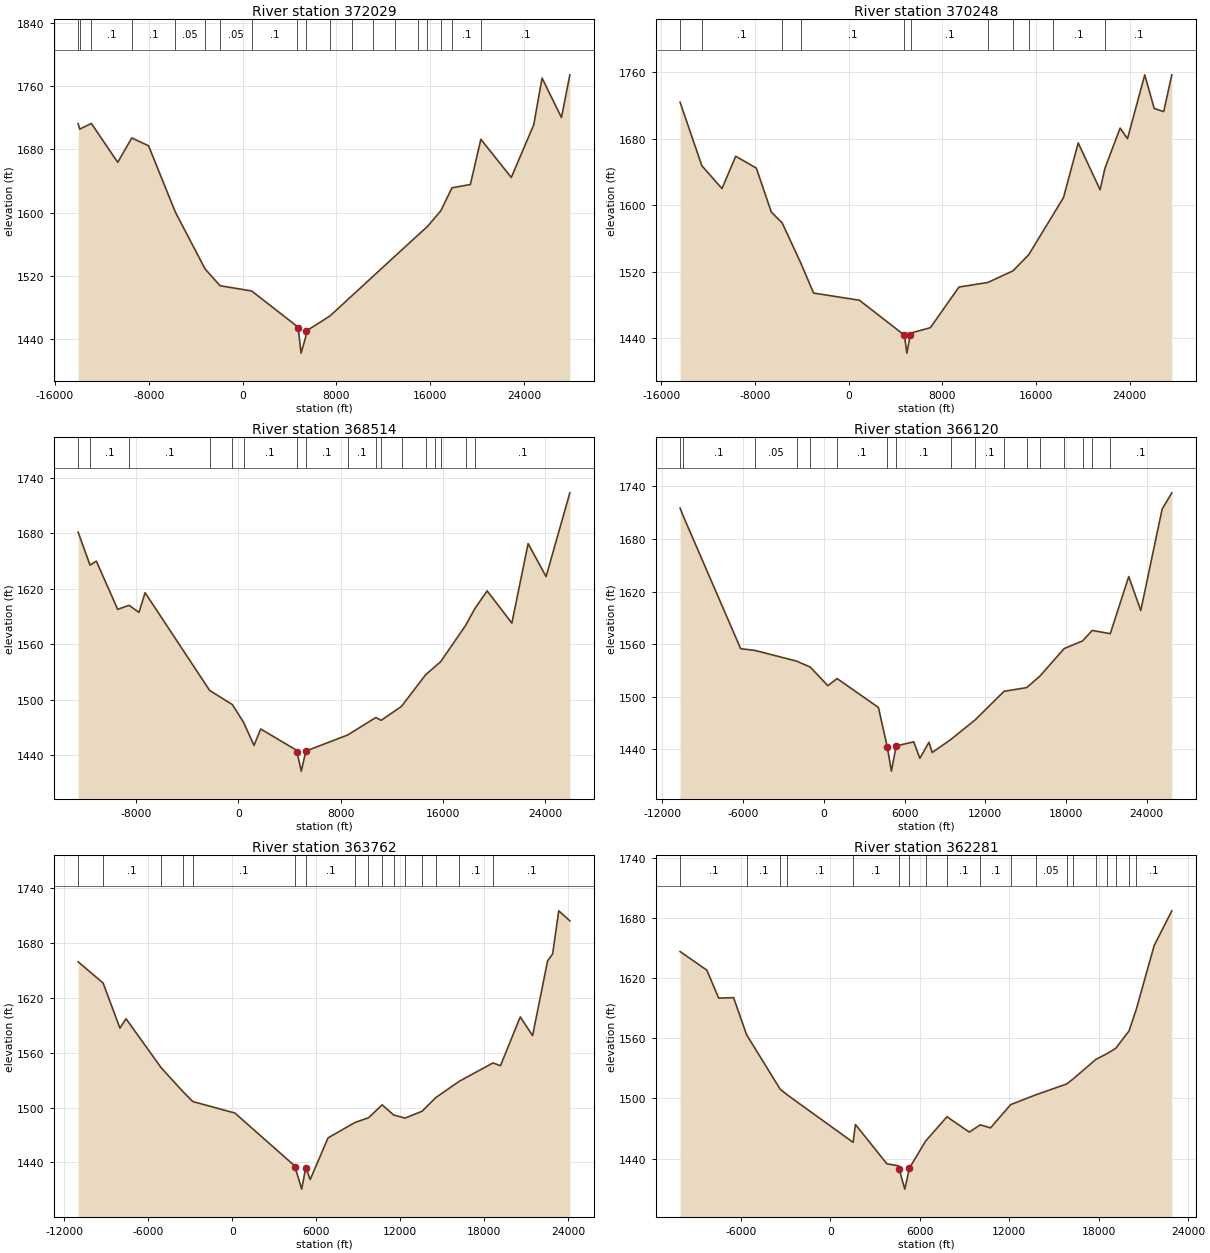
Type RM Length L Ch R = 1 ,372029  ,1781,1781,1781
BEGIN DESCRIPTION:
PEDERNALES RIVER 179.0
END DESCRIPTION:
XS GIS Cut Line= 4
      2817959.75      10072809.1      2820180.08      10055257.2
      2822256.75      10045082.1      2827177.43     10032148.46
#Sta/Elev= 30
-14020.6 1712.35-13881.5 1705.43-12890.3 1712.63  -10644 1663.47 -9451.6 1694.25
 -8018.9 1684.47 -5736.9 1600.72   -3199 1528.75 -1917.2 1507.52   767.9 1500.95
  4638.7 1456.29  4739.8 1454.26  4980.9 1422.37  5379.1 1442.77  5399.6 1450.11
  7445.6 1469.32  9337.8 1495.13 11083.3 1518.94 13008.5 1545.21 14970.1 1571.81
   15745 1582.24 16897.5 1602.33 17847.2 1631.31 19413.7 1635.46 20307.1 1692.62
 22901.3 1644.35   24815 1710.88   25525 1769.94 27178.4 1720.12 27894.1 1774.06
#Mann= 19 ,-1 , 0
-14020.6     .16       0-13881.5      .1       0-12890.3      .1       0
 -9451.6      .1       0 -5736.9     .05       0   -3199      .1       0
 -1917.2     .05       0   767.9      .1       0  4638.7     .07       0
  5379.1      .1       0  7445.6     .05       0  9337.8      .1       0
 11083.3     .05       0 13008.5      .1       0 14970.1     .05       0
   15745      .1       0 16897.5     .05       0 17847.2      .1       0
 20307.1      .1       0
Bank Sta=4739.8,5399.6
XS Rating Curve= 0 ,0
Exp/Cntr=0.3,0.1

Type RM Length L Ch R = 1 ,370248  ,1734,1734,1734
BEGIN DESCRIPTION:
PEDERNALES RIVER 182.0
END DESCRIPTION:
XS GIS Cut Line= 4
      2819657.08     10073550.56      2821379.34     10056806.47
       2824536.4     10047024.31      2827859.34      10032523.6
#Sta/Elev= 30
-14395.4 1723.61  -12537 1647.41-10819.8 1619.95 -9645.2 1658.73   -7886 1644.57
 -6607.3 1591.81   -5679 1578.76 -4104.4 1531.11 -2994.8 1494.55   915.2 1485.95
  4751.6 1444.09  4972.1 1422.44  5245.4 1443.88  5314.7 1446.55  6975.1 1452.97
  9420.2  1501.8 11886.5 1507.25 14040.2 1521.28 15376.3 1540.61 17430.7 1588.01
 18338.7 1608.96 19601.5 1674.76 21467.7 1618.52 21884.7 1644.46 23177.4 1692.55
 23808.8  1679.8   25281 1756.44 26089.2 1716.18 26897.4 1712.29 27592.6 1756.49
#Mann= 11 ,-1 , 0
-14395.4      .1       0  -12537      .1       0   -5679      .1       0
 -4104.4      .1       0  4751.6     .07       0  5314.7      .1       0
 11886.5      .1       0 14040.2     .05       0 15376.3      .1       0
 17430.7      .1       0 21884.7      .1       0
Bank Sta=4751.6,5245.4
XS Rating Curve= 0 ,0
Exp/Cntr=0.3,0.1

Type RM Length L Ch R = 1 ,368514  ,2394,2394,2394
BEGIN DESCRIPTION:
PEDERNALES RIVER 183.0
END DESCRIPTION:
XS GIS Cut Line= 4
      2820931.04     10072473.22      2822942.77     10056915.43
      2826031.04     10049226.76      2828201.57     10034887.24
#Sta/Elev= 30
-12529.7  1681.3-11597.4 1645.64-11105.3 1649.98 -9434.7 1597.86 -8541.5  1602.2
 -7770.9 1594.53 -7289.1 1615.85 -2236.6 1510.15  -464.9 1494.94   414.6 1475.73
  1233.4 1450.74  1756.1 1468.51    4579  1445.4  4603.2 1443.31    4931 1422.96
 5288.87 1444.64  8558.1 1462.01 10761.8 1480.89 11183.8 1477.88 12773.7 1492.96
 14651.6    1527 15381.8 1535.79 15834.1 1541.22 17786.8  1580.4 18515.1 1598.68
 19474.7 1617.78 21408.6 1582.99 22681.4 1668.96 24085.9  1633.2 25946.2  1723.8
#Mann= 17 ,-1 , 0
-12529.7      .1       0-11597.4      .1       0 -8541.5      .1       0
 -2236.6     .05       0  -464.9     .05       0   414.6      .1       0
    4579     .07       0 5288.87      .1       0  8558.1      .1       0
 10761.8     .16       0 11183.8      .1       0 12773.7     .05       0
 14651.6      .1       0 15381.8     .05       0 15834.1      .1       0
 17786.8     .16       0 18515.1      .1       0
Bank Sta=4603.2,5288.87
XS Rating Curve= 0 ,0
Exp/Cntr=0.3,0.1

Type RM Length L Ch R = 1 ,366120  ,2358,2358,2358
BEGIN DESCRIPTION:
PEDERNALES RIVER 184.0
END DESCRIPTION:
XS GIS Cut Line= 4
      2822971.87     10071697.04      2825251.45     10058215.02
      2826478.24      10051013.8        2829052.     10035637.37
#Sta/Elev= 30
-10691.2 1715.32-10467.8 1706.61 -6186.4 1554.71 -5108.4 1552.65 -2029.5 1540.53
 -1002.8 1533.61   292.9 1512.45   988.6 1520.57  4058.8 1487.56  4667.4 1445.84
    4717 1442.44  5022.9 1414.83  5379.3 1443.56  6683.5 1448.32  7142.6 1429.47
  7817.3 1447.79  8058.1  1436.1  9449.1 1451.04 11250.2 1473.33 13399.5 1506.01
   15084 1510.24 16060.6 1523.25 17870.8 1554.82 19241.7 1563.61 19957.3 1575.54
 21301.2 1571.85   22674 1637.09 23569.5 1598.31 25157.9 1714.17 25877.5 1732.75
#Mann= 17 ,-1 , 0
-10691.2     .05       0-10467.8      .1       0 -5108.4     .05       0
 -2029.5      .1       0 -1002.8      .1       0   988.6      .1       0
  4667.4     .07       0  5379.3      .1       0  9449.1      .1       0
 11250.2      .1       0 13399.5     .05       0   15084      .1       0
 16060.6     .05       0 17870.8      .1       0 19241.7      .1       0
 19957.3      .1       0 21301.2      .1       0
Bank Sta=4717,5379.3
XS Rating Curve= 0 ,0
Exp/Cntr=0.3,0.1

Type RM Length L Ch R = 1 ,363762  ,1481,1481,1481
BEGIN DESCRIPTION:
PEDERNALES RIVER 185.0
END DESCRIPTION:
XS GIS Cut Line= 4
       2826509.8     10070763.35      2827973.74     10057434.22
      2827105.52     10052974.65      2829645.04      10035968.7
#Sta/Elev= 30
-11015.5 1659.43 -9229.9 1636.21   -8028  1586.9 -7591.6 1597.13 -5073.2 1543.45
 -3509.1  1517.2 -2823.2 1506.61   189.5 1494.01  4482.8 1435.99  4488.1 1435.24
  4962.8  1410.8    5257 1434.44  5572.9 1421.34  6847.3 1466.83  8767.3 1483.64
  9738.9 1488.86 10717.8    1503 11534.1 1491.89 12351.5 1488.47 13567.2 1495.96
 14538.4 1510.78 16235.3 1528.82 18637.5  1548.8 19172.2 1545.79 20587.7 1599.15
 21467.4 1578.67 22539.1 1660.31 22900.1 1668.01 23337.9 1715.16 24131.6 1704.24
#Mann= 16 ,-1 , 0
-11015.5      .1       0 -9229.9      .1       0 -5073.2      .1       0
 -3509.1     .05       0 -2823.2      .1       0  4482.8     .07       0
    5257      .1       0  8767.3      .1       0  9738.9      .1       0
 10717.8     .05       0 11534.1      .1       0 12351.5     .05       0
 13567.2     .05       0 14538.4     .05       0 16235.3      .1       0
 18637.5      .1       0
Bank Sta=4488.1,5257
XS Rating Curve= 0 ,0
Exp/Cntr=0.3,0.1

Type RM Length L Ch R = 1 ,362281  ,1580,1580,1580
BEGIN DESCRIPTION:
PEDERNALES RIVER 195.0
END DESCRIPTION:
XS GIS Cut Line= 4
       2828373.3     10069212.63      2829016.97     10056416.02
      2828368.38     10051742.08      2830128.02     10036408.63
#Sta/Elev= 30
  -10069 1646.51 -8273.5 1627.93 -7479.9 1600.03 -6481.6 1600.54 -5612.3  1563.6
   -3359 1509.26 -2899.3 1503.75    1531 1456.24  1684.7 1474.05  3789.4 1434.95
  4588.4 1432.78  4603.7 1430.14  4997.2 1409.61  5310.4 1430.77  6390.8 1457.48
    7822 1481.77    9323 1466.48 10050.3  1473.7 10742.2 1470.69 12094.1 1493.86
 13781.2 1503.67 15840.3 1514.41 16239.6 1518.96 17817.4  1539.1 18560.6 1544.74
 19138.4 1550.08 20027.8 1567.29 20515.6 1588.93 21712.6 1652.45 22896.6  1687.1
#Mann= 19 ,-1 , 0
  -10069      .1       0 -5612.3      .1       0   -3359      .1       0
 -2899.3      .1       0    1531      .1       0  4588.4     .07       0
  5310.4      .1       0  6390.8      .1       0    7822      .1       0
 10050.3      .1       0 12094.1     .05       0 13781.2     .05       0
 15840.3     .16       0 16239.6      .1       0 17817.4      .1       0
 18560.6     .16       0 19138.4      .1       0 20027.8     .16       0
 20515.6      .1       0
Bank Sta=4603.7,5310.4
XS Rating Curve= 0 ,0
Exp/Cntr=0.3,0.1

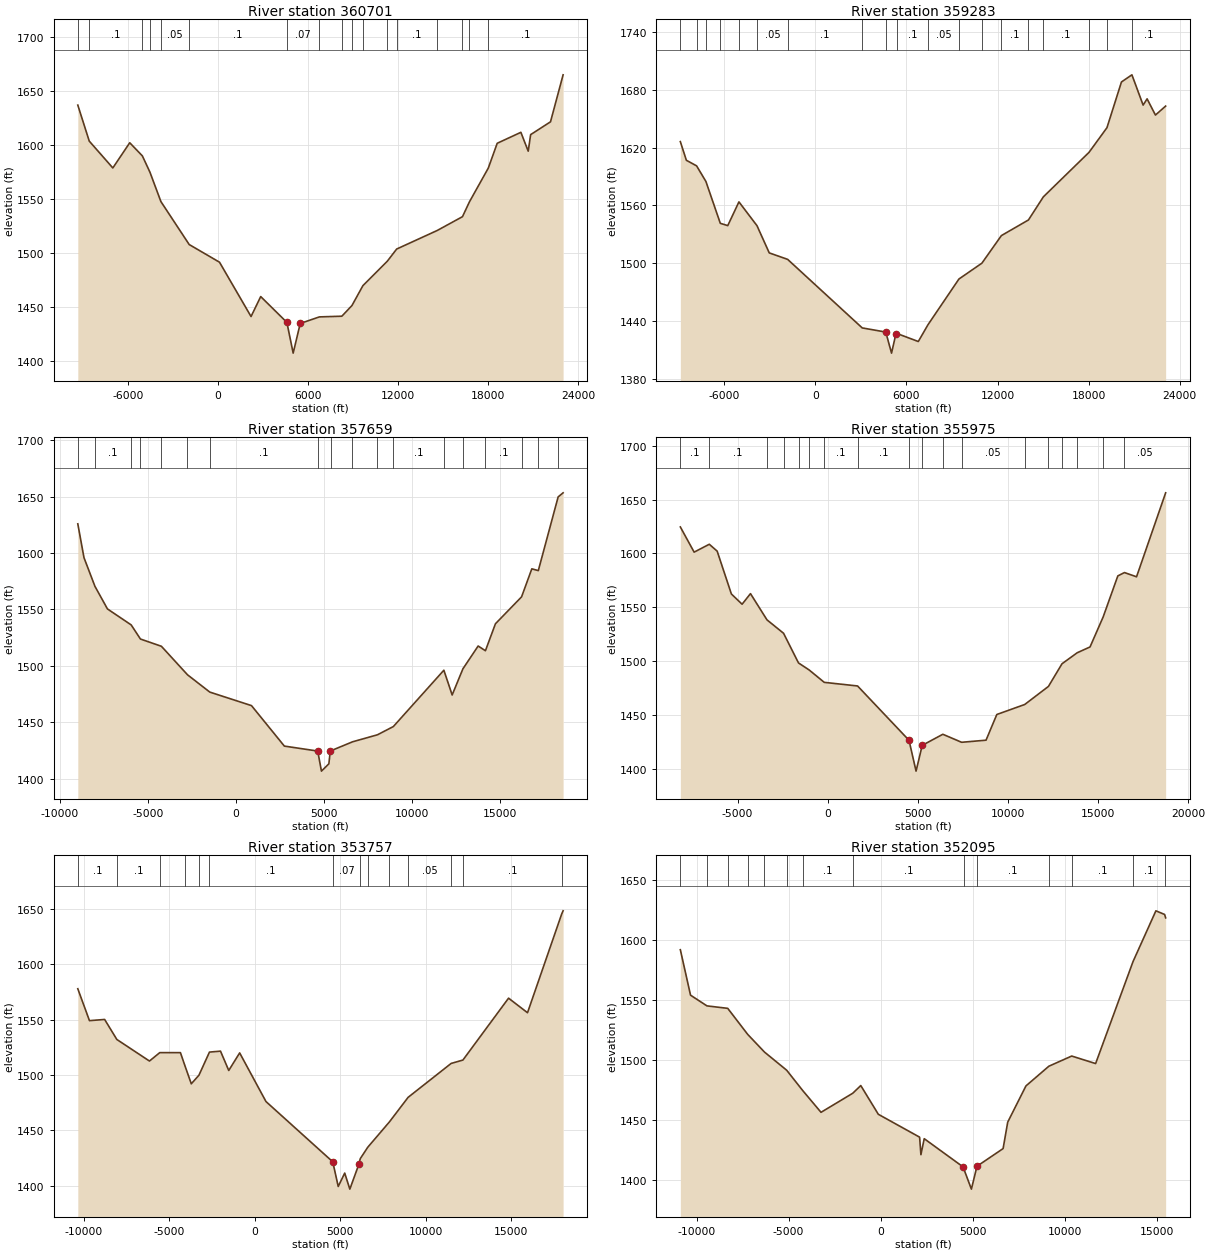
Type RM Length L Ch R = 1 ,360701  ,1418,1418,1418
BEGIN DESCRIPTION:
PEDERNALES RIVER 197.0
END DESCRIPTION:
XS GIS Cut Line= 3
      2829409.28     10068791.11        2830219.     10055725.28
      2830652.37     10036480.06
#Sta/Elev= 30
 -9325.6 1637.23 -8562.6 1603.84 -6991.6 1578.92 -5864.7  1602.3 -5023.5 1590.12
   -4520 1575.06   -3788 1547.73 -1902.7 1507.86     117 1491.47  2219.8 1441.05
  2863.8 1459.57  4607.1 1435.64  5026.9 1407.09  5497.3 1434.61  6775.7 1440.71
  8271.5 1441.34  8945.1 1451.28  9674.9 1469.72 11304.1 1492.44 11923.9 1503.67
 14626.6 1520.89   16310  1533.7 16771.4 1547.41   18031 1578.81 18623.9  1601.8
   20201 1611.98 20691.1 1594.48 20851.2 1609.83 22176.2 1621.73 23015.4 1665.33
#Mann= 17 ,-1 , 0
 -9325.6      .1       0 -8562.6      .1       0 -5023.5     .16       0
   -4520      .1       0   -3788     .05       0 -1902.7      .1       0
  4607.1     .07       0  6775.7      .1       0  8271.5     .16       0
  8945.1     .05       0  9674.9      .1       0 11304.1     .05       0
 11923.9      .1       0 14626.6      .1       0   16310      .1       0
 16771.4      .1       0   18031      .1       0
Bank Sta=4607.1,5497.3
XS Rating Curve= 0 ,0
Exp/Cntr=0.3,0.1

Type RM Length L Ch R = 1 ,359283  ,1624,1624,1624
BEGIN DESCRIPTION:
PEDERNALES RIVER 198.0
END DESCRIPTION:
XS GIS Cut Line= 2
      2830838.18     10068359.27      2832736.19     10036453.37
#Sta/Elev= 30
 -8888.9 1626.17 -8492.7 1606.82 -7818.9 1601.01 -7204.7 1584.79 -6256.3 1541.33
 -5765.8 1538.96 -5029.8  1563.6 -3840.1 1538.87   -3033 1510.62 -1823.5 1503.93
  3090.3 1432.74  4640.5 1428.43  5020.9 1406.56  5301.7 1426.05  5381.8 1426.91
  6784.3 1418.62  7413.7 1435.87    9458 1483.48 10972.5 1499.97 12254.3 1528.59
 14037.9 1544.83 15021.2 1568.85 18031.8 1615.12 19208.1 1640.62 20163.8 1688.12
 20852.4 1695.53 21590.4  1664.1 21852.3 1670.57 22401.9 1653.77 23073.4 1663.07
#Mann= 19 ,-1 , 0
 -8888.9      .1       0 -7818.9      .1       0 -7204.7     .16       0
 -6256.3      .1       0 -5029.8     .16       0 -3840.1     .05       0
 -1823.5      .1       0  3090.3      .1       0  4640.5     .07       0
  5381.8      .1       0  7413.7     .05       0    9458      .1       0
 10972.5     .05       0 12254.3      .1       0 14037.9     .16       0
 15021.2      .1       0 18031.8      .1       0 19208.1      .1       0
 20852.4      .1       0
Bank Sta=4640.5,5301.7
XS Rating Curve= 0 ,0
Exp/Cntr=0.3,0.1

Type RM Length L Ch R = 1 ,357659  ,1684,1684,1684
BEGIN DESCRIPTION:
PEDERNALES RIVER 202.0
END DESCRIPTION:
XS GIS Cut Line= 2
      2832084.25     10068686.92      2834362.54     10041213.02
#Sta/Elev= 30
 -8990.4 1625.99 -8638.9 1595.97 -8017.7 1570.58 -7306.1  1550.5 -5958.3 1536.33
 -5431.7 1523.79 -4241.3 1517.37 -2760.5  1492.1 -1491.7 1476.71   876.5 1464.72
  2742.9 1428.81  4639.4  1424.4  4849.9  1406.6  5271.6 1413.09  5351.8 1424.38
    5392  1424.7  6613.6 1432.59  8033.6 1438.85  8935.3 1446.15 11804.8 1496.13
 12275.5 1474.15 12886.6 1497.38 13752.2  1517.6 14165.9 1513.43 14733.9 1537.33
 16218.6 1561.22   16801 1586.08 17169.4  1584.5 18296.4 1649.89 18577.8 1653.51
#Mann= 18 ,-1 , 0
 -8990.4      .1       0 -8017.7      .1       0 -5958.3     .05       0
 -5431.7      .1       0 -4241.3     .05       0 -2760.5      .1       0
 -1491.7      .1       0  4639.4     .07       0    5392      .1       0
  6613.6      .1       0  8033.6     .05       0  8935.3      .1       0
 11804.8     .16       0 12886.6      .1       0 14165.9      .1       0
 16218.6      .1       0 17169.4      .1       0 18296.4      .1       0
Bank Sta=4639.4,5351.8
XS Rating Curve= 0 ,0
Exp/Cntr=0.3,0.1

Type RM Length L Ch R = 1 ,355975  ,2218,2218,2218
BEGIN DESCRIPTION:
PEDERNALES RIVER 204.0
END DESCRIPTION:
XS GIS Cut Line= 3
      2833517.66     10068394.58      2834704.87     10056693.43
      2835878.53     10041581.77
#Sta/Elev= 30
 -8174.4 1624.62 -7409.6  1601.2 -6568.4 1608.53 -6131.8 1602.12 -5343.6 1562.32
 -4749.8 1552.79 -4283.7 1562.63 -3368.7 1538.26 -2448.9 1525.78 -1620.6 1498.21
 -1028.8 1491.67  -192.2 1480.16  1655.7  1476.8  4509.3 1426.31  4900.2 1397.64
  5241.5  1421.6  6386.1  1431.9  7426.3 1424.45  8782.1  1426.4  9379.6 1450.29
 10927.8 1459.58 12244.4  1476.4 12996.2 1497.46   13838 1507.66 14550.2 1513.07
 15280.1 1541.05 16092.4 1579.12 16459.8 1582.22 17130.5 1578.29   18744 1656.34
#Mann= 18 ,-1 , 0
 -8174.4      .1       0 -6568.4      .1       0 -3368.7      .1       0
 -2448.9     .05       0 -1620.6      .1       0 -1028.8     .05       0
  -192.2      .1       0  1655.7      .1       0  4509.3     .07       0
  5241.5      .1       0  6386.1      .1       0  7426.3     .05       0
 10927.8     .05       0 12244.4      .1       0 12996.2     .05       0
   13838      .1       0 15280.1      .1       0 16459.8     .05       0
Bank Sta=4509.3,5241.5
XS Rating Curve= 0 ,0
Exp/Cntr=0.3,0.1

Type RM Length L Ch R = 1 ,353757  ,1662,1662,1662
BEGIN DESCRIPTION:
PEDERNALES RIVER 208.0
END DESCRIPTION:
XS GIS Cut Line= 3
      2835258.77     10069955.71      2836903.99     10056775.16
      2837032.78     10041650.74
#Sta/Elev= 30
-10353.8 1577.75 -9670.8 1548.96 -8783.3 1550.04 -8068.1 1531.98 -6159.5 1512.52
 -5556.4  1520.1   -4346 1520.09 -4065.6 1507.51 -3710.7 1491.98 -3261.2 1499.78
 -2646.7 1520.59 -2001.3 1521.46 -1517.2 1504.02  -878.9 1519.86   661.1 1475.97
  4570.5  1421.6  4890.5 1399.34  5270.5 1411.43  5570.3 1396.95  6095.6 1419.21
  6180.6 1424.44  6620.2 1434.75  7887.1  1457.6  8982.5 1479.78   11500 1510.36
 12189.5 1513.41 14860.9 1569.25 15970.9 1556.12 17973.2 1645.27   18054 1648.06
#Mann= 14 ,-1 , 0
-10353.8      .1       0 -8068.1      .1       0 -5556.4      .1       0
 -4065.6      .1       0 -3261.2      .1       0 -2646.7      .1       0
  4570.5     .07       0  6180.6     .16       0  6620.2      .1       0
  7887.1      .1       0  8982.5     .05       0   11500      .1       0
 12189.5      .1       0 17973.2     .05       0
Bank Sta=4570.5,6095.6
XS Rating Curve= 0 ,0
Exp/Cntr=0.3,0.1

Type RM Length L Ch R = 1 ,352095  ,1902,1902,1902
BEGIN DESCRIPTION:
PEDERNALES RIVER 210.0
END DESCRIPTION:
XS GIS Cut Line= 2
      2837787.14     10070096.44      2838987.24     10043764.67
#Sta/Elev= 30
-10881.4 1592.05-10328.1 1554.19 -9436.1 1545.25 -8307.3  1543.2 -7221.9 1521.48
   -6311 1506.76   -5106 1491.63 -4240.2 1474.79 -3240.8 1456.54 -1516.7 1472.44
 -1080.9 1478.85  -127.5  1454.9  2114.8 1435.84  2184.9 1421.23    2365 1434.57
  4487.2 1410.93  4537.3 1408.51  4927.4 1392.53    5228 1411.47    5238 1411.67
  6649.5 1426.32  6899.7 1448.35  7890.8 1478.56  9135.7 1494.97   10376 1503.45
 11674.7 1497.18 13707.2 1582.19 14948.1 1624.48 15422.7 1621.44 15477.7 1618.63
#Mann= 14 ,-1 , 0
-10881.4      .1       0 -9436.1      .1       0 -8307.3      .1       0
 -7221.9     .05       0   -6311      .1       0   -5106     .05       0
 -4240.2      .1       0 -1516.7      .1       0  4537.3     .07       0
    5238      .1       0  9135.7     .05       0   10376      .1       0
 13707.2      .1       0 15422.7     .16       0
Bank Sta=4487.2,5228
XS Rating Curve= 0 ,0
Exp/Cntr=0.3,0.1