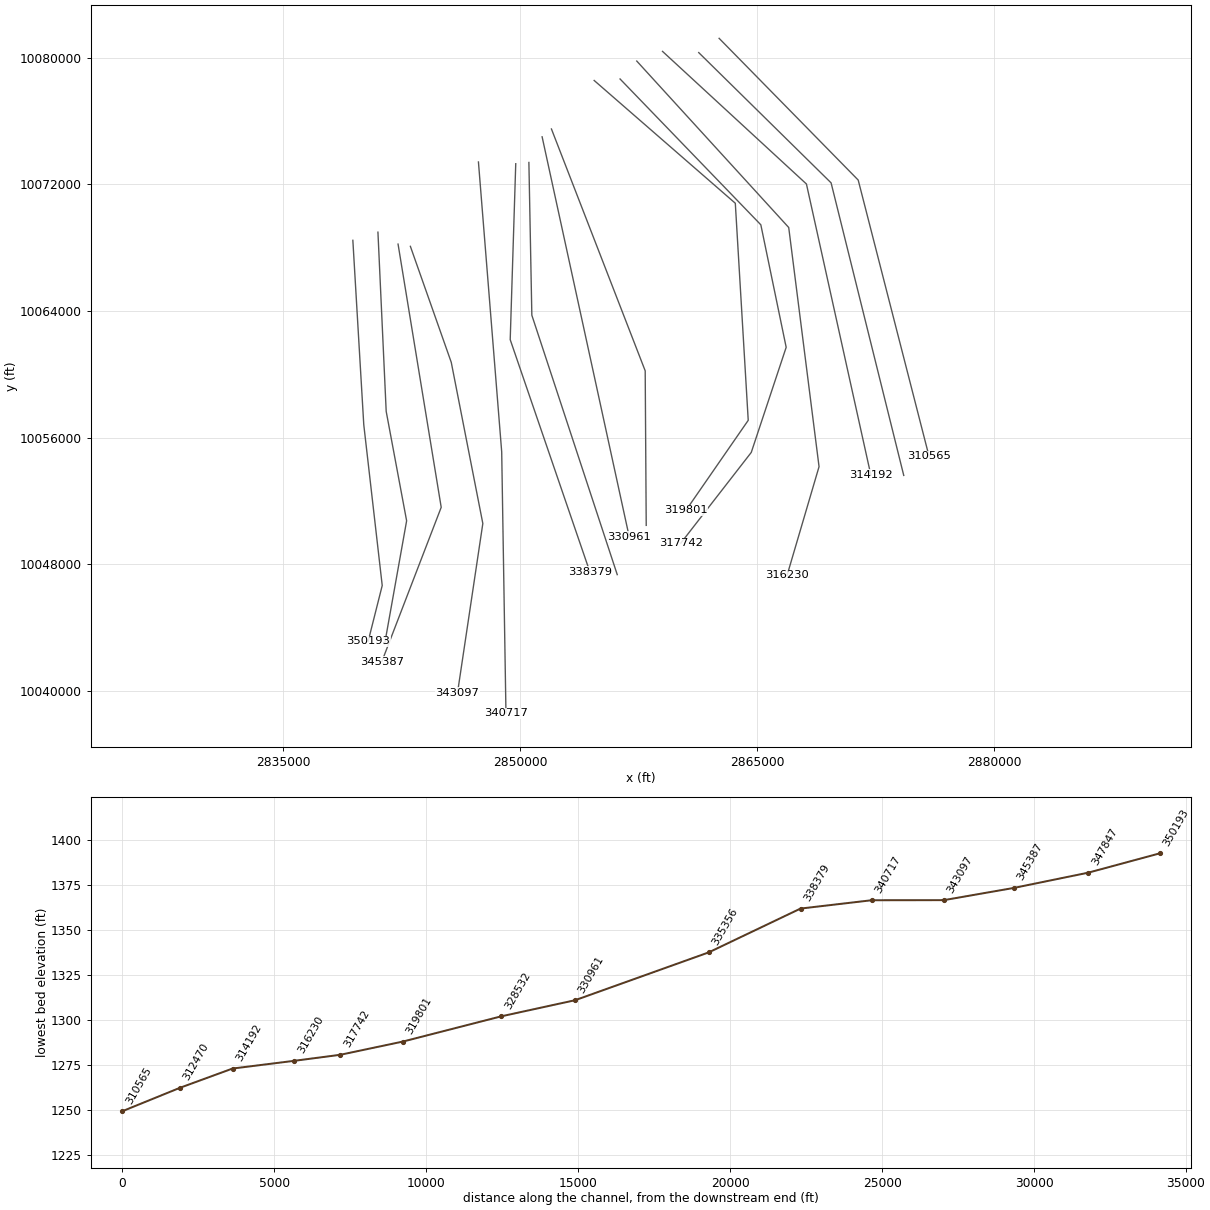
HEC-RAS study PEDERNALES RIVER.prj: PEDERNALES RIVER Base Level Engineering

--- PEDERNALES RIVER.g02 (geometry) --- (continued)

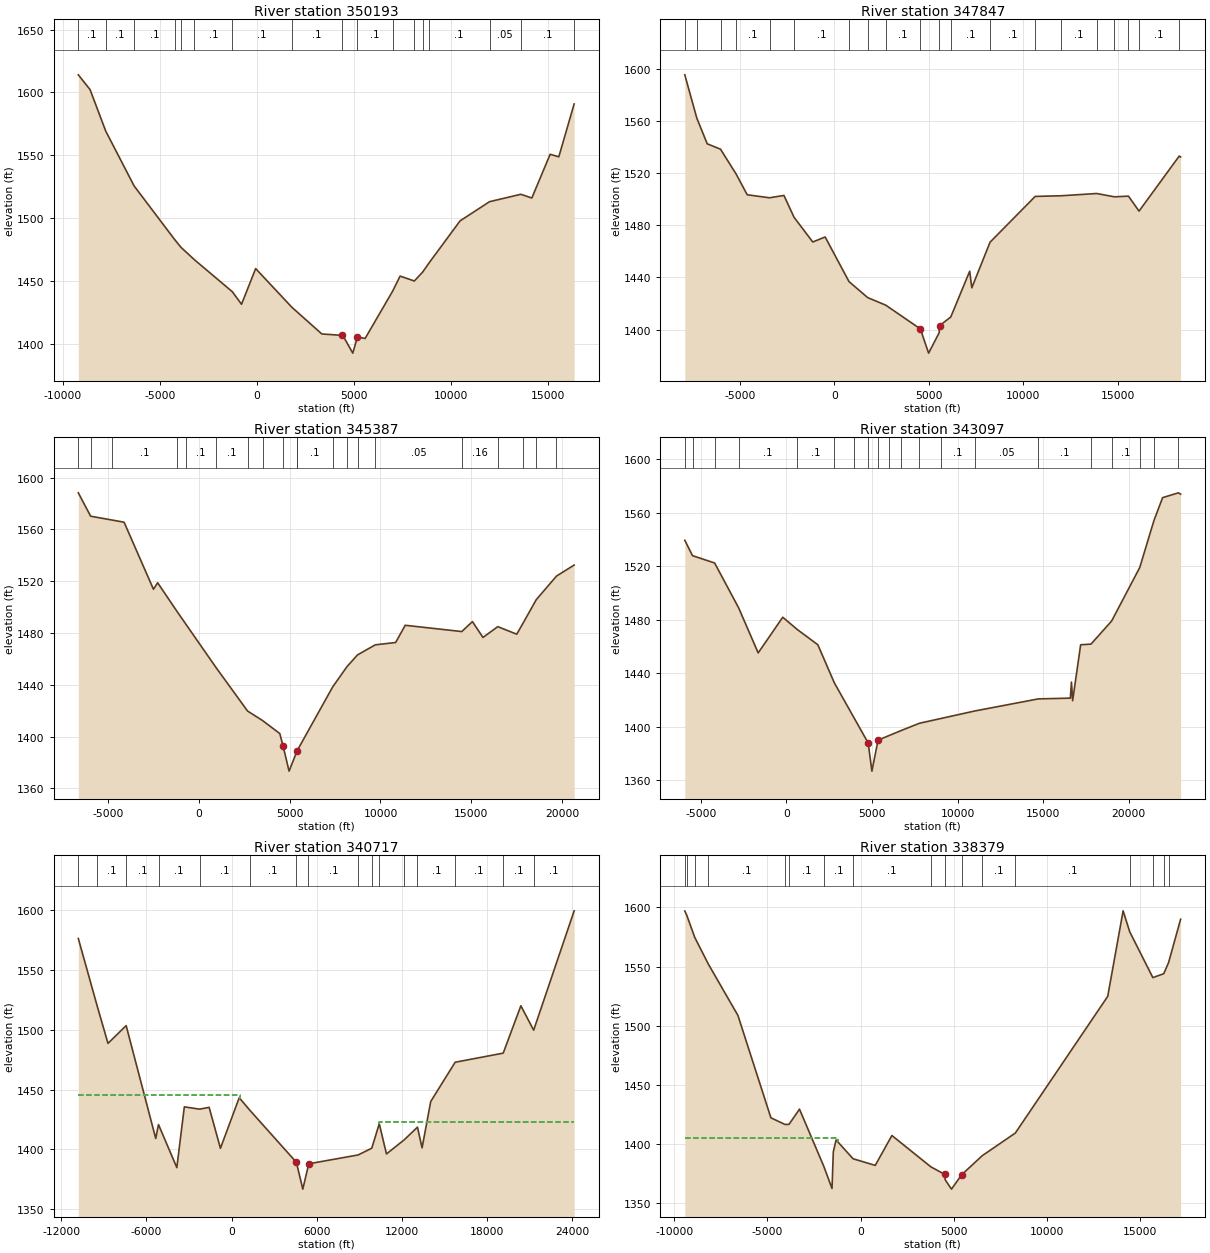
Type RM Length L Ch R = 1 ,350193  ,2346,2346,2346
BEGIN DESCRIPTION:
PEDERNALES RIVER 212.0
END DESCRIPTION:
XS GIS Cut Line= 4
      2839402.01     10068466.09      2840093.69     10056813.93
      2841262.29     10046652.52      2840370.16     10043121.44
#Sta/Elev= 30
 -9207.8 1613.97 -8604.4 1602.25 -7794.2 1569.15 -6335.1  1525.6 -4244.9 1482.93
 -3921.8 1476.77 -3229.7  1466.9 -1272.3 1441.39  -800.7 1431.44   -72.3 1459.82
    1793 1429.06    3337 1407.81  4377.6 1406.71  4397.7 1407.19    4931 1392.57
    5172 1405.51  5565.4 1404.22  6978.2  1441.7  7368.3 1453.85  8102.6 1449.96
  8533.5  1457.1  8854.2  1464.2 10457.4 1497.77 11975.6 1513.04 13590.1 1518.94
 14154.8 1515.96 15098.7 1550.76   15545 1548.75 16330.9 1590.63 16335.3  1590.8
#Mann= 17 ,-1 , 0
 -9207.8      .1       0 -7794.2      .1       0 -6335.1      .1       0
 -4244.9      .1       0 -3921.8     .05       0 -3229.7      .1       0
 -1272.3      .1       0    1793      .1       0  4377.6     .07       0
    5172      .1       0  6978.2     .16       0  8102.6      .1       0
  8533.5     .05       0  8854.2      .1       0 11975.6     .05       0
 13590.1      .1       0 16330.9      .1       0
Bank Sta=4397.7,5172
XS Rating Curve= 0 ,0
Exp/Cntr=0.3,0.1

Type RM Length L Ch R = 1 ,347847  ,2460,2460,2460
BEGIN DESCRIPTION:
PEDERNALES RIVER 214.0
END DESCRIPTION:
XS GIS Cut Line= 4
      2840990.82     10068980.41      2841513.52     10057656.23
      2842807.67     10050741.57      2841417.08     10042969.15
#Sta/Elev= 30
 -7927.4 1595.57 -7289.1 1562.28 -6739.5 1542.61 -6035.3 1538.47 -5208.9 1519.41
 -4619.5 1503.47 -3437.9 1501.16 -2675.1 1502.96 -2141.6 1486.23 -1147.7 1467.21
    -492 1471.06   772.3  1436.8  1761.9 1424.52  2716.7 1418.72    4553 1400.47
  4988.9 1381.88  5547.8 1397.52  5568.2 1402.93  6163.9 1409.65  7165.4 1444.77
  7277.4 1432.05  8244.7 1467.07   10636 1502.21 11987.7 1502.69 13890.2 1504.44
 14835.4 1501.89 15575.8 1502.42 16136.8 1490.92 18265.9 1533.21 18339.4 1532.48
#Mann= 20 ,-1 , 0
 -7927.4      .1       0 -7289.1      .1       0 -6035.3     .05       0
 -5208.9      .1       0 -3437.9     .05       0 -2141.6      .1       0
   772.3      .1       0  1761.9      .1       0  2716.7      .1       0
    4553     .07       0  5547.8      .1       0  6163.9      .1       0
  8244.7      .1       0   10636     .05       0 11987.7      .1       0
 13890.2     .05       0 14835.4      .1       0 15575.8     .05       0
 16136.8      .1       0 18265.9     .05       0
Bank Sta=4553,5568.2
XS Rating Curve= 0 ,0
Exp/Cntr=0.3,0.1

Type RM Length L Ch R = 1 ,345387  ,2290,2290,2290
BEGIN DESCRIPTION:
PEDERNALES RIVER 218.0
END DESCRIPTION:
XS GIS Cut Line= 3
      2842265.04     10068225.88      2844997.45     10051593.26
      2841237.13     10041844.08
#Sta/Elev= 30
 -6639.7 1588.19   -5961 1570.15   -4809 1567.25 -4119.7 1565.52 -2502.8 1513.77
 -2272.2 1518.78 -1187.7  1496.3  -700.5 1486.48   935.8 1453.49  2679.9 1419.77
  3509.2  1412.4  4454.3 1402.38    4638 1392.68  4965.7 1373.38  5410.4 1389.14
  7369.4 1438.42  8161.2 1454.14  8735.8 1463.08  9713.1 1470.86   10835 1472.66
 11361.5 1485.96 14475.9 1481.11 15063.7 1488.78 15644.8 1476.57 16459.3  1484.9
 17502.9 1479.07 17854.4 1487.66 18577.3  1505.7 19691.9 1523.92 20665.1 1532.46
#Mann= 20 ,-1 , 0
 -6639.7      .1       0   -5961     .05       0   -4809      .1       0
 -1187.7      .1       0  -700.5      .1       0   935.8      .1       0
  2679.9     .05       0  3509.2      .1       0    4638     .07       0
  5410.4     .05       0  5410.4      .1       0  7369.4      .1       0
  8161.2      .1       0  8735.8     .05       0  9713.1     .05       0
 14475.9     .16       0 16459.3     .05       0 17854.4      .1       0
 18577.3      .1       0 19691.9     .05       0
Bank Sta=4638,5410.4
XS Rating Curve= 0 ,0
Exp/Cntr=0.3,0.1

Type RM Length L Ch R = 1 ,343097  ,2380,2380,2380
BEGIN DESCRIPTION:
PEDERNALES RIVER 221.0
END DESCRIPTION:
XS GIS Cut Line= 4
      2843044.93     10068084.66      2845634.17     10060754.77
      2847633.18      10050570.2      2846027.55     10039857.12
#Sta/Elev= 30
 -5941.9 1539.43 -5491.4 1527.92 -4197.6 1522.42 -2792.9 1488.81   -1652 1455.12
  -215.5 1481.81   637.7 1472.61  1834.9 1461.23  2800.2 1432.72  3920.6 1407.24
  4778.1 1387.74    4996 1366.64  5356.3 1389.86  6017.4 1393.36  6710.3 1397.03
  7771.8 1402.46  9032.4 1406.04 11008.8 1411.65 14723.5  1420.7 16597.5 1421.27
 16661.5 1433.29 16730.7 1419.34 17199.4 1461.21   17805 1461.72 19010.6    1479
 20652.2 1518.98   21486 1554.29 21990.9 1571.33 22912.5 1574.94 23043.5 1573.94
#Mann= 20 ,-1 , 0
 -5941.9      .1       0 -5491.4      .1       0 -4197.6     .05       0
 -2792.9      .1       0   637.7      .1       0  2800.2      .1       0
  3920.6      .1       0  4778.1     .07       0  5356.3      .1       0
  6017.4      .1       0  6710.3      .1       0  7771.8      .1       0
  9032.4      .1       0 11008.8     .05       0 14723.5      .1       0
   17805      .1       0 19010.6      .1       0 20652.2      .1       0
   21486     .16       0 22912.5     .16       0
Bank Sta=4778.1,5356.3
XS Rating Curve= 0 ,0
Exp/Cntr=0.3,0.1

Type RM Length L Ch R = 1 ,340717  ,2338,2338,2338
BEGIN DESCRIPTION:
PEDERNALES RIVER 225.0
END DESCRIPTION:
XS GIS Cut Line= 3
      2847355.22     10073415.11      2848828.15     10055098.89
       2849098.7     10038573.25
#Sta/Elev= 30
-10784.6 1576.44 -9464.6 1520.25 -8696.5 1488.64 -7418.4 1503.51 -5335.7 1409.02
 -5141.1 1420.65 -3850.9 1384.61 -3322.7 1435.49 -2250.8 1433.56 -1576.7 1435.07
    -781 1400.77   542.2 1443.15  1292.6  1432.6  4566.2 1389.04  5017.4 1366.58
  5412.7 1386.56    5439  1387.8  8914.1 1395.21  9872.7 1400.88 10399.9 1421.35
 10906.3 1396.04   12160 1407.93 13088.8 1418.47 13412.7 1401.15 14023.2 1439.99
 15742.1 1472.85 19124.8 1480.47 20367.6 1520.13 21268.2 1499.71 24118.6 1599.65
#Mann= 16 ,-1 , 0
-10784.6      .1       0 -9464.6      .1       0 -7418.4      .1       0
 -5141.1      .1       0 -2250.8      .1       0  1292.6      .1       0
  4566.2     .07       0  5412.7      .1       0  8914.1     .05       0
  9872.7     .16       0 10399.9      .1       0   12160      .1       0
 13088.8      .1       0 15742.1      .1       0 19124.8      .1       0
 21268.2      .1       0
#XS Ineff= 2 , 0
          590.91 1445.4310409.09         1422.59
Permanent Ineff=
       F       F
Bank Sta=4566.2,5439
XS Rating Curve= 0 ,0
Exp/Cntr=0.3,0.1

Type RM Length L Ch R = 1 ,338379  ,3023,3023,3023
BEGIN DESCRIPTION:
PEDERNALES RIVER 234.0
END DESCRIPTION:
XS GIS Cut Line= 3
      2849717.75     10073304.95       2849366.9     10062189.14
      2854406.54     10047528.08
#Sta/Elev= 30
 -9440.3 1596.96 -9329.7 1593.21 -8905.5 1574.67 -8173.3 1552.06 -6587.7 1508.75
 -4816.8 1422.24 -4064.2 1416.63 -3844.8 1416.69 -3281.5 1429.52 -1979.5 1381.35
 -1535.1 1362.51 -1465.1 1393.54   -1315  1403.5  -405.4 1387.64     786 1382.02
    1681 1407.26  3780.5  1380.7  4520.7 1374.43  4541.8 1369.86    4880 1361.96
  5430.1 1374.15  6527.7 1390.17  8308.6 1409.35 13269.4 1524.84 14097.1 1597.13
 14450.1 1579.45 15692.9 1540.71 16277.9 1543.98 16534.3 1553.28 17184.1 1590.02
#Mann= 17 ,-1 , 0
 -9440.3      .1       0 -9329.7     .16       0 -8905.5      .1       0
 -8173.3      .1       0 -4064.2     .05       0 -3844.8      .1       0
 -1979.5      .1       0  -405.4      .1       0  3780.5     .16       0
  4541.8     .07       0  5430.1     .16       0  6527.7      .1       0
  8308.6      .1       0 14450.1      .1       0 15692.9     .16       0
 16277.9     .05       0 16534.3      .1       0
#XS Ineff= 2 , 0
        -1238.64 1405.38
Permanent Ineff=
       F       F
Bank Sta=4520.7,5430.1
XS Rating Curve= 0 ,0
Exp/Cntr=0.3,0.1

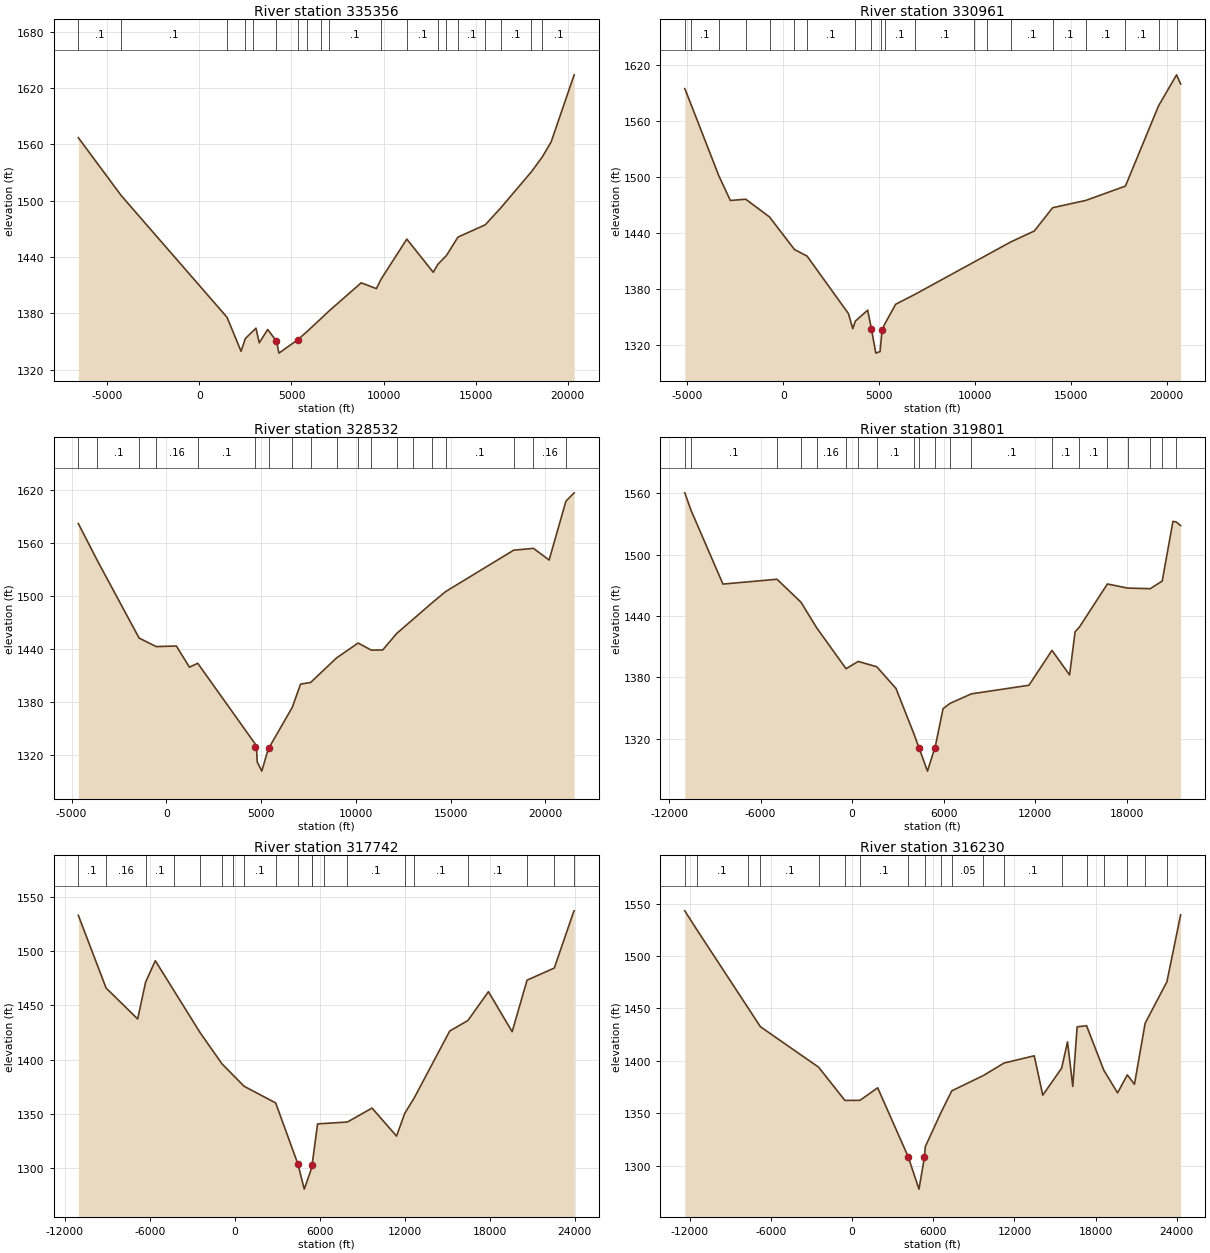
Type RM Length L Ch R = 1 ,335356  ,4395,4395,4395
BEGIN DESCRIPTION:
PEDERNALES RIVER 236.0
END DESCRIPTION:
XS GIS Cut Line= 3
      2850550.14     10073384.54      2850737.05     10063733.67
      2856145.26      10047340.3
#Sta/Elev= 30
 -6568.9 1567.18 -4242.1 1505.52  1505.1 1375.76  2263.6 1339.65  2499.4 1353.22
  2901.2 1360.89  3073.7 1364.19  3252.2 1348.63  3710.5  1362.8  4160.3 1351.12
  4186.8 1350.87  4318.8 1337.63  5335.2 1351.76  5851.8 1360.72  6598.2 1374.33
  7034.5 1382.41  8785.8 1412.53  9611.4 1406.36  9864.8 1416.41   11263 1459.11
 12697.7 1423.75 12950.4 1432.36 13408.2 1441.44 14037.7 1461.25 15523.5 1474.38
 16366.9 1492.49   18027 1530.86   18625 1546.93 19095.2 1562.58 20346.2 1634.14
#Mann= 19 ,-1 , 0
 -6568.9      .1       0 -4242.1      .1       0  1505.1      .1       0
  2499.4     .16       0  2901.2      .1       0  4160.3     .07       0
  5335.2      .1       0  5851.8      .1       0  6598.2     .16       0
  7034.5      .1       0  9864.8      .1       0   11263      .1       0
 12950.4      .1       0 13408.2     .05       0 14037.7      .1       0
 15523.5      .1       0 16366.9      .1       0   18027     .16       0
   18625      .1       0
Bank Sta=4186.8,5335.2
XS Rating Curve= 0 ,0
Exp/Cntr=0.3,0.1

Type RM Length L Ch R = 1 ,330961  ,2429,2429,2429
BEGIN DESCRIPTION:
PEDERNALES RIVER 245.0
END DESCRIPTION:
XS GIS Cut Line= 2
      2851387.65     10075004.99       2856903.7     10049735.63
#Sta/Elev= 30
 -5133.1 1594.45 -4820.9  1578.3 -3361.4 1501.28 -2756.7 1474.66 -1955.5 1476.02
  -714.5 1457.01   585.9 1422.19  1245.8 1415.06  3404.6 1353.42  3629.8 1337.33
  3762.2 1345.37  4407.6 1357.18  4598.6 1337.31  4833.3 1311.11  5052.5 1312.79
  5124.1 1328.69  5161.5 1336.24  5286.1 1341.86  5866.2 1363.44  6865.2 1373.99
  9956.4 1408.72 10644.1 1416.45 11879.8 1430.33 13097.6 1441.95 14056.8 1466.93
 15780.7 1474.69 17851.6 1490.07 19579.6 1576.03 20519.9 1609.28 20731.3 1599.49
#Mann= 20 ,-1 , 0
 -5133.1     .16       0 -4820.9      .1       0 -3361.4     .05       0
 -1955.5      .1       0  -714.5      .1       0   585.9      .1       0
  1245.8      .1       0  3762.2      .1       0  4598.6     .07       0
  5124.1      .1       0  5286.1      .1       0  6865.2      .1       0
  9956.4      .1       0 10644.1      .1       0 11879.8      .1       0
 14056.8      .1       0 15780.7      .1       0 17851.6      .1       0
 19579.6     .16       0 20519.9     .16       0
Bank Sta=4598.6,5161.5
XS Rating Curve= 0 ,0
Exp/Cntr=0.3,0.1

Type RM Length L Ch R = 1 ,328532  ,3234,3234,3234
BEGIN DESCRIPTION:
PEDERNALES RIVER 246.0
END DESCRIPTION:
XS GIS Cut Line= 3
      2851978.42     10075500.48       2857915.6     10060218.48
      2857980.31      10050453.1
#Sta/Elev= 30
 -4639.8 1582.08 -3631.6    1540 -1431.8 1452.57  -531.1 1442.98   533.1 1443.61
    1224 1419.65  1658.9 1424.14  4690.2 1332.96    4707 1329.68  4766.8  1326.5
  4797.5 1312.59  5038.7 1302.17  5400.8 1328.75  5419.7 1328.54  6649.5 1374.32
  7085.2 1400.56  7616.8 1402.42  8984.5 1430.16 10122.1 1446.97 10819.3 1438.96
   11420 1439.16 12164.2 1457.93 13012.9 1473.67 14026.5 1492.47 14735.1 1505.09
 18329.9 1551.96 19374.2 1554.04 20199.9 1540.81 21086.6 1607.43 21520.6  1616.8
#Mann= 19 ,-1 , 0
 -4639.8      .1       0 -3631.6      .1       0 -1431.8     .16       0
  -531.1     .16       0  1658.9      .1       0  4690.2     .07       0
  5419.7     .16       0  6649.5      .1       0  7616.8      .1       0
  8984.5     .16       0 10122.1      .1       0 10819.3     .16       0
 12164.2      .1       0 13012.9     .05       0 14026.5      .1       0
 14735.1      .1       0 18329.9     .16       0 19374.2     .16       0
 21086.6     .16       0
Bank Sta=4707,5400.8
XS Rating Curve= 0 ,0
Exp/Cntr=0.3,0.1

Type RM Length L Ch R = 1 ,319801  ,2059,2059,2059
BEGIN DESCRIPTION:
PEDERNALES RIVER 254.0
END DESCRIPTION:
XS GIS Cut Line= 4
       2854683.8     10078565.79      2863621.89     10070807.71
      2864440.18     10057090.95      2860494.53     10051400.15
#Sta/Elev= 30
-10970.2 1560.56-10562.2 1543.46 -8470.4 1471.26   -4927 1475.98 -3354.2 1453.52
 -2336.4 1428.71  -399.6 1388.43   396.7 1395.52  1612.5 1390.35  2872.8 1369.11
  4028.2 1325.42 4386.36 1310.89  4936.2 1288.18    5424 1311.15    5429 1310.76
  5958.2 1349.26  6407.3 1354.42  7812.6 1363.79 11588.2 1372.23 13099.7 1406.37
   14253 1382.31 14613.6 1424.53 14896.9 1429.18 16731.6 1471.35   18052 1467.34
 19538.5 1466.74 20324.6 1474.22 21029.1 1532.61 21226.4 1532.13 21531.2 1528.55
#Mann= 20 ,-1 , 0
-10970.2      .1       0-10562.2      .1       0   -4927      .1       0
 -3354.2      .1       0 -2336.4     .16       0  -399.6     .16       0
   396.7      .1       0  1612.5      .1       0  4028.2      .1       0
 4386.36     .07       0    5429     .05       0  6407.3      .1       0
  7812.6      .1       0 13099.7      .1       0 14896.9      .1       0
 16731.6      .1       0   18052      .1       0 19538.5     .16       0
 20324.6      .1       0 21226.4      .1       0
Bank Sta=4386.36,5424
XS Rating Curve= 0 ,0
Exp/Cntr=0.3,0.1

Type RM Length L Ch R = 1 ,317742  ,1512,1512,1512
BEGIN DESCRIPTION:
PEDERNALES RIVER 257.0
END DESCRIPTION:
XS GIS Cut Line= 5
      2856323.79     10078660.44      2865238.41     10069445.89
      2866843.28     10061704.72      2864632.48     10055062.83
      2860170.79       10049331.
#Sta/Elev= 30
-11037.9 1532.98 -9078.1 1466.01 -6850.3 1437.54   -6292 1471.38 -5605.5 1491.19
 -4301.4 1463.87 -2446.5    1425  -901.8 1396.25  -129.7 1386.02   657.3 1375.59
  2888.6 1360.22 4454.55 1304.07  4908.1 1280.84  5439.2 1300.68    5455 1302.72
  5846.1  1340.9  6312.1 1341.29  7953.6 1342.65  9688.9 1355.48 11418.4 1329.67
 11995.8  1350.6 12664.4 1364.79 15170.9 1426.42 16452.3 1436.11 17903.3 1462.66
 19577.2 1425.79 20629.6 1473.28 22551.1 1484.43 23921.1 1536.45 23952.7 1537.12
#Mann= 20 ,-1 , 0
-11037.9      .1       0 -9078.1     .16       0   -6292      .1       0
 -4301.4      .1       0 -2446.5      .1       0  -901.8     .16       0
  -129.7      .1       0   657.3      .1       0  2888.6     .16       0
 4454.55     .07       0  5439.2      .1       0  5439.2      .1       0
  6312.1     .16       0  7953.6      .1       0 11995.8     .05       0
 12664.4      .1       0 16452.3      .1       0 20629.6      .1       0
 22551.1     .05       0 23921.1     .16       0
Bank Sta=4454.55,5455
XS Rating Curve= 0 ,0
Exp/Cntr=0.3,0.1

Type RM Length L Ch R = 1 ,316230  ,2038,2038,2038
BEGIN DESCRIPTION:
PEDERNALES RIVER 256.0
END DESCRIPTION:
XS GIS Cut Line= 4
      2857381.58     10079792.27      2867004.41     10069275.54
      2868924.93     10054161.53      2866899.15     10047292.72
#Sta/Elev= 30
-12369.8 1543.12-11477.1 1525.11   -7732 1451.27 -6781.7 1432.53 -2478.5  1393.9
  -532.8 1362.15   578.4 1362.26  1888.5 1374.21 4136.36 1308.57    4941  1277.5
  5344.4 1308.03  5404.9 1317.93    6563 1350.46  7362.8 1371.28  9704.7 1385.95
 11230.6 1397.85   13462 1404.75 14091.8 1367.17 15487.1 1392.93 15921.4 1418.09
 16311.3 1375.52 16631.2 1432.39 17329.4 1433.46 18598.6 1391.14 19620.5 1369.38
 20341.9 1386.55 20869.7  1377.6 21658.1 1435.79 23268.5 1475.42 24281.9 1539.31
#Mann= 19 ,-1 , 0
-12369.8      .1       0-11477.1      .1       0   -7732      .1       0
 -6781.7      .1       0 -2478.5      .1       0  -532.8      .1       0
   578.4      .1       0 4136.36     .07       0  5404.9      .1       0
    6563      .1       0  7362.8     .05       0  9704.7      .1       0
 11230.6      .1       0 15487.1      .1       0 17329.4     .16       0
 18598.6      .1       0 20341.9      .1       0 21658.1      .1       0
 23268.5      .1       0
Bank Sta=4136.36,5344.4
XS Rating Curve= 0 ,0
Exp/Cntr=0.3,0.1

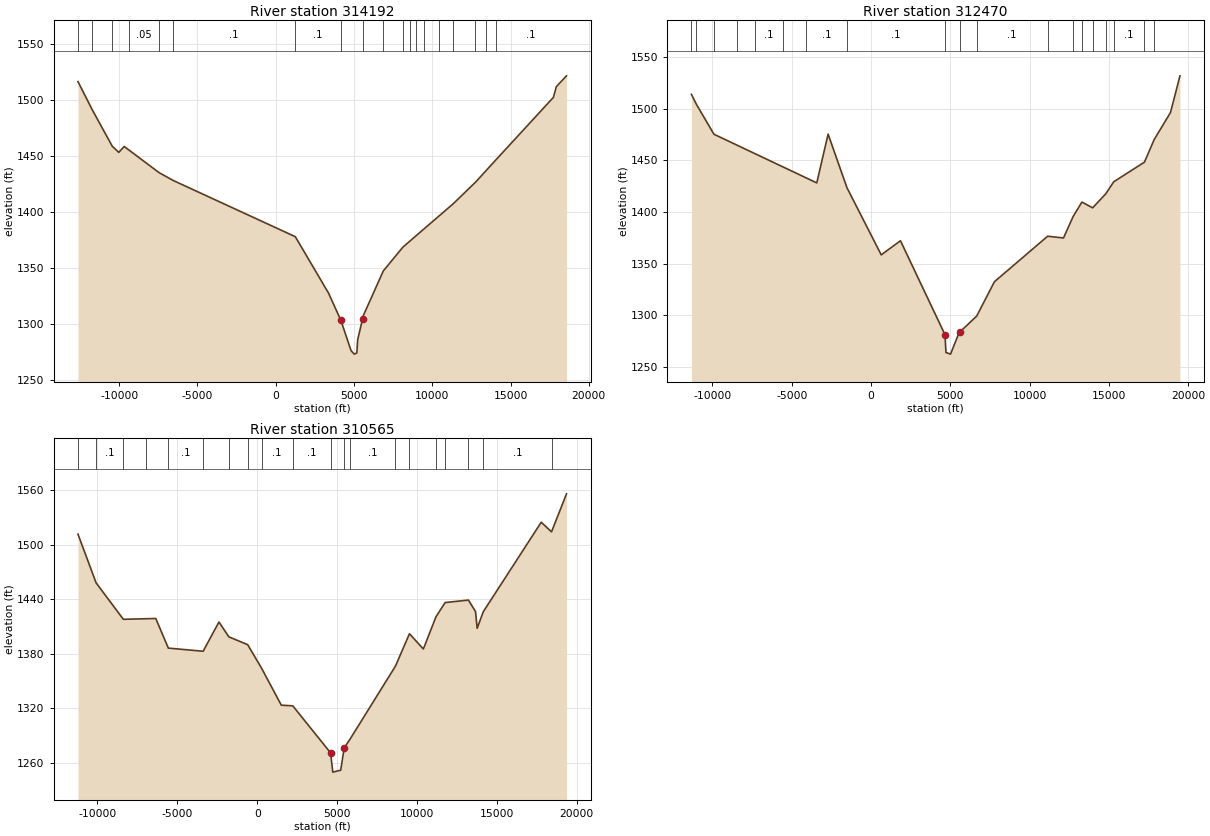
Type RM Length L Ch R = 1 ,314192  ,1722,1722,1722
BEGIN DESCRIPTION:
PEDERNALES RIVER 260.0
END DESCRIPTION:
XS GIS Cut Line= 3
      2859013.12     10080403.31      2868125.91     10072024.59
      2872204.26     10053637.41
#Sta/Elev= 30
-12636.5 1516.48-11747.7 1491.95-10448.2 1458.82-10028.6 1453.28 -9681.5 1458.55
 -9369.8 1455.28   -7463 1435.27 -6559.5 1428.24  1249.9 1378.01  3377.3 1327.54
  4164.2 1303.25  4810.1 1276.35  5018.5 1273.19  5179.2 1274.22  5233.9 1286.03
  5548.3 1304.75  5553.4 1306.31  6873.7 1347.48  8126.9 1368.75  8578.4 1374.19
  8971.1 1378.92  9476.8 1385.01   10399 1396.11 11335.1 1407.38 12761.6 1426.67
   13426 1436.82 14057.6 1446.47 17738.7 1502.39 17928.4 1511.99 18576.8 1521.61
#Mann= 19 ,-1 , 0
-12636.5      .1       0-11747.7      .1       0-10448.2      .1       0
 -9369.8     .05       0   -7463      .1       0 -6559.5      .1       0
  1249.9      .1       0  4164.2     .07       0  5553.4      .1       0
  6873.7     .05       0  8126.9     .05       0  8578.4     .16       0
  8971.1      .1       0  9476.8     .05       0   10399     .05       0
 11335.1      .1       0 12761.6      .1       0   13426     .16       0
 14057.6      .1       0
Bank Sta=4164.2,5548.3
XS Rating Curve= 0 ,0
Exp/Cntr=0.3,0.1

Type RM Length L Ch R = 1 ,312470  ,1905,1905,1905
BEGIN DESCRIPTION:
PEDERNALES RIVER 262.0
END DESCRIPTION:
XS GIS Cut Line= 3
      2861305.79     10080327.06      2869687.59     10072095.73
      2874288.34     10053609.37
#Sta/Elev= 30
-11319.5 1513.82-11000.9  1504.1 -9899.1 1475.24 -8447.7  1464.7 -7279.5 1456.22
 -5566.2 1443.78   -4067  1432.9 -3416.5 1428.18 -2702.3 1475.36 -1512.2 1423.49
   646.7 1358.57    1859 1372.23  4665.7  1281.4  4727.5 1264.13  5015.8 1262.56
  5582.3  1284.4  5587.5 1283.75    6666 1299.38  7782.3 1332.57 11136.5  1376.6
 12136.8 1374.91 12750.3 1395.86 13297.3 1409.61   13974 1404.08 14803.3 1417.67
 15304.3 1429.27 17239.1 1448.23 17855.3 1470.14   18880 1496.18 19478.5 1531.74
#Mann= 19 ,-1 , 0
-11319.5     .16       0-11000.9      .1       0 -9899.1      .1       0
 -8447.7     .05       0 -7279.5      .1       0 -5566.2      .1       0
   -4067      .1       0 -1512.2      .1       0  4665.7     .07       0
  5582.3      .1       0    6666      .1       0 11136.5      .1       0
 12750.3      .1       0 13297.3     .16       0   13974      .1       0
 14803.3     .16       0 15304.3      .1       0 17239.1      .1       0
 17855.3      .1       0
Bank Sta=4665.7,5587.5
XS Rating Curve= 0 ,0
Exp/Cntr=0.3,0.1

Type RM Length L Ch R = 1 ,310565  ,2231,2231,2231
BEGIN DESCRIPTION:
PEDERNALES RIVER 264.0
END DESCRIPTION:
XS GIS Cut Line= 3
      2862596.85     10081228.29      2871404.24     10072272.92
      2875887.93      10054827.8
#Sta/Elev= 30
-11216.9 1511.48-10082.1 1457.87   -8377 1417.74 -6975.9 1418.35 -6347.4 1418.62
 -5561.3 1386.04 -3384.4 1382.56 -2394.6 1414.76 -1774.9 1398.42  -597.2 1389.84
     273 1363.92  1508.1 1323.19  2223.8 1322.51  4592.3 1270.71  4729.2 1249.51
  5225.1 1251.63  5442.6 1276.13  5817.3 1286.02  8648.9 1366.13  9528.5 1401.84
 10397.9 1385.05 11188.6 1420.59 11758.8 1436.16 13217.5 1438.91 13660.6 1426.33
 13763.9 1407.88 14153.8 1426.25 17773.1 1524.58 18417.8 1514.02 19355.8 1555.86
#Mann= 20 ,-1 , 0
-11216.9      .1       0-10082.1      .1       0   -8377      .1       0
 -6975.9     .16       0 -5561.3      .1       0 -3384.4     .16       0
 -1774.9      .1       0  -597.2     .16       0     273      .1       0
  2223.8      .1       0  4592.3     .07       0  5442.6      .1       0
  5817.3      .1       0  8648.9      .1       0  9528.5      .1       0
 11188.6     .16       0 11758.8      .1       0 13217.5      .1       0
 14153.8      .1       0 18417.8      .1       0
Bank Sta=4592.3,5442.6
XS Rating Curve= 0 ,0
Exp/Cntr=0.3,0.1