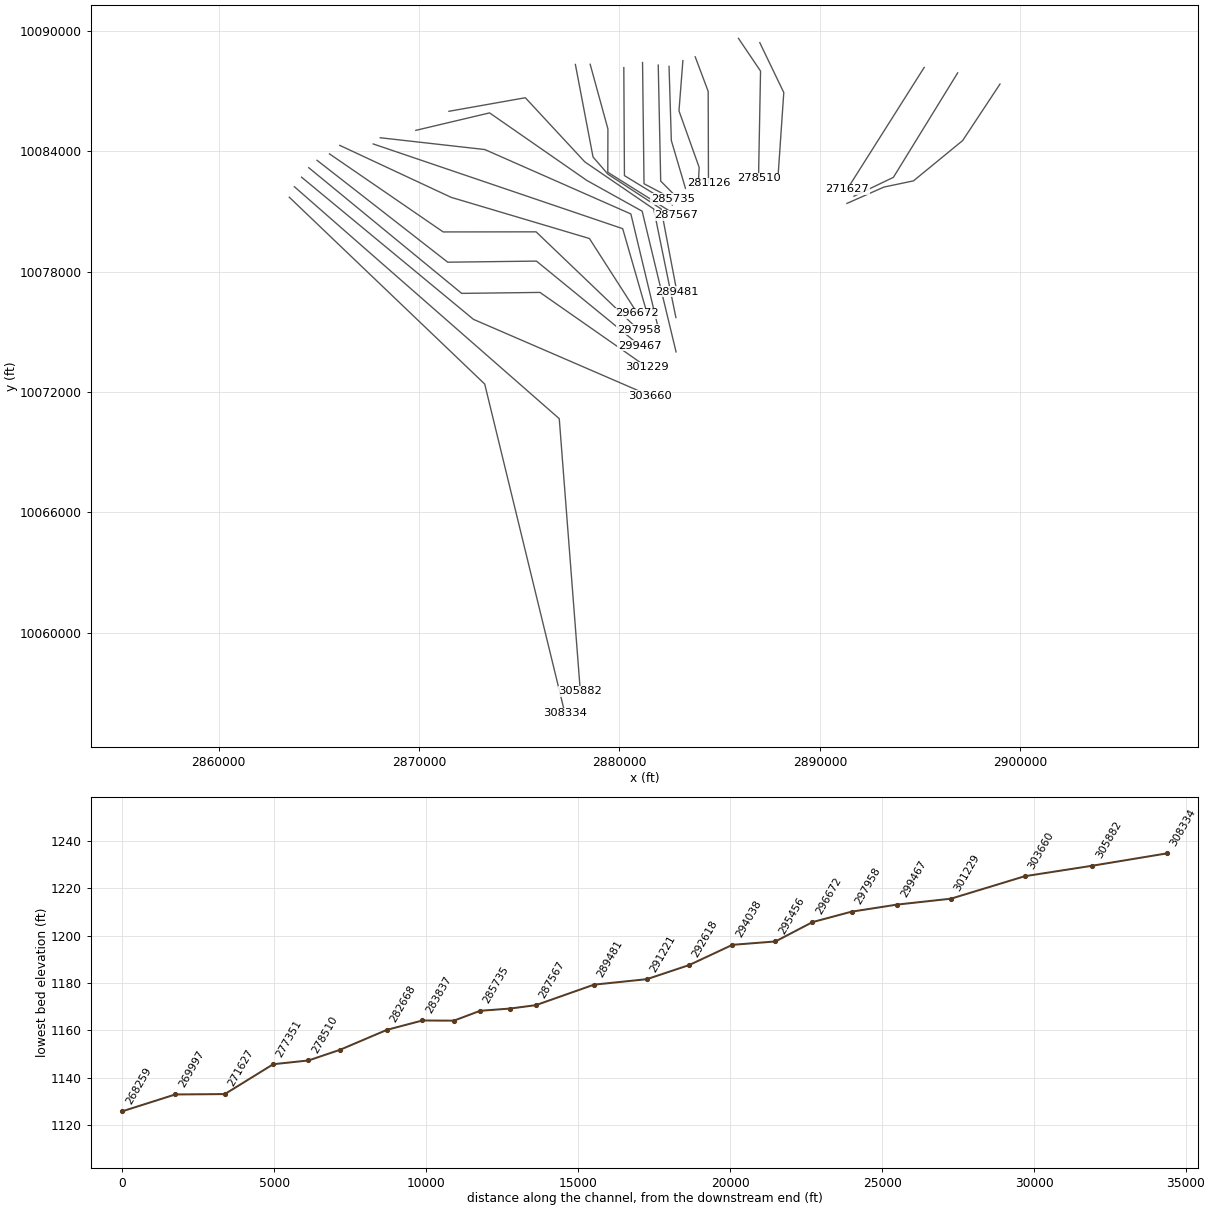
HEC-RAS study PEDERNALES RIVER.prj: PEDERNALES RIVER Base Level Engineering

--- PEDERNALES RIVER.g02 (geometry) --- (continued)

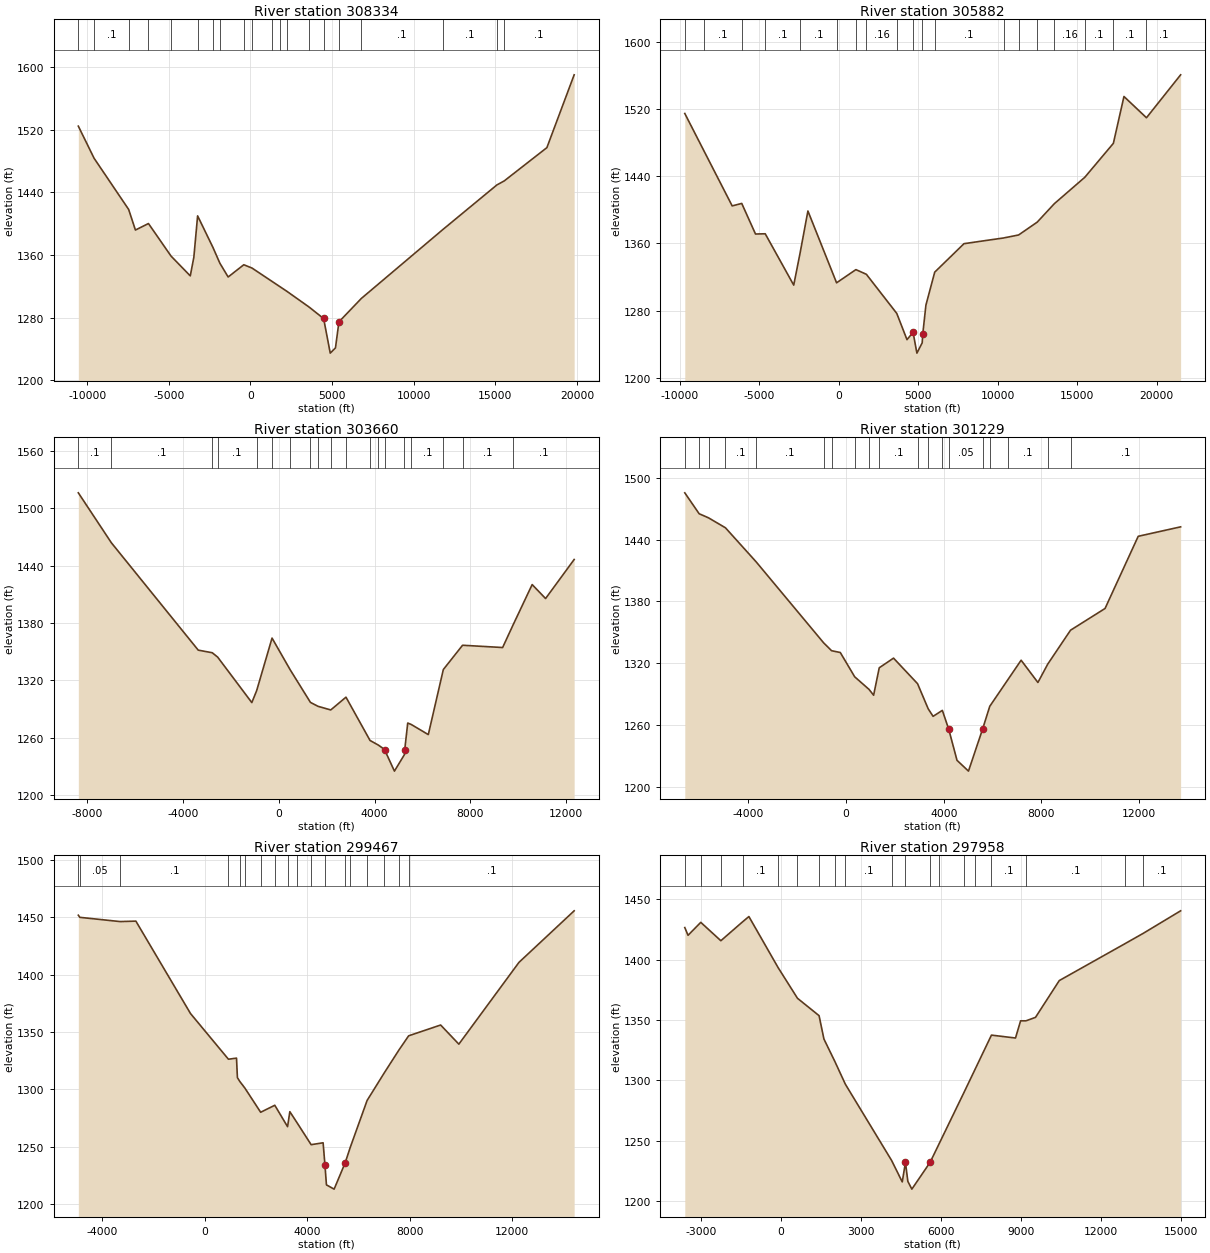
Type RM Length L Ch R = 1 ,308334  ,2452,2452,2452
BEGIN DESCRIPTION:
PEDERNALES RIVER 266.0
END DESCRIPTION:
XS GIS Cut Line= 3
      2863528.56     10081708.37      2873277.75     10072399.95
      2877280.29     10055989.79
#Sta/Elev= 30
-10541.6 1524.33 -9575.8 1483.34 -7458.1 1417.99 -7044.2 1391.71 -6245.6 1400.01
 -4861.7 1358.46 -3684.5 1333.19 -3465.3 1357.08   -3235 1409.82 -2295.2 1369.49
 -1871.7 1349.37 -1364.7 1331.78  -405.3 1347.43    99.7 1343.16  1334.8    1326
  1817.5 1319.29  2232.9 1313.52  3594.4 1293.39  4476.9 1278.83  4482.1  1278.9
  4889.3  1234.6  5208.7 1241.26  5404.2 1271.85  5409.5 1274.29  6793.2 1304.38
   11793 1392.47 15095.7 1449.29 15548.4 1454.47 18158.5  1496.9   19829 1589.85
#Mann= 20 ,-1 , 0
-10541.6      .1       0 -9575.8      .1       0 -7458.1     .16       0
 -6245.6      .1       0 -4861.7      .1       0   -3235     .16       0
 -2295.2      .1       0 -1871.7     .16       0  -405.3      .1       0
    99.7      .1       0  1334.8      .1       0  1817.5     .16       0
  2232.9      .1       0  3594.4     .16       0  4476.9     .05       0
  5404.2     .16       0  6793.2      .1       0   11793      .1       0
 15095.7     .05       0 15548.4      .1       0
Bank Sta=4482.1,5409.5
XS Rating Curve= 0 ,0
Exp/Cntr=0.3,0.1

Type RM Length L Ch R = 1 ,305882  ,2222,2222,2222
BEGIN DESCRIPTION:
PEDERNALES RIVER 268.0
END DESCRIPTION:
XS GIS Cut Line= 3
      2863782.62     10082232.29      2876996.85     10070674.46
      2878048.13      10057092.9
#Sta/Elev= 30
 -9672.7 1514.74 -8461.9 1469.98 -6692.9 1404.69 -6092.2 1407.66 -5226.5 1371.22
 -4614.9 1371.51 -2823.2 1310.38 -2426.7 1348.22 -1931.1 1398.64  -128.5 1313.12
  1085.7 1328.84  1744.7 1323.27  3656.6  1276.7  4298.2 1245.47  4681.6 1254.14
  4922.2 1229.41  5254.9 1241.66    5291 1252.19  5489.4 1286.59  6042.8 1325.83
  7882.9 1359.72 10373.9 1366.53 11317.3 1370.09 12489.5  1385.4 13564.6 1407.34
   15481 1438.79 17275.8 1479.17 17942.3 1534.96 19357.7 1509.65 21505.1 1560.76
#Mann= 19 ,-1 , 0
 -9672.7      .1       0 -8461.9      .1       0 -6092.2     .16       0
 -4614.9      .1       0 -2426.7      .1       0  -128.5      .1       0
  1085.7      .1       0  1744.7     .16       0  3656.6      .1       0
  4681.6     .05       0  5254.9      .1       0  6042.8      .1       0
 10373.9     .05       0 11317.3      .1       0 12489.5     .16       0
 13564.6     .16       0   15481      .1       0 17275.8      .1       0
 19357.7      .1       0
Bank Sta=4681.6,5291
XS Rating Curve= 0 ,0
Exp/Cntr=0.3,0.1

Type RM Length L Ch R = 1 ,303660  ,2431,2431,2431
BEGIN DESCRIPTION:
PEDERNALES RIVER 269.0
END DESCRIPTION:
XS GIS Cut Line= 3
      2864141.38     10082705.47      2872717.58     10075622.38
      2881513.83     10071823.58
#Sta/Elev= 30
 -8372.6 1516.19 -6991.7 1463.89 -3365.9 1351.59   -2782 1348.87 -2555.7 1344.32
 -1127.7 1296.71  -926.8 1309.15  -283.2 1364.19   473.3 1331.06  1320.6  1296.9
  1636.8  1292.8  2167.5    1289  2803.8 1302.37  3807.9  1257.1  4159.5 1252.18
    4418 1247.62  4429.3  1246.7  4826.9 1224.99  5245.8 1242.34  5253.9 1246.66
  5382.4 1275.31  5528.4 1273.81  6241.4 1263.22  6868.9 1331.28  7672.2  1356.7
  9344.8 1354.32  9764.7 1377.07 10578.2 1420.19 11138.8 1405.58 12331.9 1446.43
#Mann= 19 ,-1 , 0
 -8372.6      .1       0 -6991.7      .1       0   -2782     .16       0
 -2555.7      .1       0  -926.8     .16       0  -283.2      .1       0
   473.3     .16       0  1320.6      .1       0  1636.8     .16       0
  2167.5      .1       0  2803.8     .16       0  3807.9      .1       0
  4159.5     .16       0  4429.3     .05       0  5245.8      .1       0
  5528.4      .1       0  6868.9      .1       0  7672.2      .1       0
  9764.7      .1       0
Bank Sta=4418,5253.9
XS Rating Curve= 0 ,0
Exp/Cntr=0.3,0.1

Type RM Length L Ch R = 1 ,301229  ,1762,1762,1762
BEGIN DESCRIPTION:
Mapping XS 468fd7d0
END DESCRIPTION:
XS GIS Cut Line= 4
      2864500.23     10083178.58      2872128.84     10076917.32
      2876034.62     10076964.99      2881392.54     10073228.48
#Sta/Elev= 30
   -6606 1485.26 -6018.7    1465 -5634.9 1461.03 -4941.3 1451.38   -3694 1418.64
  -924.2 1339.98  -594.5 1332.23  -237.6 1330.49   353.4 1306.92   940.9 1294.71
  1127.3  1289.1  1357.8 1315.68  1943.2 1325.04  2927.4 1300.26  3362.7 1275.93
  3562.7 1268.63  3942.6 1274.38    4203 1256.17  4542.8    1226  5012.5 1215.52
 5596.59  1256.7  5884.7 1278.36  6617.6 1303.85  7168.6 1323.02  7856.2 1301.43
  8256.7 1319.15  9192.5 1352.11 10606.2 1373.16 11964.6 1443.13 13701.3 1452.28
#Mann= 19 ,-1 , 0
   -6606      .1       0 -6018.7     .05       0 -5634.9      .1       0
 -4941.3      .1       0   -3694      .1       0  -924.2      .1       0
  -594.5     .16       0   353.4      .1       0   940.9     .16       0
  1357.8      .1       0  2927.4      .1       0  3362.7      .1       0
  3942.6      .1       0    4203     .05       0 5596.59     .16       0
  5884.7     .16       0  6617.6      .1       0  8256.7      .1       0
  9192.5      .1       0
Bank Sta=4203,5596.59
XS Rating Curve= 0 ,0
Exp/Cntr=0.3,0.1

Type RM Length L Ch R = 1 ,299467  ,1509,1509,1509
BEGIN DESCRIPTION:
Mapping XS b7bac6b9
END DESCRIPTION:
XS GIS Cut Line= 4
      2864912.37     10083548.22      2871432.78     10078471.37
      2875859.31     10078525.39      2881013.38     10074318.72
#Sta/Elev= 30
 -4933.2    1452 -4873.8 1450.14   -3304 1446.44 -2688.2 1446.84  -557.4 1366.24
   922.4 1326.37  1237.7 1327.33    1273 1310.31  1360.9 1307.16  1564.7  1301.2
  2179.7  1280.1    2731 1286.21  3229.7 1267.52  3318.7 1280.61  3605.1 1270.77
  4149.4 1251.83  4616.4 1253.47  4686.4 1234.49  4746.4 1216.75  5046.2 1213.05
 5477.27 1236.05  5678.7 1249.68  6332.7 1290.39  7004.6 1314.55  7572.7 1334.34
  7953.6 1346.79  9201.4 1356.21    9912 1339.52 12257.1 1410.85 14410.3 1455.82
#Mann= 18 ,-1 , 0
 -4933.2     .05       0 -4873.8     .05       0   -3304      .1       0
   922.4     .05       0  1360.9     .16       0  1564.7      .1       0
  2179.7      .1       0    2731      .1       0  3229.7     .16       0
  3605.1      .1       0  4149.4     .16       0  4686.4     .05       0
 5477.27      .1       0  5678.7      .1       0  6332.7     .16       0
  7004.6      .1       0  7572.7      .1       0  7953.6      .1       0
Bank Sta=4686.4,5477.27
XS Rating Curve= 0 ,0
Exp/Cntr=0.3,0.1

Type RM Length L Ch R = 1 ,297958  ,1286,1286,1286
BEGIN DESCRIPTION:
Mapping XS 5d83a6b7
END DESCRIPTION:
XS GIS Cut Line= 4
      2865533.48     10083868.29      2871206.05     10079979.05
      2875841.51     10079983.54      2880952.96     10075098.31
#Sta/Elev= 30
 -3603.8 1426.52 -3481.7 1420.12   -3005 1430.83 -2252.1 1415.63 -1432.9 1431.35
 -1201.3 1435.63  -108.8 1393.48   619.6    1368  1428.6 1353.61    1611 1334.28
  2015.6 1315.93  2414.8 1296.86    4150 1233.69  4546.4 1216.02  4666.4 1232.21
  4756.4 1216.47  4906.2 1210.05 5590.91 1232.23  5915.3 1247.01  6860.8 1290.07
  7268.2 1308.85  7889.7 1337.51  8791.1 1335.11  8982.4 1349.34  9182.5 1349.33
  9540.9  1352.2 10432.3 1382.65 12905.5 1413.32 13574.1 1421.68   14980 1440.37
#Mann= 19 ,-1 , 0
 -3603.8     .16       0   -3005      .1       0 -2252.1     .16       0
 -1432.9      .1       0  -108.8      .1       0   619.6      .1       0
  1428.6     .16       0  2015.6      .1       0  2414.8      .1       0
    4150      .1       0  4666.4     .05       0 5590.91      .1       0
  5915.3      .1       0  6860.8     .16       0  7268.2      .1       0
  7889.7      .1       0  9182.5      .1       0 12905.5      .1       0
 13574.1      .1       0
Bank Sta=4666.4,5590.91
XS Rating Curve= 0 ,0
Exp/Cntr=0.3,0.1

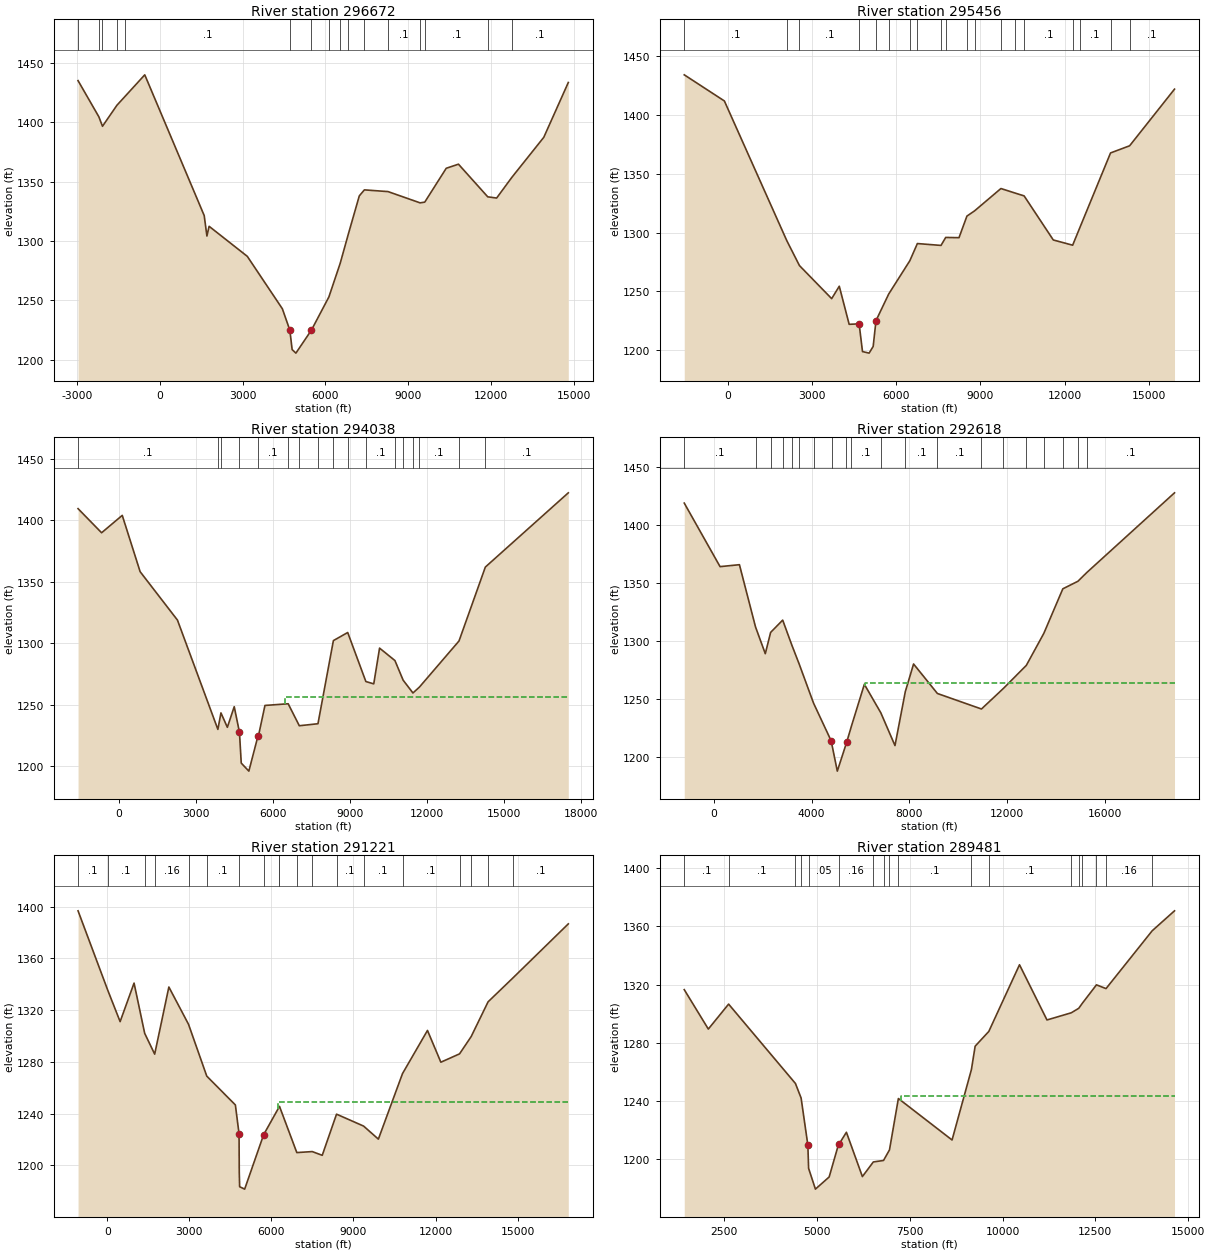
Type RM Length L Ch R = 1 ,296672  ,1216,1216,1216
BEGIN DESCRIPTION:
Mapping XS 632ee251
END DESCRIPTION:
XS GIS Cut Line= 4
      2866049.23     10084291.22      2871601.69     10081702.67
      2878501.88     10079651.43      2880891.13     10075930.51
#Sta/Elev= 30
 -2953.4 1435.02 -2198.7  1404.5 -2068.8 1396.59 -1548.5 1414.21   -1255 1421.68
  -538.5  1439.9  1613.6 1321.43  1711.1 1304.23  1790.7  1312.4  3172.8 1287.12
  4442.2    1243  4713.5 1224.97  4796.3 1208.64  4932.3 1205.65  5495.2 1225.04
  6126.5 1252.93  6537.9 1281.38  6820.9 1305.05  7227.7 1338.03    7412 1343.06
  8267.5 1341.61  9428.4 1332.13  9597.4 1332.76 10374.5 1361.24 10816.5  1364.7
 11877.4 1337.21 12198.8 1336.18 12752.8 1353.68 13906.8 1387.34 14793.4 1433.44
#Mann= 16 ,-1 , 0
 -2953.4     .16       0 -2198.7     .05       0 -2068.8      .1       0
 -1548.5     .16       0   -1255      .1       0  4713.5     .05       0
  5495.2      .1       0  6126.5      .1       0  6537.9     .16       0
  6820.9     .16       0    7412      .1       0  8267.5      .1       0
  9428.4     .16       0  9597.4      .1       0 11877.4     .16       0
 12752.8      .1       0
Bank Sta=4713.5,5495.2
XS Rating Curve= 0 ,0
Exp/Cntr=0.3,0.1

Type RM Length L Ch R = 1 ,295456  ,1418,1418,1418
BEGIN DESCRIPTION:
Mapping XS 9e6836ef
END DESCRIPTION:
XS GIS Cut Line= 3
      2867714.99     10084363.64      2880162.61     10080140.47
      2881359.12     10075988.56
#Sta/Elev= 30
 -1550.2 1434.33  -120.9  1412.1  2104.3 1293.15  2554.1    1272  3701.7 1243.87
  3972.6 1254.44  4324.8 1222.02  4683.8 1222.42  4689.5 1220.47  4799.9 1198.83
  5034.7 1197.51  5180.1  1203.2  5280.9 1225.15  5733.5  1247.8  6486.1 1276.13
  6755.1 1290.75  7596.7 1289.16  7763.9 1295.95  8237.7 1295.75  8520.3 1314.12
  8790.4 1318.53  9731.3 1337.57 10240.3 1333.69 10557.5 1331.31 11596.8 1293.81
 12286.8 1289.35 12538.1 1304.02 13636.5 1367.85 14316.6 1373.95 15915.2 1422.15
#Mann= 19 ,-1 , 0
 -1550.2      .1       0  2104.3     .16       0  2554.1      .1       0
  4689.5     .05       0  5280.9     .16       0  5733.5      .1       0
  6486.1      .1       0  6755.1     .16       0  7596.7     .16       0
  7763.9      .1       0  8520.3     .16       0  8790.4      .1       0
  9731.3      .1       0 10240.3     .16       0 10557.5      .1       0
 12286.8     .16       0 12538.1      .1       0 13636.5      .1       0
 14316.6      .1       0
Bank Sta=4683.8,5280.9
XS Rating Curve= 0 ,0
Exp/Cntr=0.3,0.1

Type RM Length L Ch R = 1 ,294038  ,1420,1420,1420
BEGIN DESCRIPTION:
Mapping XS 98904cda
END DESCRIPTION:
XS GIS Cut Line= 4
       2868067.1     10084671.76      2873282.73     10084084.33
      2880570.32     10080874.63      2881942.21     10075162.07
#Sta/Elev= 30
 -1598.3 1409.27    -682 1389.68   122.6 1403.81   818.2 1358.09  2271.6 1318.76
  3845.4 1229.99    3965 1243.38  4214.7 1231.68  4482.2 1248.43  4685.3 1227.64
  4755.3  1202.6  5051.4 1196.08  5400.1 1224.08  5423.5 1224.55  5678.6 1249.43
  6582.6 1250.79  7015.8 1232.94    7742 1234.57  8342.7 1302.09  8900.4 1308.66
  9607.4 1268.83  9914.2 1266.96 10140.6 1295.99 10738.1  1285.9   11059 1269.92
 11440.3 1259.56 11692.3 1264.35 13233.8  1301.8 14258.7 1361.82 17488.4 1422.12
#Mann= 17 ,-1 , 0
 -1598.3      .1       0  3845.4     .16       0    3965     .16       0
  4685.3     .05       0  5400.1      .1       0  6582.6     .16       0
  7015.8      .1       0    7742     .16       0  8342.7      .1       0
  8900.4     .16       0  9607.4      .1       0 10738.1     .16       0
   11059     .16       0 11440.3     .16       0 11692.3      .1       0
 13233.8      .1       0 14258.7      .1       0
#XS Ineff= 2 , 0
                         6463.07         1256.63
Permanent Ineff=
       F       F
Bank Sta=4685.3,5423.5
XS Rating Curve= 0 ,0
Exp/Cntr=0.3,0.1

Type RM Length L Ch R = 1 ,292618  ,1397,1397,1397
BEGIN DESCRIPTION:
Mapping XS cafbb9bf
END DESCRIPTION:
XS GIS Cut Line= 5
       2869842.2     10085040.64      2873520.87     10085910.18
      2878379.79     10082540.62      2881132.89     10081011.71
      2882824.48     10074000.95
#Sta/Elev= 30
 -1206.6 1418.82   258.5    1364  1050.5 1365.68  1708.6 1311.99  2108.6 1288.89
  2326.9 1307.26  2820.1 1317.87  3191.4 1296.45  3489.9 1280.24  4081.9 1246.26
  4810.2  1213.4  4818.9 1212.03  5054.5 1187.58  5415.4 1211.06  5436.4  1212.4
  5634.6 1226.59  6161.2 1262.48  6833.9 1237.91  7413.5 1209.62  7835.7 1256.15
  8174.2 1280.01  9148.9 1254.56 10951.3 1241.18 11851.4 1258.97 12786.5 1278.83
 13501.8 1306.41 14279.1 1344.85 14896.3 1351.37 15254.9 1358.82 18847.5 1427.68
#Mann= 20 ,-1 , 0
 -1206.6      .1       0  1708.6      .1       0  2326.9      .1       0
  2820.1      .1       0  3191.4      .1       0  3489.9     .16       0
  4081.9      .1       0  4818.9     .05       0  5415.4      .1       0
  5634.6      .1       0  6833.9     .16       0  7835.7      .1       0
  9148.9      .1       0 10951.3      .1       0 11851.4      .1       0
 12786.5      .1       0 13501.8      .1       0 14279.1      .1       0
 14896.3     .16       0 15254.9      .1       0
#XS Ineff= 2 , 0
                         6193.18         1263.39
Permanent Ineff=
       F       F
Bank Sta=4810.2,5436.4
XS Rating Curve= 0 ,0
Exp/Cntr=0.3,0.1

Type RM Length L Ch R = 1 ,291221  ,1740,1740,1740
BEGIN DESCRIPTION:
Mapping XS 4bb0072c
END DESCRIPTION:
XS GIS Cut Line= 5
      2871492.99     10085989.61      2875304.21     10086665.47
      2878272.98     10083468.15      2881708.81     10081122.92
      2882816.62     10075710.92
#Sta/Elev= 30
 -1066.8 1396.68      17 1335.44   470.9 1311.05   980.1 1340.84  1368.5 1302.02
    1734 1285.92  2252.3  1337.8  2969.9 1309.04  3637.3 1268.95  4683.3 1246.66
  4817.6 1224.31    4825 1194.82  4839.1 1183.47  5022.6 1181.61  5716.2 1223.67
  6295.5 1245.58  6928.7 1209.86  7493.6 1210.62  7857.7 1207.74  8380.4 1239.54
  9368.1 1230.35  9909.6 1220.25 10791.3 1270.88   11704 1304.24 12193.2 1279.69
 12876.3 1286.14 13300.5 1299.48 13919.3 1326.36 14818.9 1344.65 16851.1 1386.59
#Mann= 19 ,-1 , 0
 -1066.8      .1       0      17      .1       0  1368.5      .1       0
    1734     .16       0  2969.9      .1       0  3637.3      .1       0
  4817.6     .05       0  5716.2     .16       0  6295.5      .1       0
  6295.5     .16       0  6928.7      .1       0  7493.6      .1       0
  8380.4      .1       0  9368.1      .1       0 10791.3      .1       0
 12876.3     .16       0 13300.5      .1       0 13919.3      .1       0
 14818.9      .1       0
#XS Ineff= 2 , 0
                            6250         1249.19
Permanent Ineff=
       F       F
Bank Sta=4817.6,5716.2
XS Rating Curve= 0 ,0
Exp/Cntr=0.3,0.1

Type RM Length L Ch R = 1 ,289481  ,1914,1914,1914
BEGIN DESCRIPTION:
Mapping XS 0e9bef21
END DESCRIPTION:
XS GIS Cut Line= 5
      2877801.37     10088323.55      2878682.34     10083711.87
      2879430.69     10082852.94      2882077.68     10081127.42
      2882866.06     10076992.02
#Sta/Elev= 30
  1427.8 1316.48  2076.3 1289.37  2622.6 1306.53  4422.6 1251.94  4575.4 1241.92
  4756.7 1209.59  4777.1 1193.59  4960.7  1179.3  5330.7 1187.66  5591.2 1210.81
  5596.3 1210.23  5795.2 1218.41  6225.5 1187.93  6520.1 1197.99  6794.6    1199
  6955.3 1206.27  7194.9 1241.61  8640.7 1213.09  9161.6 1261.48  9262.3 1277.58
  9631.2 1287.77   10457 1333.59 11197.2 1295.63 11852.2 1300.56 12052.4 1303.65
 12143.4  1306.9 12529.7 1319.78 12787.4  1317.2 14030.5 1356.95 14631.7 1370.68
#Mann= 18 ,-1 , 0
  1427.8      .1       0  2622.6      .1       0  4422.6     .16       0
  4575.4      .1       0  4777.1     .05       0  5591.2     .16       0
  6520.1      .1       0  6794.6      .1       0  6955.3     .16       0
  7194.9      .1       0  9161.6     .16       0  9631.2      .1       0
 11852.2     .16       0 12052.4     .16       0 12143.4      .1       0
 12529.7      .1       0 12787.4     .16       0 14030.5      .1       0
#XS Ineff= 2 , 0
                         7272.73         1243.55
Permanent Ineff=
       F       F
Bank Sta=4756.7,5596.3
XS Rating Curve= 0 ,0
Exp/Cntr=0.3,0.1

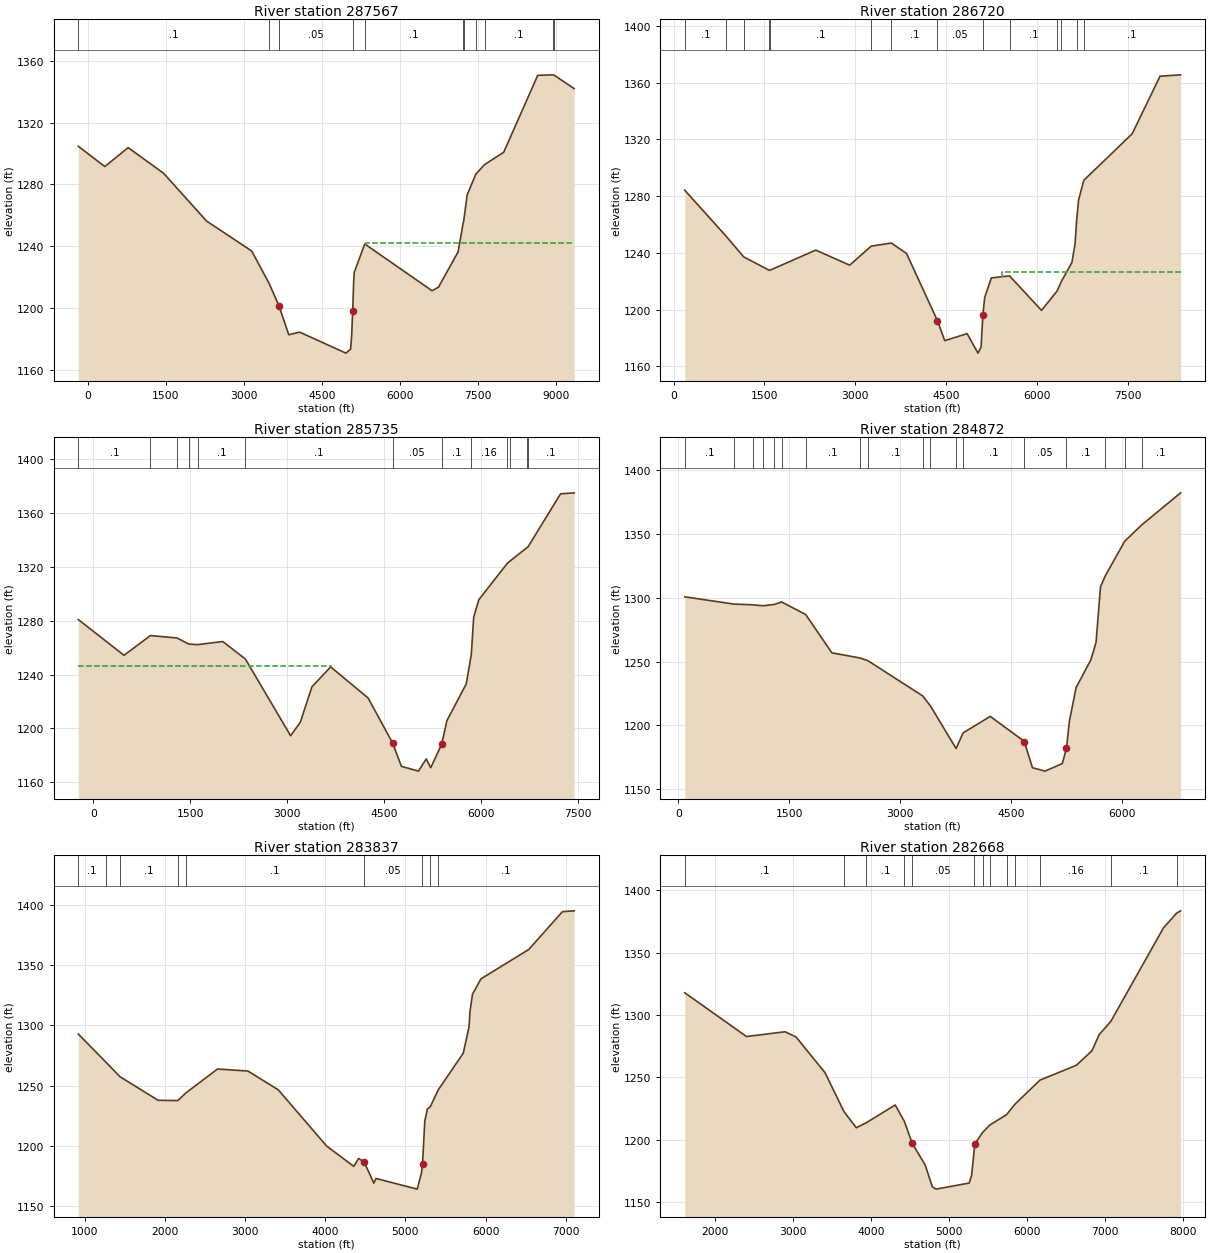
Type RM Length L Ch R = 1 ,287567  ,847,847,847
BEGIN DESCRIPTION:
Mapping XS 5d15e5cf
END DESCRIPTION:
XS GIS Cut Line= 4
       2878539.1     10088332.59      2879424.83     10085109.85
      2879418.64     10082950.45      2882841.18     10080809.03
#Sta/Elev= 30
  -185.5 1304.71   324.1 1291.56   773.5 1303.83  1455.3  1287.2    2280  1256.3
  3149.6 1236.84  3484.7 1215.86  3672.9 1201.44  3862.9 1182.59  4072.9 1184.26
  4962.6 1170.66  5052.9 1173.29  5072.9 1182.02  5092.9 1198.16  5112.9 1217.88
  5122.9 1223.01  5324.8 1241.39  6619.8  1211.1  6743.3 1213.42  7120.7 1236.23
  7216.7  1254.7  7228.8 1256.33  7295.4 1273.25  7462.6 1286.68  7629.6 1292.83
    7998 1300.81  8652.4 1350.65    8945    1351  8973.9 1350.66  9353.4 1342.09
#Mann= 11 ,-1 , 0
  -185.5      .1       0  3484.7     .16       0  3672.9     .05       0
  5092.9     .16       0  5324.8      .1       0  7216.7     .16       0
  7228.8      .1       0  7462.6     .16       0  7629.6      .1       0
    8945     .16       0  8973.9      .1       0
#XS Ineff= 2 , 0
                         5343.18         1241.99
Permanent Ineff=
       F       F
Bank Sta=3672.9,5092.9
XS Rating Curve= 0 ,0
Exp/Cntr=0.3,0.1

Type RM Length L Ch R = 1 ,286720  ,985,985,985
BEGIN DESCRIPTION:
Mapping XS 2efcf93c
END DESCRIPTION:
XS GIS Cut Line= 3
      2880217.95     10088166.49      2880248.95     10082784.81
      2882644.43     10081321.56
#Sta/Elev= 30
   185.8 1284.13   874.4 1251.42  1158.3 1237.13  1578.5 1227.74  1593.4 1227.74
  2348.6 1241.92  2908.6 1231.29  3264.6 1244.72  3596.9 1246.88  3848.6 1239.49
  4358.6 1192.09  4478.6 1178.06  4848.6 1182.98  5028.4 1169.24  5078.6 1173.49
  5108.6 1195.89  5138.6 1208.46  5248.6 1222.31  5548.6 1223.74  6077.4 1199.37
  6335.2  1213.1  6404.5 1219.77  6578.7 1233.15  6630.9 1246.13  6656.5 1262.36
    6689 1277.22  6775.3 1291.12  7575.5 1324.02  8034.2 1364.56  8374.6 1365.55
#Mann= 14 ,-1 , 0
   185.8      .1       0   874.4     .16       0  1158.3      .1       0
  1578.5     .05       0  1593.4      .1       0  3264.6     .16       0
  3596.9      .1       0  4358.6     .05       0  5108.6     .16       0
  5548.6      .1       0  6335.2     .16       0  6404.5      .1       0
  6656.5     .16       0  6775.3      .1       0
#XS Ineff= 2 , 0
                         5426.14         1226.66
Permanent Ineff=
       F       F
Bank Sta=4358.6,5108.6
XS Rating Curve= 0 ,0
Exp/Cntr=0.3,0.1

Type RM Length L Ch R = 1 ,285735  ,863,863,863
BEGIN DESCRIPTION:
Mapping XS bbd2c49a
END DESCRIPTION:
XS GIS Cut Line= 3
      2881152.35     10088420.92      2881226.14     10082380.07
      2882675.01     10081617.28
#Sta/Elev= 30
  -232.5    1281   474.7 1254.39   883.7 1269.09  1296.9 1267.27  1478.4 1262.73
  1617.6 1262.36  2004.9 1264.65  2354.9 1251.63  3054.9 1194.61  3204.9 1204.55
    3385 1230.97    3675 1245.79    4255 1222.66  4635.1 1189.21  4770.7 1171.84
  5034.8 1168.29  5155.1 1177.33  5225.1 1170.85  5395.1 1188.31  5475.1 1205.78
  5775.1 1233.13  5852.8 1254.69  5890.5 1282.73  5969.7 1295.71  6408.7 1322.65
    6450 1324.36  6712.7 1334.38  6732.2 1335.06  7235.4 1374.47  7446.2 1375.21
#Mann= 13 ,-1 , 0
  -232.5      .1       0   883.7     .16       0  1296.9      .1       0
  1478.4     .16       0  1617.6      .1       0  2354.9      .1       0
  4635.1     .05       0  5395.1      .1       0  5852.8     .16       0
  6408.7     .16       0    6450      .1       0  6712.7     .16       0
  6732.2      .1       0
#XS Ineff= 2 , 0
         3681.82 1246.37
Permanent Ineff=
       F       F
Bank Sta=4635.1,5395.1
XS Rating Curve= 0 ,0
Exp/Cntr=0.3,0.1

Type RM Length L Ch R = 1 ,284872  ,1035,1035,1035
BEGIN DESCRIPTION:
Mapping XS 5be24633
END DESCRIPTION:
XS GIS Cut Line= 3
      2881935.19     10088291.62      2882057.88     10082511.76
      2882708.21     10081859.97
#Sta/Elev= 30
    87.1 1300.68   749.5 1295.01  1002.7 1294.44  1146.3 1293.69  1297.5 1294.74
  1395.8 1296.66  1721.1 1286.83  2075.4 1256.82  2459.4 1252.72  2561.8 1250.66
  3303.4 1223.04  3406.4 1215.28  3754.4 1181.86  3848.5 1194.06  4215.9 1207.02
    4666 1187.85    4676 1187.31    4786 1166.83  4955.8 1164.14  5190.2 1170.09
  5246.2 1182.19  5286.2 1203.41  5376.2 1229.61  5576.2 1251.35  5646.2 1265.13
  5706.3 1308.64  5771.1 1317.15    6033 1344.23  6264.3 1357.08    6789 1382.16
#Mann= 18 ,-1 , 0
    87.1      .1       0   749.5      .1       0  1002.7     .16       0
  1146.3      .1       0  1297.5     .16       0  1395.8      .1       0
  1721.1      .1       0  2459.4     .05       0  2561.8      .1       0
  3303.4     .16       0  3406.4      .1       0  3754.4     .16       0
  3848.5      .1       0    4666     .05       0  5246.2      .1       0
  5771.1      .1       0    6033     .16       0  6264.3      .1       0
Bank Sta=4676,5246.2
XS Rating Curve= 0 ,0
Exp/Cntr=0.3,0.1

Type RM Length L Ch R = 1 ,283837  ,1169,1169,1169
BEGIN DESCRIPTION:
Mapping XS a3bec1fe
END DESCRIPTION:
XS GIS Cut Line= 3
      2882474.16     10088228.69      2882588.76     10084532.17
      2883294.45     10082146.86
#Sta/Elev= 30
   919.3 1292.74  1260.1 1269.68  1436.7 1257.52  1914.7 1237.84  2160.5 1237.62
  2259.3 1243.83  2655.1 1263.76  3035.3 1262.11  3415.5 1246.43  4015.7    1200
  4355.9 1183.06  4415.9 1189.64    4486 1186.61    4606 1169.19  4632.9 1173.05
  5147.6 1164.21  5201.7 1178.13 5213.64 1185.36  5241.7 1220.54  5273.4 1230.57
  5309.4  1232.4    5408 1246.33  5721.4 1276.87  5793.3 1298.44  5804.8 1311.13
    5837 1325.85    5942 1338.48  6538.8 1362.87  6958.9 1394.22  7105.1  1394.9
#Mann= 9 ,-1 , 0
   919.3      .1       0  1260.1     .16       0  1436.7      .1       0
  2160.5     .16       0  2259.3      .1       0    4486     .05       0
  5201.7     .05       0  5309.4     .16       0    5408      .1       0
Bank Sta=4486,5213.64
XS Rating Curve= 0 ,0
Exp/Cntr=0.3,0.1

Type RM Length L Ch R = 1 ,282668  ,1542,1542,1542
BEGIN DESCRIPTION:
Mapping XS a81cf08a
END DESCRIPTION:
XS GIS Cut Line= 4
      2883165.11     10088514.96      2882969.99     10086012.54
      2883976.65     10083194.93      2883934.97      10082343.7
#Sta/Elev= 30
  1609.8 1317.83  2400.6 1282.74  2894.9 1286.57  3035.3  1282.4  3406.5 1253.75
  3650.6 1222.39  3807.7 1209.51    3937  1213.6  4306.4  1227.8  4424.3 1214.55
  4522.1 1197.34  4690.8 1179.55  4783.1 1162.03  4829.8 1160.27  5254.5 1165.15
  5285.3 1171.27  5321.4 1193.28  5329.1 1196.74  5425.3 1205.67  5517.8 1211.69
  5733.9 1220.04  5836.8 1228.16  6160.9 1247.73  6628.4 1259.68  6826.4 1271.21
  6920.4 1284.23  7071.1 1295.04  7743.8  1369.9  7912.3 1381.77  7964.1 1383.62
#Mann= 13 ,-1 , 0
  1609.8      .1       0  3650.6     .16       0    3937      .1       0
  4424.3     .16       0  4522.1     .05       0  5321.4      .1       0
  5425.3     .16       0  5517.8      .1       0  5733.9     .16       0
  5836.8      .1       0  6160.9     .16       0  7071.1      .1       0
  7912.3     .16       0
Bank Sta=4522.1,5329.1
XS Rating Curve= 0 ,0
Exp/Cntr=0.3,0.1

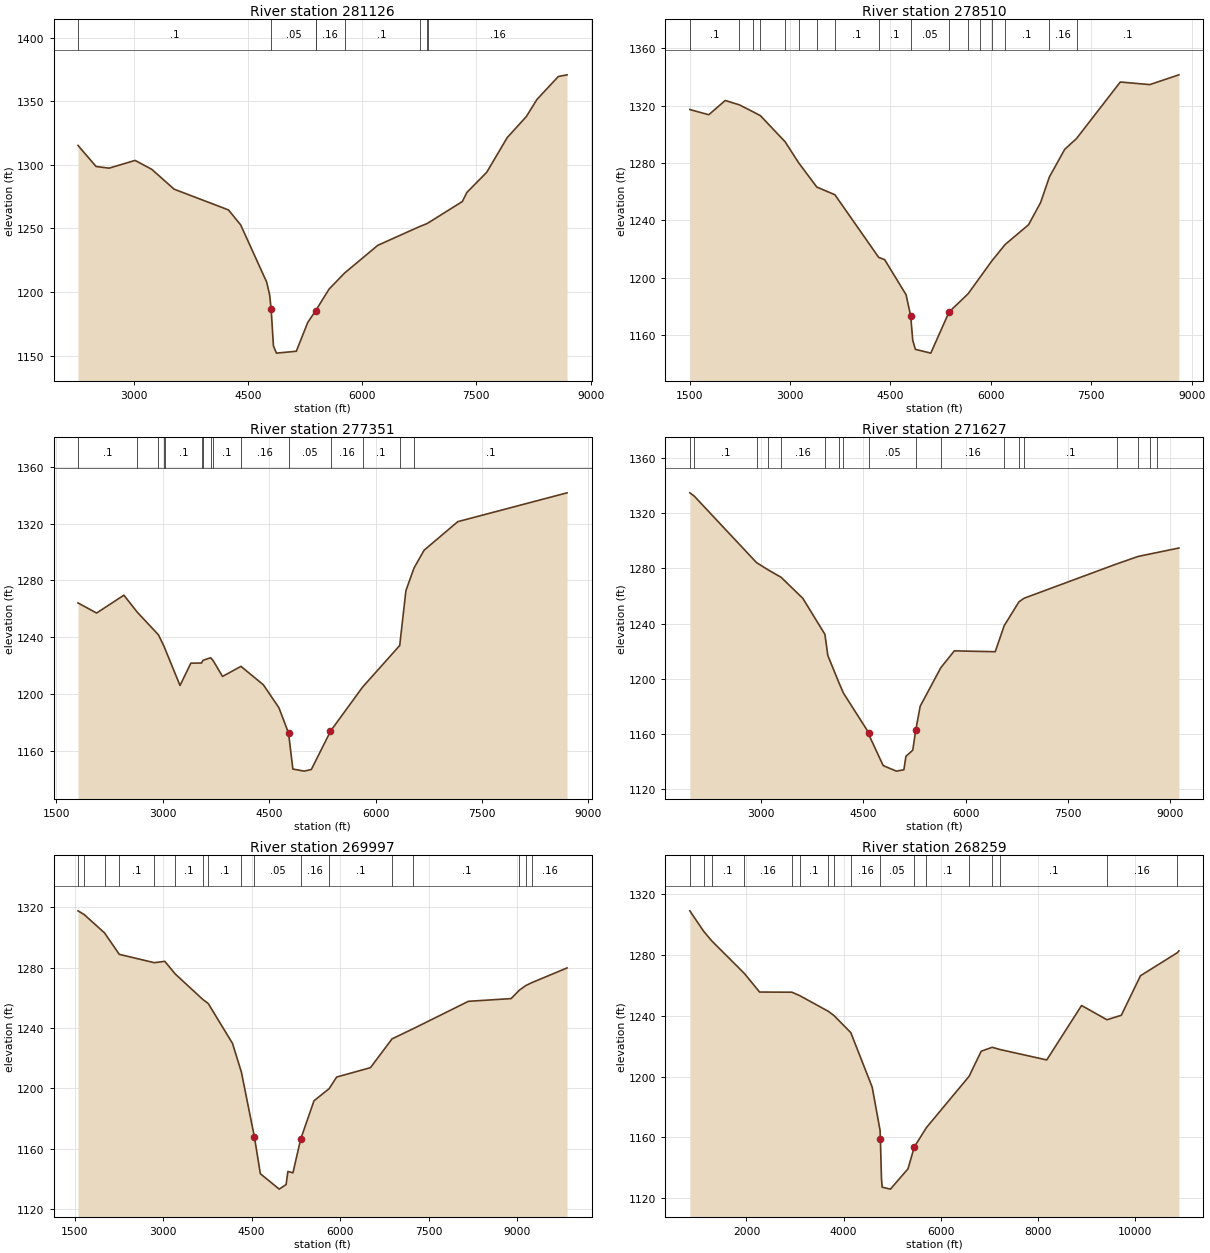
Type RM Length L Ch R = 1 ,281126  ,1041,1041,1041
BEGIN DESCRIPTION:
Mapping XS 92669579
END DESCRIPTION:
XS GIS Cut Line= 3
      2883780.87     10088703.06      2884426.92     10086981.74
      2884441.25     10082398.63
#Sta/Elev= 30
  2268.7 1315.32    2506 1298.76  2676.9 1297.43  3018.5 1303.54  3239.2 1296.44
    3531 1280.89  4245.3 1264.55  4405.3 1252.73  4745.3  1207.9  4785.3 1197.75
  4805.3 1186.27  4835.3 1157.45    4875 1151.87  5135.3 1153.35  5285.3 1175.98
  5390.5 1185.38  5565.3 1202.25  5769.9 1214.93  6205.9 1236.73  6756.7 1251.53
  6847.8 1253.71  6866.4 1254.34  7315.3 1271.15  7375.3 1278.35  7635.3 1294.16
  7905.3 1321.54  8155.3 1338.01  8295.3 1351.51  8575.3 1369.53  8690.4 1370.88
#Mann= 8 ,-1 , 0
  2268.7      .1       0  4805.3     .05       0  5390.5      .1       0
  5390.5     .16       0  5769.9      .1       0  6756.7     .16       0
  6847.8      .1       0  6866.4     .16       0
Bank Sta=4805.3,5390.5
XS Rating Curve= 0 ,0
Exp/Cntr=0.3,0.1

Type RM Length L Ch R = 1 ,278510  ,1159,1159,1159
BEGIN DESCRIPTION:
Mapping XS 6115e061
END DESCRIPTION:
XS GIS Cut Line= 3
      2885936.27     10089625.26      2887039.59     10087992.85
      2886938.13     10082658.51
#Sta/Elev= 30
  1503.1 1317.33  1786.2 1313.72  2031.9 1323.66  2243.6  1320.6  2442.5 1315.89
  2557.9 1313.05  2926.8 1294.83  3130.1  1280.1  3399.7 1263.27  3670.5 1257.87
  4324.5 1214.16  4412.7 1212.65  4732.7 1188.18  4802.8 1173.25  4832.8 1156.33
  4872.8    1150  5102.6 1147.37  5375.5 1176.07  5659.3 1188.76  5833.7 1200.02
  6011.7 1211.55  6213.5 1223.18  6563.1 1236.96  6743.1 1252.46  6873.2 1270.19
  7103.2 1289.58  7279.6 1297.11  7933.3 1336.55  8373.4 1334.74  8808.7 1341.56
#Mann= 17 ,-1 , 0
  1503.1      .1       0  2243.6     .16       0  2442.5      .1       0
  2557.9      .1       0  2926.8     .16       0  3130.1     .16       0
  3399.7      .1       0  3670.5      .1       0  4324.5      .1       0
  4802.8     .05       0  5375.5     .16       0  5659.3      .1       0
  5833.7     .16       0  6011.7      .1       0  6213.5      .1       0
  6873.2     .16       0  7279.6      .1       0
Bank Sta=4802.8,5375.5
XS Rating Curve= 0 ,0
Exp/Cntr=0.3,0.1

Type RM Length L Ch R = 1 ,277351  ,1593,1593,1593
BEGIN DESCRIPTION:
Mapping XS 9b352956
END DESCRIPTION:
XS GIS Cut Line= 3
      2887001.43      10089409.1      2888198.51     10086923.67
      2887915.76     10082796.93
#Sta/Elev= 30
  1804.6 1264.18  2067.1 1257.07  2451.7 1269.64  2641.5 1257.61  2939.1 1241.72
  3019.4 1233.48  3031.5  1231.9    3243 1206.07  3395.8 1221.79    3546 1221.89
  3567.4 1223.79  3674.4 1225.61  3708.7 1223.69  3842.3 1212.45  4102.2 1219.54
  4418.9 1206.52  4637.7 1190.39  4773.7 1172.53  4833.9 1147.26    4994 1145.79
  5094.5 1146.95  5364.3 1173.83  5375.1 1174.66  5817.7    1205  6340.4 1234.21
  6427.6  1272.8  6542.8 1288.85  6684.2 1301.29  7159.3  1321.4  8699.7 1341.69
#Mann= 15 ,-1 , 0
  1804.6      .1       0  2641.5     .16       0  2939.1      .1       0
  3019.4     .16       0  3031.5      .1       0    3546     .16       0
  3567.4      .1       0  3674.4     .16       0  3708.7      .1       0
  4102.2     .16       0  4773.7     .05       0  5375.1     .16       0
  5817.7      .1       0  6340.4     .16       0  6542.8      .1       0
Bank Sta=4773.7,5364.3
XS Rating Curve= 0 ,0
Exp/Cntr=0.3,0.1

Type RM Length L Ch R = 1 ,271627  ,1630,1630,1630
BEGIN DESCRIPTION:
Mapping XS 20aac99c
END DESCRIPTION:
XS GIS Cut Line= 2
      2895204.11     10088176.03      2891361.63     10082108.13
#Sta/Elev= 30
    1950 1334.71    2014 1332.38  2930.1 1284.16  3097.3 1279.01  3290.3 1273.56
  3609.3 1258.33  3933.7 1232.25  3976.7 1216.93  4137.1 1197.53  4205.4 1189.75
  4580.4 1160.73  4586.5 1158.74  4789.9  1137.2  4983.7  1133.2  5093.3 1134.18
  5123.9 1143.97  5223.9 1148.37  5266.9 1162.69  5333.2 1180.21  5635.5 1208.06
  5834.1 1220.28    6435 1219.66  6566.5  1238.5  6783.1 1255.76    6859 1258.39
  8216.9 1283.21  8536.9 1288.69  8702.9 1290.38    8809 1291.46  9132.2 1294.75
#Mann= 18 ,-1 , 0
    1950     .16       0    2014      .1       0  2930.1     .16       0
  3097.3      .1       0  3290.3     .16       0  3933.7      .1       0
  4137.1     .16       0  4205.4      .1       0  4586.5     .05       0
  5266.9      .1       0  5635.5     .16       0  6566.5      .1       0
  6783.1     .16       0    6859      .1       0  8216.9     .16       0
  8536.9      .1       0  8702.9     .16       0    8809      .1       0
Bank Sta=4580.4,5266.9
XS Rating Curve= 0 ,0
Exp/Cntr=0.3,0.1

Type RM Length L Ch R = 1 ,269997  ,1738,1738,1738
BEGIN DESCRIPTION:
Mapping XS 833a2dfa
END DESCRIPTION:
XS GIS Cut Line= 3
      2896874.13     10087904.81      2893666.93      10082698.8
       2891699.9     10081758.38
#Sta/Elev= 30
  1554.1 1317.71    1658 1315.27  2004.4 1303.07  2254.4 1288.85  2847.5 1283.31
  3026.4  1284.2  3203.4  1275.8  3672.4 1258.88  3762.3 1256.26  4174.6 1229.76
  4325.8 1210.64  4546.6  1167.6  4647.1 1143.27  4967.5 1133.05  5083.6 1136.07
  5114.2  1144.8  5199.6 1143.87  5330.9 1166.22  5556.9 1191.67    5813 1199.68
  5941.3 1207.42  6515.1 1213.66  6880.5 1232.75  7243.2 1239.56  8175.1 1257.66
  8900.3 1259.48  9038.5 1265.01  9144.3 1268.01  9251.5 1270.06    9849 1279.82
#Mann= 17 ,-1 , 0
  1554.1      .1       0    1658     .16       0  2004.4     .16       0
  2254.4      .1       0  2847.5     .16       0  3203.4      .1       0
  3672.4     .16       0  3762.3      .1       0  4325.8      .1       0
  4546.6     .05       0  5330.9     .16       0    5813      .1       0
  6880.5     .16       0  7243.2      .1       0  9038.5     .16       0
  9144.3      .1       0  9251.5     .16       0
Bank Sta=4546.6,5330.9
XS Rating Curve= 0 ,0
Exp/Cntr=0.3,0.1

Type RM Length L Ch R = 1 ,268259  ,1359,1359,1359
BEGIN DESCRIPTION:
Mapping XS 9c8e1187
END DESCRIPTION:
XS GIS Cut Line= 5
      2898985.12     10087347.26      2897123.72     10084532.79
      2894669.09     10082523.56      2893193.68     10082213.84
      2891349.42     10081399.59
#Sta/Elev= 30
     834 1309.06  1115.5 1295.75  1287.1 1289.24  1955.7 1267.91    2270 1255.63
  2935.2 1255.53  3092.2 1253.35    3688 1242.91  3803.8 1240.12  4148.4 1228.94
  4588.5  1193.1  4751.5 1164.57  4757.9 1158.78  4780.2 1132.82  4794.5 1127.26
  4964.4 1125.98  5326.5 1139.37  5455.6 1153.71  5705.9 1166.48  6584.2  1200.2
  6833.7 1216.71  7060.7 1219.29    7216 1217.85  8182.9 1210.97  8899.9 1246.79
  9423.2 1237.41  9718.3 1240.36 10113.2 1266.37 10874.1 1281.56   10904 1282.73
#Mann= 17 ,-1 , 0
     834      .1       0  1115.5     .05       0  1287.1      .1       0
  1955.7     .16       0  2935.2      .1       0  3092.2      .1       0
    3688     .16       0  3803.8     .16       0  4148.4     .16       0
  4751.5     .05       0  5455.6     .16       0  5705.9      .1       0
  6584.2     .16       0  7060.7     .16       0    7216      .1       0
  9423.2     .16       0 10874.1      .1       0
Bank Sta=4757.9,5455.6
XS Rating Curve= 0 ,0
Exp/Cntr=0.3,0.1