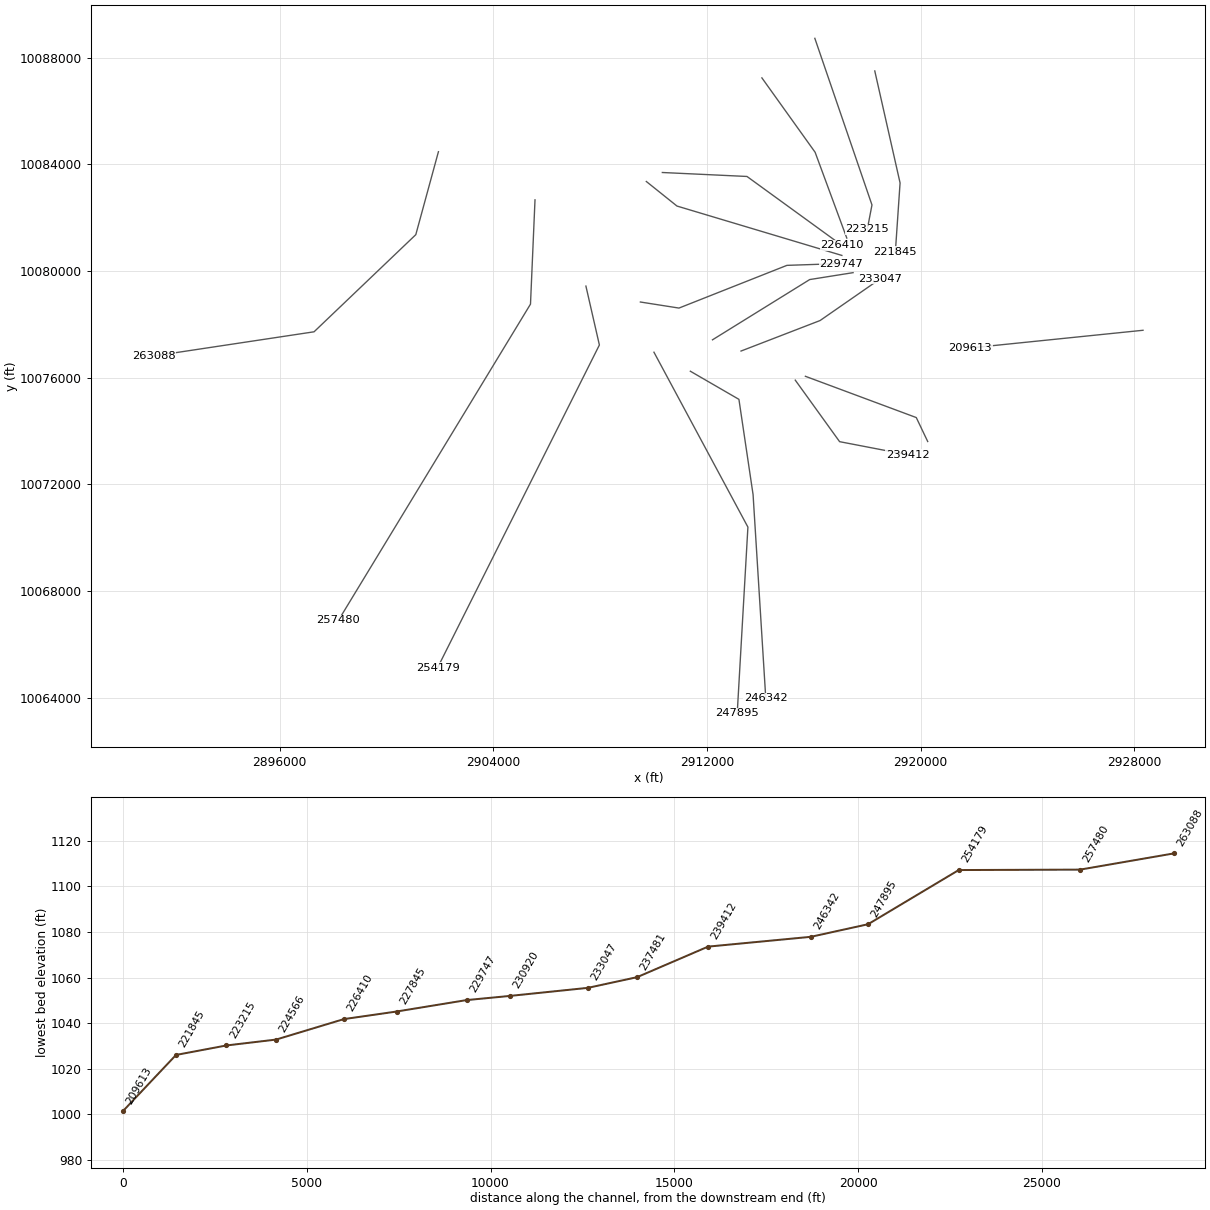
HEC-RAS study PEDERNALES RIVER.prj: PEDERNALES RIVER Base Level Engineering

--- PEDERNALES RIVER.g02 (geometry) --- (continued)

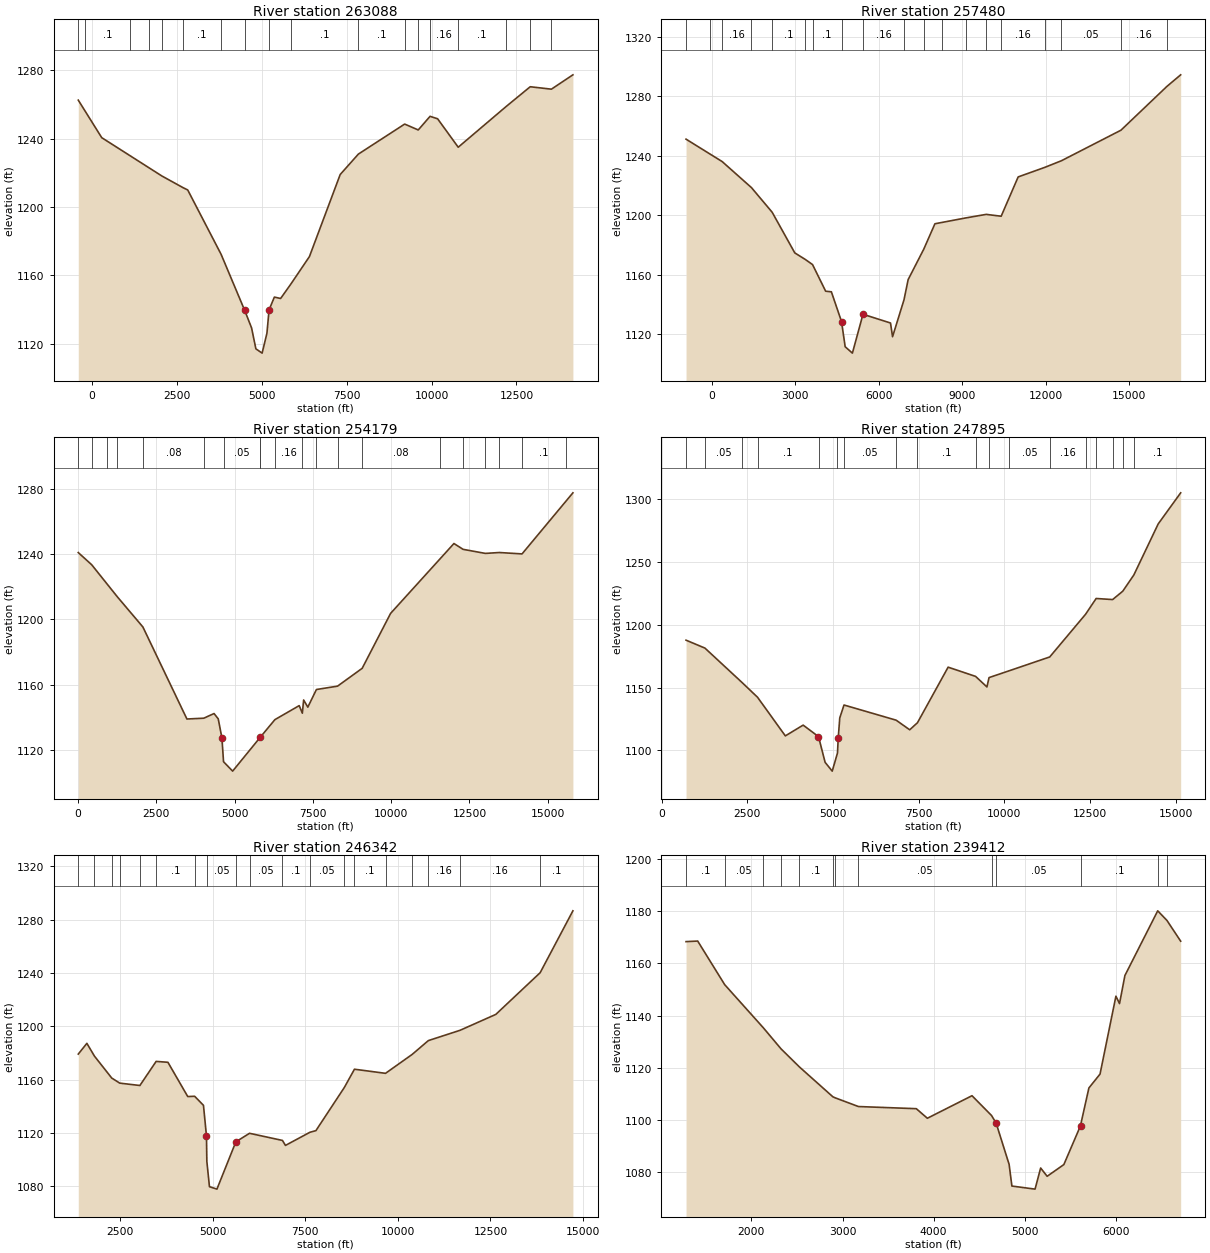
Type RM Length L Ch R = 1 ,263088  ,2551,2551,2551
BEGIN DESCRIPTION:
Mapping XS a36af871
END DESCRIPTION:
XS GIS Cut Line= 4
      2901946.32     10084470.57      2901098.96     10081361.19
      2897289.25     10077720.73      2891284.54     10076813.91
#Sta/Elev= 30
  -402.8 1262.47  -218.8 1256.62   287.9 1240.52  1121.8 1229.97  1685.2 1222.84
    2060  1218.1  2668.7 1211.43    2820 1209.94  3802.4 1172.33 4494.32 1139.65
    4700 1129.28  4827.1 1117.02  5010.8 1114.51  5152.6 1126.15  5216.1 1139.88
  5371.8 1147.27  5555.8 1146.48    5865 1155.13  6404.4 1170.99  7309.8 1218.97
  7845.8 1230.92  9207.9 1248.46  9608.1 1245.03  9956.2    1253 10178.7 1251.56
 10785.3 1234.93 12186.1 1258.57   12905  1270.3 13529.4 1268.88 14162.2 1277.27
#Mann= 18 ,-1 , 0
  -402.8     .16       0  -218.8      .1       0  1121.8     .05       0
  1685.2     .05       0    2060      .1       0  2668.7      .1       0
  3802.4     .16       0 4494.32     .05       0  5216.1     .16       0
    5865      .1       0  7845.8      .1       0  9207.9     .05       0
  9608.1      .1       0  9956.2     .16       0 10785.3      .1       0
 12186.1      .1       0   12905      .1       0 13529.4      .1       0
Bank Sta=4494.32,5216.1
XS Rating Curve= 0 ,0
Exp/Cntr=0.3,0.1

Type RM Length L Ch R = 1 ,257480  ,3301,3301,3301
BEGIN DESCRIPTION:
Mapping XS 02f041a1
END DESCRIPTION:
XS GIS Cut Line= 3
      2905562.24     10082665.92      2905393.09     10078757.46
       2898203.7     10066908.27
#Sta/Elev= 30
    -923 1251.28   -48.5 1241.12   374.7 1236.21  1428.1 1218.68  2171.1 1202.14
  2984.2  1174.8  3366.6 1170.33  3621.9 1166.95    4093 1149.04  4298.5 1148.64
  4662.9 1128.65  4794.7 1111.68  5054.3  1107.4  5434.5 1133.53  6423.2 1127.66
  6496.8 1118.42  6909.1 1143.34  7057.1 1156.85  7617.6 1177.29  8018.6 1194.38
  8272.2 1195.28  9123.1  1198.3  9861.2  1200.7 10399.2 1199.45 11009.8 1225.89
 11962.4 1232.28 12565.5 1236.78 14702.8  1257.3 16356.1 1286.79 16848.8 1294.54
#Mann= 19 ,-1 , 0
    -923     .16       0   -48.5      .1       0   374.7     .16       0
  1428.1     .16       0  2171.1      .1       0  3366.6     .16       0
  3621.9      .1       0  4662.9     .05       0  5434.5     .16       0
  6909.1      .1       0  7617.6     .16       0  8272.2     .16       0
  9123.1      .1       0  9861.2      .1       0 10399.2     .16       0
 11962.4     .16       0 12565.5     .05       0 14702.8     .16       0
 16356.1     .16       0
Bank Sta=4662.9,5434.5
XS Rating Curve= 0 ,0
Exp/Cntr=0.3,0.1

Type RM Length L Ch R = 1 ,254179  ,2466,2466,2466
BEGIN DESCRIPTION:
Mapping XS a5f67f4f
END DESCRIPTION:
XS GIS Cut Line= 3
      2907468.19     10079433.95      2907972.68     10077226.52
      2901914.03     10065129.34
#Sta/Elev= 30
    10.5 1240.95   439.6 1233.49   927.4  1221.8  1258.6 1213.87    2074 1195.42
  3479.6  1139.1  4018.3  1139.6  4345.6 1142.45  4479.7 1139.21  4597.1 1127.52
    4649 1112.96  4939.5 1107.21  5821.9 1127.95  6288.4 1138.71  7064.7 1147.29
  7165.1 1142.66  7206.4 1150.75  7340.5 1146.36  7614.7 1157.15    8289 1159.21
  9075.8 1170.12  9983.8 1203.75 11548.4 1236.82 12005.9 1246.49 12297.7 1242.93
 13009.5 1240.44 13452.4 1240.98 14180.2 1240.13 15579.7 1272.34 15804.4 1277.51
#Mann= 20 ,-1 , 0
    10.5      .1       0   439.6     .05       0   927.4     .16       0
  1258.6      .1       0    2074     .08       0  4018.3     .08       0
    4649     .05       0  5821.9     .05       0  5821.9     .16       0
  6288.4     .16       0  7165.1     .05       0  7614.7     .05       0
    8289     .08       0  9075.8     .08       0 11548.4      .1       0
 12297.7     .16       0 13009.5     .16       0 13452.4     .05       0
 14180.2      .1       0 15579.7     .16       0
Bank Sta=4597.1,5821.9
XS Rating Curve= 0 ,0
Exp/Cntr=0.3,0.1

Type RM Length L Ch R = 1 ,247895  ,1553,1553,1553
BEGIN DESCRIPTION:
Mapping XS 123fdf3d
END DESCRIPTION:
XS GIS Cut Line= 3
      2910015.82     10076955.53      2913533.76     10070401.22
      2913133.41     10063419.73
#Sta/Elev= 30
   714.7  1187.7  1265.6  1181.4  2345.7 1154.08  2801.2 1142.24  3611.6  1111.5
  4131.2 1120.07  4578.3 1110.94  4580.2 1110.91  4771.9 1090.45  4979.5 1083.44
  5133.2 1097.85  5155.1 1109.78  5199.7 1125.79  5323.4 1136.08  6845.2    1124
  7240.3 1116.35  7466.6 1121.97  8361.3 1166.21  9161.9 1158.88  9493.1 1150.48
  9554.9 1157.91 10147.3 1163.38 11325.7 1174.34 12370.6  1208.3 12679.9 1220.89
 13160.8 1220.03   13457 1226.71 13781.1 1239.68 14491.3  1280.3 15146.4 1305.02
#Mann= 18 ,-1 , 0
   714.7     .05       0  1265.6     .05       0  2345.7      .1       0
  2801.2      .1       0  4580.2     .05       0  5133.2     .16       0
  5323.4     .05       0  6845.2     .05       0  7466.6      .1       0
  9161.9     .16       0  9554.9      .1       0 10147.3     .05       0
 11325.7     .16       0 12370.6     .16       0 12679.9      .1       0
 13160.8     .16       0   13457      .1       0 13781.1      .1       0
Bank Sta=4578.3,5155.1
XS Rating Curve= 0 ,0
Exp/Cntr=0.3,0.1

Type RM Length L Ch R = 1 ,246342  ,2798,2798,2798
BEGIN DESCRIPTION:
Mapping XS c0ef7d5f
END DESCRIPTION:
XS GIS Cut Line= 4
      2911378.73     10076243.07      2913197.28     10075188.92
      2913727.17     10071618.91      2914202.62     10063987.11
#Sta/Elev= 30
  1369.1 1179.16  1601.4 1187.21  1806.1 1177.63  2273.5 1161.17  2490.1 1157.38
  3033.3 1155.61  3471.9 1173.67  3790.2 1173.01  4325.5 1147.32  4511.8 1147.53
  4750.1 1140.74    4831 1117.78  4841.1 1098.79  4911.9 1079.76  5113.8 1077.93
  5624.6 1113.37  5993.8 1119.78    6883 1114.43  6964.1  1110.7  7624.1 1120.53
  7786.8 1121.78  8555.1 1154.17  8827.5 1167.81  9666.4 1164.73 10386.6 1178.92
 10822.9 1189.26 11679.7 1196.99 12645.4 1208.91 13841.7 1240.14 14726.8 1286.54
#Mann= 19 ,-1 , 0
  1369.1      .1       0  1806.1     .05       0  2273.5      .1       0
  2490.1     .05       0  3033.3      .1       0  3471.9      .1       0
  4511.8     .16       0  4841.1     .05       0  5624.6      .1       0
  5993.8     .05       0    6883      .1       0  7624.1     .05       0
  8555.1     .16       0  8827.5      .1       0  9666.4      .1       0
 10386.6      .1       0 10822.9     .16       0 11679.7     .16       0
 13841.7      .1       0
Bank Sta=4831,5624.6
XS Rating Curve= 0 ,0
Exp/Cntr=0.3,0.1

Type RM Length L Ch R = 1 ,239412  ,1931,1931,1931
BEGIN DESCRIPTION:
Mapping XS c23ee2bb
END DESCRIPTION:
XS GIS Cut Line= 3
      2915306.55     10075909.28      2916966.84     10073603.15
      2919507.66     10073113.46
#Sta/Elev= 30
  1282.5 1168.29  1410.3 1168.51    1707 1151.82  2131.1 1135.32  2324.7 1127.29
  2526.5 1120.37  2893.3 1108.96  2920.1 1108.53  3174.7 1105.21  3809.7 1104.39
  3931.2 1100.73  4421.1 1109.35  4635.9 1101.77  4685.9 1098.88  4828.5  1083.1
    4859  1074.8  5113.4 1073.62  5174.7  1081.7    5246 1078.53  5429.3 1083.01
  5612.6 1097.89  5622.4 1099.54  5704.3 1112.32  5826.5 1117.62  6000.8 1147.41
  6040.4  1144.6  6099.5 1155.32  6459.7 1180.07    6561 1176.39  6711.7 1168.46
#Mann= 13 ,-1 , 0
  1282.5      .1       0    1707     .05       0  2131.1      .1       0
  2324.7     .05       0  2526.5      .1       0  2893.3     .05       0
  2920.1      .1       0  3174.7     .05       0  4635.9      .1       0
  4685.9     .05       0  5622.4      .1       0  6459.7     .05       0
    6561      .1       0
Bank Sta=4685.9,5612.6
XS Rating Curve= 0 ,0
Exp/Cntr=0.3,0.1

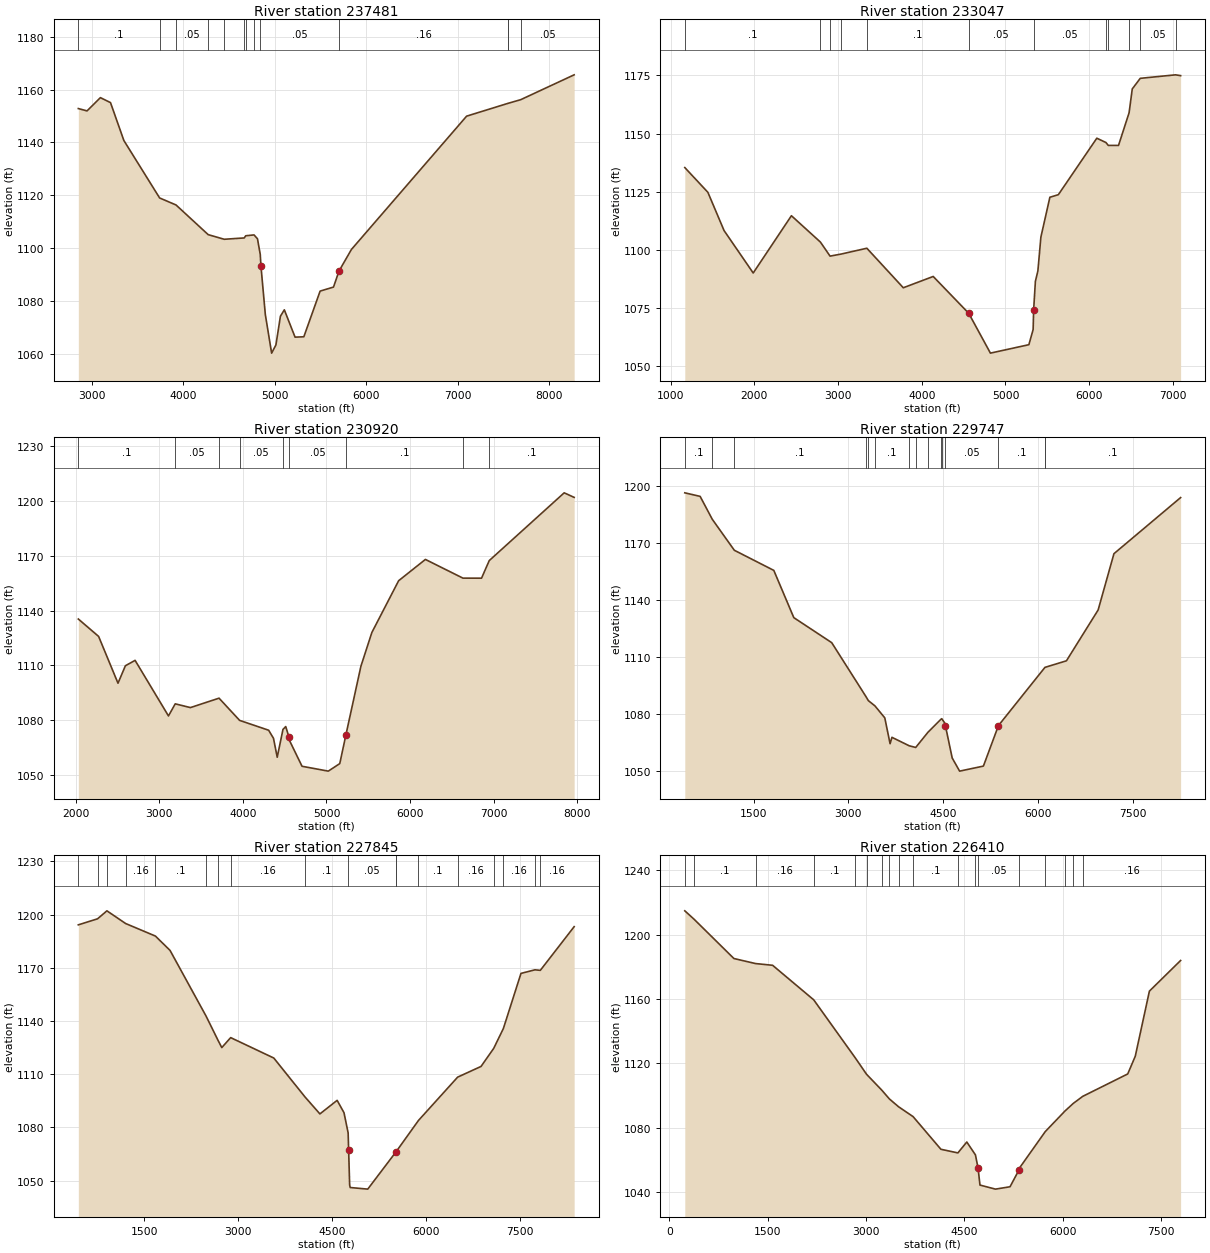
Type RM Length L Ch R = 1 ,237481  ,1337,1337,1337
BEGIN DESCRIPTION:
Mapping XS cc62e269
END DESCRIPTION:
XS GIS Cut Line= 3
      2915686.76     10076052.81       2919837.8     10074506.45
      2920265.51     10073608.86
#Sta/Elev= 30
  2850.6 1152.82  2945.7 1151.93    3092 1156.95  3202.6 1155.07  3348.9 1140.71
  3739.9 1118.97  3919.5 1116.31  4271.1 1105.08  4446.3 1103.33  4665.7 1103.83
  4681.5 1104.65  4772.7 1104.98  4810.4  1103.5  4840.7 1097.58    4848 1093.34
  4896.1 1074.87  4965.1 1060.22    5012 1063.31  5061.4 1074.19  5104.1 1076.62
  5221.5 1066.27  5317.5 1066.41  5495.6  1083.7    5642 1085.23  5702.6 1091.32
  5838.3 1099.48  7098.1 1149.94  7550.9 1154.79    7690 1156.18  8274.6 1165.59
#Mann= 13 ,-1 , 0
  2850.6      .1       0  3739.9     .05       0  3919.5     .05       0
  4271.1      .1       0  4446.3     .05       0  4665.7     .16       0
  4681.5      .1       0  4772.7     .16       0  4840.7     .05       0
  5702.6     .16       0  7550.9     .05       0  7550.9     .16       0
    7690     .05       0
Bank Sta=4848,5702.6
XS Rating Curve= 0 ,0
Exp/Cntr=0.3,0.1

Type RM Length L Ch R = 1 ,233047  ,2127,2127,2127
BEGIN DESCRIPTION:
Mapping XS 1c776ee1
END DESCRIPTION:
XS GIS Cut Line= 3
       2913276.2     10076999.55      2916235.35     10078142.64
      2918494.15     10079710.73
#Sta/Elev= 30
  1169.8 1135.37  1445.3 1124.73  1638.9 1108.26    1987 1090.01  2443.3 1114.65
  2789.4 1103.32  2904.9 1097.27  3037.5 1098.16  3344.2 1100.66  3779.4 1083.66
  4136.7 1088.52    4561 1072.68  4820.1 1055.54  5279.6 1059.17  5330.3  1065.7
  5336.4 1074.22  5357.3 1086.44    5387 1090.91  5422.8 1105.44  5530.2 1122.59
  5631.5  1123.7  6090.8 1147.99    6200 1146.14  6228.1 1144.89  6350.1 1144.89
  6476.4 1158.95  6514.2 1169.19  6609.6 1173.75  7031.5 1175.26  7091.8 1174.91
#Mann= 12 ,-1 , 0
  1169.8      .1       0  2789.4     .05       0  2904.9      .1       0
  3037.5     .16       0  3344.2      .1       0    4561     .05       0
  5336.4     .05       0    6200      .1       0  6228.1     .05       0
  6476.4      .1       0  6609.6     .05       0  7031.5      .1       0
Bank Sta=4561,5336.4
XS Rating Curve= 0 ,0
Exp/Cntr=0.3,0.1

Type RM Length L Ch R = 1 ,230920  ,1173,1173,1173
BEGIN DESCRIPTION:
Mapping XS 7631730a
END DESCRIPTION:
XS GIS Cut Line= 3
      2912207.63     10077420.49      2915847.58     10079678.72
      2917472.07     10079937.36
#Sta/Elev= 30
  2033.1 1135.37  2275.8 1125.83  2507.3 1100.19  2595.9 1109.75  2711.7 1112.71
  3110.9 1082.25  3191.7 1088.88  3373.2 1086.82  3715.6 1091.98  3961.7  1079.8
  4308.6 1074.41  4366.5 1069.98  4411.3 1059.61    4480 1074.85    4513 1076.41
  4549.6 1070.94  4555.5 1069.02  4707.8 1054.65  5021.8 1051.99  5159.1 1056.12
  5232.3 1071.81  5411.8 1109.48  5542.9    1128    5863 1156.37  6183.1 1168.04
  6631.6 1157.79  6854.2 1157.76  6946.4  1167.4  7842.3 1204.55  7961.6 1202.05
#Mann= 9 ,-1 , 0
  2033.1      .1       0  3191.7     .05       0  3715.6      .1       0
  3961.7     .05       0    4480     .16       0  4555.5     .05       0
  5232.3      .1       0  6631.6     .05       0  6946.4      .1       0
Bank Sta=4549.6,5232.3
XS Rating Curve= 0 ,0
Exp/Cntr=0.3,0.1

Type RM Length L Ch R = 1 ,229747  ,1902,1902,1902
BEGIN DESCRIPTION:
Mapping XS e6b95da8
END DESCRIPTION:
XS GIS Cut Line= 4
      2909507.91      10078837.1      2910952.38     10078609.97
      2914994.68     10080210.81      2917033.67     10080279.21
#Sta/Elev= 30
   411.7 1196.17   654.4 1194.31   846.6  1182.3  1195.9 1166.04  1820.9 1155.48
  2137.7 1130.69  2737.6 1117.57  3283.1 1089.11  3317.9 1087.16  3422.3 1084.39
    3578 1078.12  3661.8 1064.56  3691.5  1067.9  3965.2 1063.46  4067.6 1062.59
  4261.5 1070.56  4464.4  1077.3    4480 1077.67  4526.3 1075.47  4537.3 1074.09
  4645.4 1057.05  4762.7 1050.17  5139.4 1052.81  5377.8 1074.08  6112.6 1104.55
  6114.8 1104.61  6454.3 1108.05  6955.9 1134.72    7206 1164.23  8261.8 1193.68
#Mann= 15 ,-1 , 0
   411.7      .1       0   846.6     .05       0  1195.9      .1       0
  3283.1     .05       0  3317.9     .16       0  3422.3      .1       0
  3965.2     .05       0  4067.6      .1       0  4261.5     .05       0
  4464.4      .1       0    4480     .05       0  4526.3     .05       0
  5377.8      .1       0  6112.6     .05       0  6114.8      .1       0
Bank Sta=4537.3,5377.8
XS Rating Curve= 0 ,0
Exp/Cntr=0.3,0.1

Type RM Length L Ch R = 1 ,227845  ,1435,1435,1435
BEGIN DESCRIPTION:
Mapping XS ffaed9bf
END DESCRIPTION:
XS GIS Cut Line= 3
      2909730.33     10083353.82      2910877.68     10082433.77
      2917051.75     10080583.28
#Sta/Elev= 30
   444.9 1194.25   752.1 1197.66   901.4 1202.16    1200    1195  1675.5 1187.92
  1908.9 1179.85  2485.8 1142.68  2676.4 1129.03  2735.1 1125.01  2877.2 1130.63
  3565.4 1119.12  4064.2 1097.15  4301.7 1087.59  4576.8 1095.24  4686.4 1088.28
  4752.6 1076.88 4760.42 1067.18  4776.8 1047.45  4785.7 1046.07  5065.7 1045.16
  5520.7 1066.37  5875.1 1083.88  6500.5 1108.33  6874.5 1114.38  7076.6 1124.56
  7230.9 1135.77    7512 1166.86  7735.7 1168.88  7820.8 1168.58    8361 1193.22
#Mann= 19 ,-1 , 0
   444.9      .1       0   752.1     .05       0   901.4      .1       0
    1200     .16       0  1675.5      .1       0  2485.8     .05       0
  2676.4      .1       0  2877.2     .16       0  4064.2      .1       0
  4752.6     .05       0  5520.7     .05       0  5520.7      .1       0
  5520.7     .16       0  5875.1      .1       0  6500.5     .16       0
  7076.6      .1       0  7230.9     .16       0  7735.7      .1       0
  7820.8     .16       0
Bank Sta=4760.42,5520.7
XS Rating Curve= 0 ,0
Exp/Cntr=0.3,0.1

Type RM Length L Ch R = 1 ,226410  ,1844,1844,1844
BEGIN DESCRIPTION:
Mapping XS 5c696f8a
END DESCRIPTION:
XS GIS Cut Line= 3
      2910330.36     10083691.03      2913498.94     10083542.37
      2917051.49     10080960.88
#Sta/Elev= 30
   233.7 1214.73   372.5 1209.62   982.6  1185.1  1312.9 1181.97  1573.3 1180.89
  2200.1 1159.44  2832.5 1123.48  3006.5 1113.18  3239.6 1103.28  3353.8 1097.89
  3494.3 1093.01  3716.2 1086.88  4140.7 1066.58  4399.5 1064.33  4535.5  1071.1
  4667.4 1063.09  4707.1 1054.99  4736.4 1044.35  4972.7 1041.83  5194.8  1043.3
  5330.8 1053.67    5337 1054.83    5732 1077.55    6036 1090.48  6161.9 1095.15
    6305 1099.49  6990.2 1113.38  7105.4 1124.38    7321 1164.84  7797.2 1183.88
#Mann= 18 ,-1 , 0
   233.7     .16       0   372.5      .1       0  1312.9     .16       0
  2200.1      .1       0  2832.5     .05       0  3006.5      .1       0
  3239.6     .05       0  3353.8      .1       0  3494.3     .05       0
  3716.2      .1       0  4399.5     .16       0  4667.4      .1       0
  4707.1     .05       0    5337     .16       0    5732      .1       0
    6036     .16       0  6161.9      .1       0    6305     .16       0
Bank Sta=4707.1,5330.8
XS Rating Curve= 0 ,0
Exp/Cntr=0.3,0.1

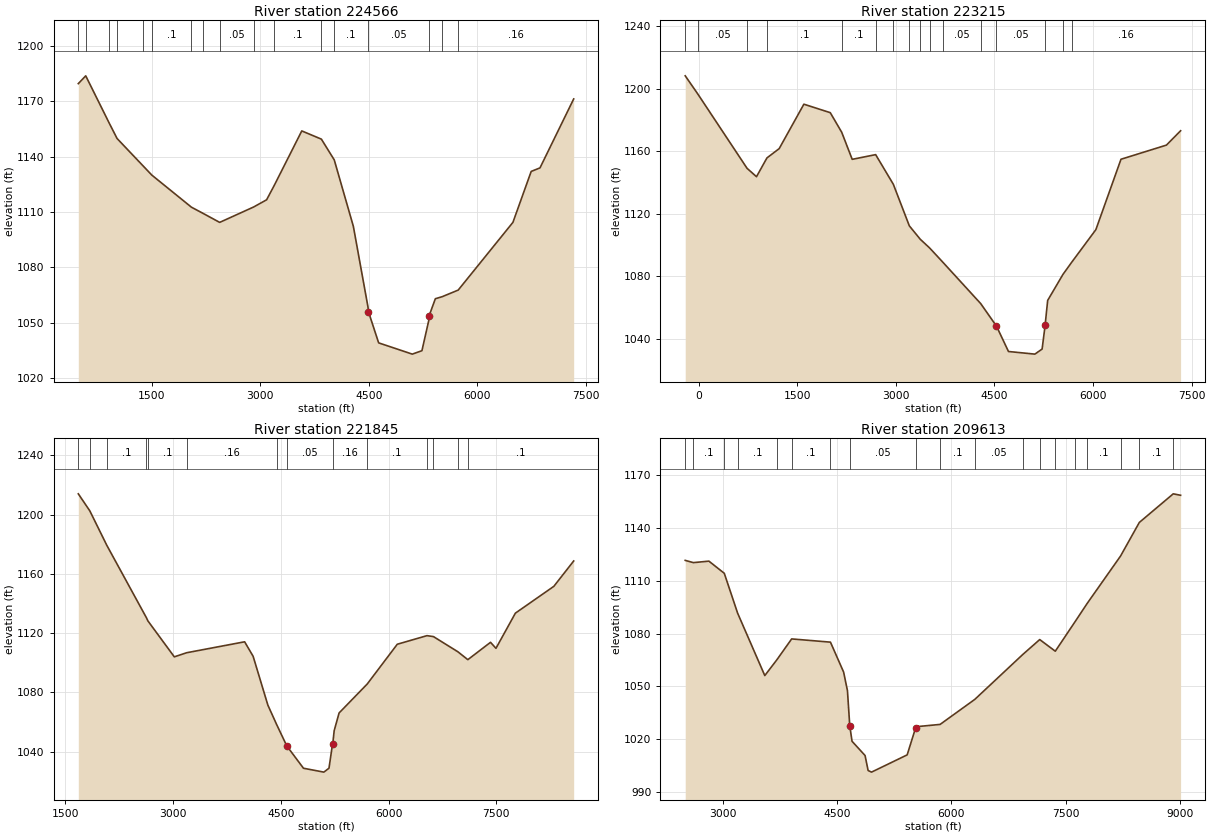
Type RM Length L Ch R = 1 ,224566  ,1351,1351,1351
BEGIN DESCRIPTION:
Mapping XS da71cbba
END DESCRIPTION:
XS GIS Cut Line= 3
      2914057.84     10087236.76      2916050.38     10084448.67
      2917235.64     10081234.01
#Sta/Elev= 30
   482.2 1179.64   584.9 1183.88   912.8 1157.98  1018.9 1149.85    1382 1134.85
  1498.6 1130.03  2047.2 1112.59  2203.2 1109.34  2437.8 1104.34    2907 1112.68
  3087.2  1116.6  3190.3 1124.21  3573.8 1153.98  3845.1 1149.52  4023.2 1138.24
  4287.4 1102.19  4489.9  1058.4  4495.7 1055.93  4637.2 1038.96  5102.7 1032.85
    5236 1034.71  5330.5 1051.09  5335.8 1053.69  5421.8 1062.92  5515.4 1064.01
  5737.7  1067.6  6494.8 1104.35  6747.5    1132  6869.2 1133.92  7335.3 1171.32
#Mann= 17 ,-1 , 0
   482.2      .1       0   584.9     .16       0   912.8     .05       0
  1018.9      .1       0    1382     .16       0  1498.6      .1       0
  2047.2      .1       0  2203.2     .16       0  2437.8     .05       0
    2907     .16       0  3190.3      .1       0  3845.1     .16       0
  4023.2      .1       0  4489.9     .05       0  5330.5     .16       0
  5515.4      .1       0  5737.7     .16       0
Bank Sta=4495.7,5335.8
XS Rating Curve= 0 ,0
Exp/Cntr=0.3,0.1

Type RM Length L Ch R = 1 ,223215  ,1370,1370,1370
BEGIN DESCRIPTION:
Mapping XS 223380d4
END DESCRIPTION:
XS GIS Cut Line= 3
      2916039.69     10088719.39      2918178.79     10082474.73
      2918002.84     10081557.32
#Sta/Elev= 30
  -202.3 1208.22   -14.8 1196.84   738.5 1149.07   881.9 1143.72  1040.4 1155.71
  1227.1 1161.68  1602.5 1190.08  2003.9 1184.66  2177.9 1172.15  2337.5 1154.82
  2694.3 1157.83  2963.3 1138.86  3206.5 1112.29  3372.4 1103.74  3514.5 1098.19
  3713.5 1089.17  4292.6 1062.56  4532.3 1048.17  4714.7 1031.95  5115.9 1030.27
  5226.3 1033.51  5267.3 1047.04  5272.6 1049.06  5310.9 1064.61  5543.4 1081.25
  5678.7 1089.15  6044.1 1109.87  6425.9 1154.87  7117.2 1163.92  7332.7 1173.09
#Mann= 16 ,-1 , 0
  -202.3     .05       0   -14.8     .05       0   738.5      .1       0
  1040.4      .1       0  2177.9      .1       0  2694.3     .16       0
  2963.3      .1       0  3206.5      .1       0  3372.4     .05       0
  3514.5      .1       0  3713.5     .05       0  4292.6     .05       0
  4532.3     .05       0  5267.3     .05       0  5543.4      .1       0
  5678.7     .16       0
Bank Sta=4532.3,5272.6
XS Rating Curve= 0 ,0
Exp/Cntr=0.3,0.1

Type RM Length L Ch R = 1 ,221845  ,1447,1447,1447
BEGIN DESCRIPTION:
Mapping XS c9dd96ed
END DESCRIPTION:
XS GIS Cut Line= 3
      2918283.86     10087496.93      2919231.19     10083300.16
      2919054.57     10080714.64
#Sta/Elev= 30
  1683.1 1214.09  1843.4 1202.58  2078.3 1179.46  2631.2 1130.37  2651.7 1128.26
  3019.1 1103.98  3190.1 1106.74  3997.8 1114.14    4116 1104.35    4321  1071.4
  4442.6 1058.32  4585.2 1043.75  4816.6 1028.74  5099.9 1026.11  5171.9 1028.77
  5220.9 1045.06  5226.9 1046.36  5243.7 1054.05  5312.4 1066.07    5704 1085.64
  6122.2 1112.49  6535.3 1118.29  6625.3 1117.66  6964.4 1107.44  7104.1 1102.07
  7419.8  1113.8  7495.4 1109.73    7766  1133.5    8301  1151.6    8577 1168.72
#Mann= 14 ,-1 , 0
  1683.1      .1       0  1843.4     .16       0  2078.3      .1       0
  2631.2     .16       0  2651.7      .1       0  3190.1     .16       0
  4442.6      .1       0  4585.2     .05       0  5226.9     .16       0
    5704      .1       0  6535.3     .05       0  6625.3      .1       0
  6964.4     .05       0  7104.1      .1       0
Bank Sta=4585.2,5220.9
XS Rating Curve= 0 ,0
Exp/Cntr=0.3,0.1

Type RM Length L Ch R = 1 ,209613  ,1569,1569,1569
BEGIN DESCRIPTION:
Mapping XS c5e8d5e5
END DESCRIPTION:
XS GIS Cut Line= 2
      2928327.79     10077777.99      2921856.64     10077115.21
#Sta/Elev= 30
  2503.5 1121.47  2610.5 1120.19  2814.4 1121.04  3016.3 1114.15  3192.2 1091.49
  3548.3 1056.16  3706.8  1065.1  3901.1 1076.94  4410.7 1075.11  4583.6 1058.13
  4633.9 1047.58  4664.1 1027.65  4694.2  1018.9  4865.1 1010.84  4905.3 1002.32
    4950 1001.42    5418  1011.2  5528.6 1026.49  5536.2 1027.17  5850.4 1028.47
  6306.2 1042.66  6936.8 1068.14  7158.7 1076.57  7363.1 1069.98  7628.1 1087.05
  7781.8 1097.06  8220.7 1123.97  8466.5 1142.97    8912  1159.2  9008.5 1158.38
#Mann= 19 ,-1 , 0
  2503.5      .1       0  2610.5      .1       0  3016.3     .16       0
  3192.2      .1       0  3706.8     .05       0  3901.1      .1       0
  4410.7     .16       0  4664.1     .05       0  5536.2      .1       0
  5850.4      .1       0  6306.2     .05       0  6936.8      .1       0
  7158.7     .16       0  7363.1      .1       0  7628.1     .05       0
  7781.8      .1       0  8220.7     .05       0  8466.5      .1       0
    8912      .1       0
Bank Sta=4664.1,5528.6
XS Rating Curve= 0 ,0
Exp/Cntr=0.3,0.1