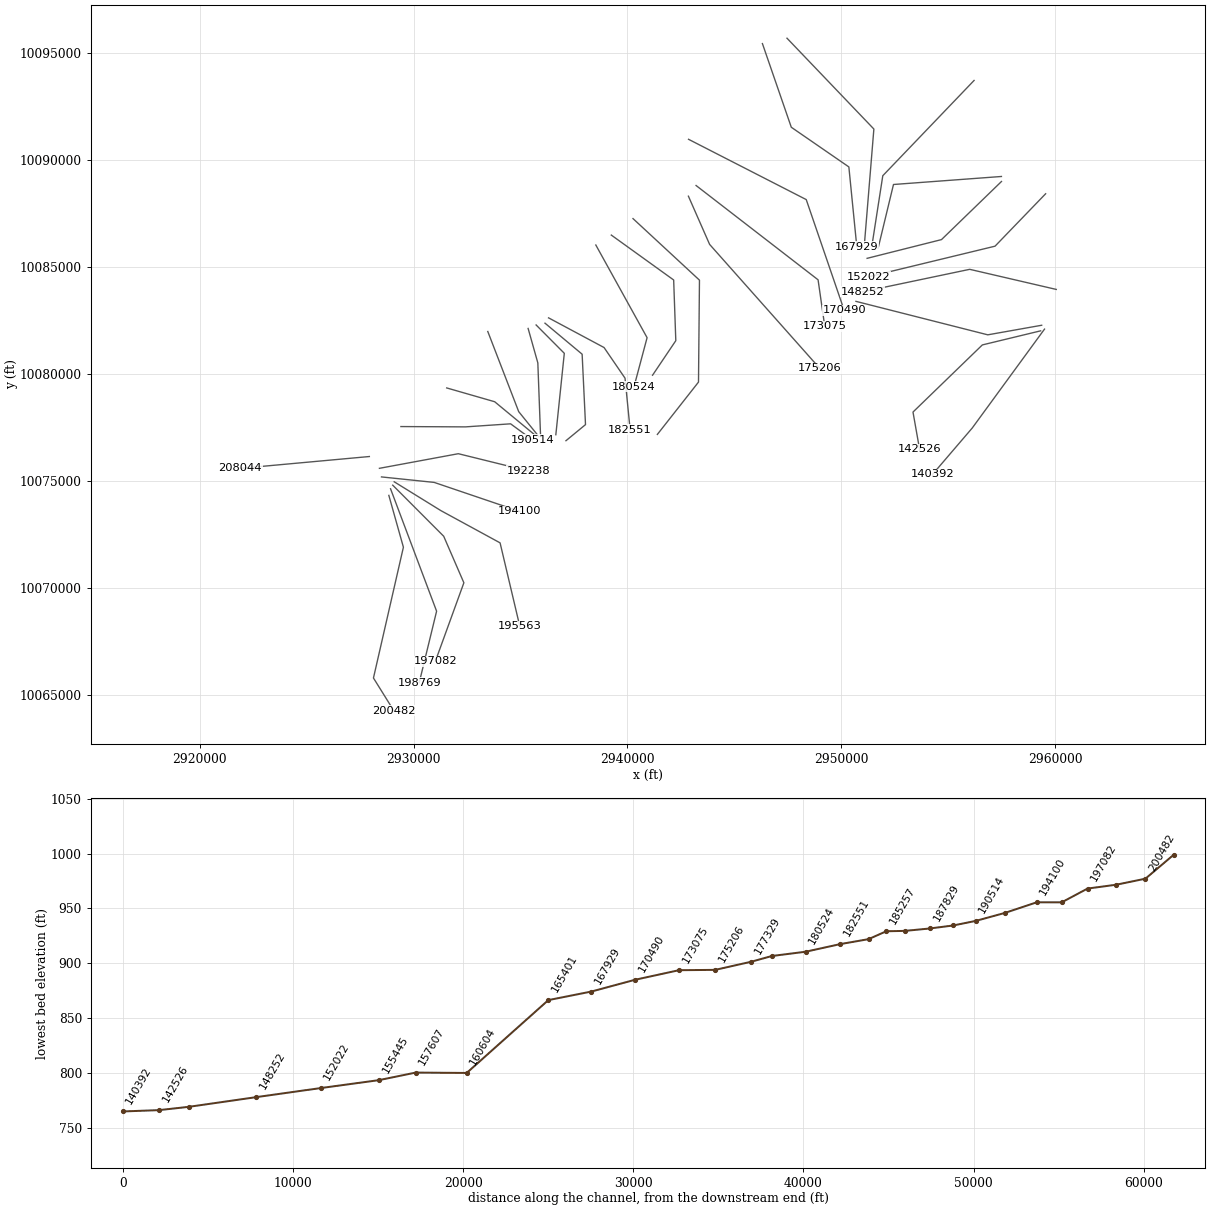
HEC-RAS study PEDERNALES RIVER.prj: PEDERNALES RIVER Base Level Engineering

--- PEDERNALES RIVER.g02 (geometry) --- (continued)

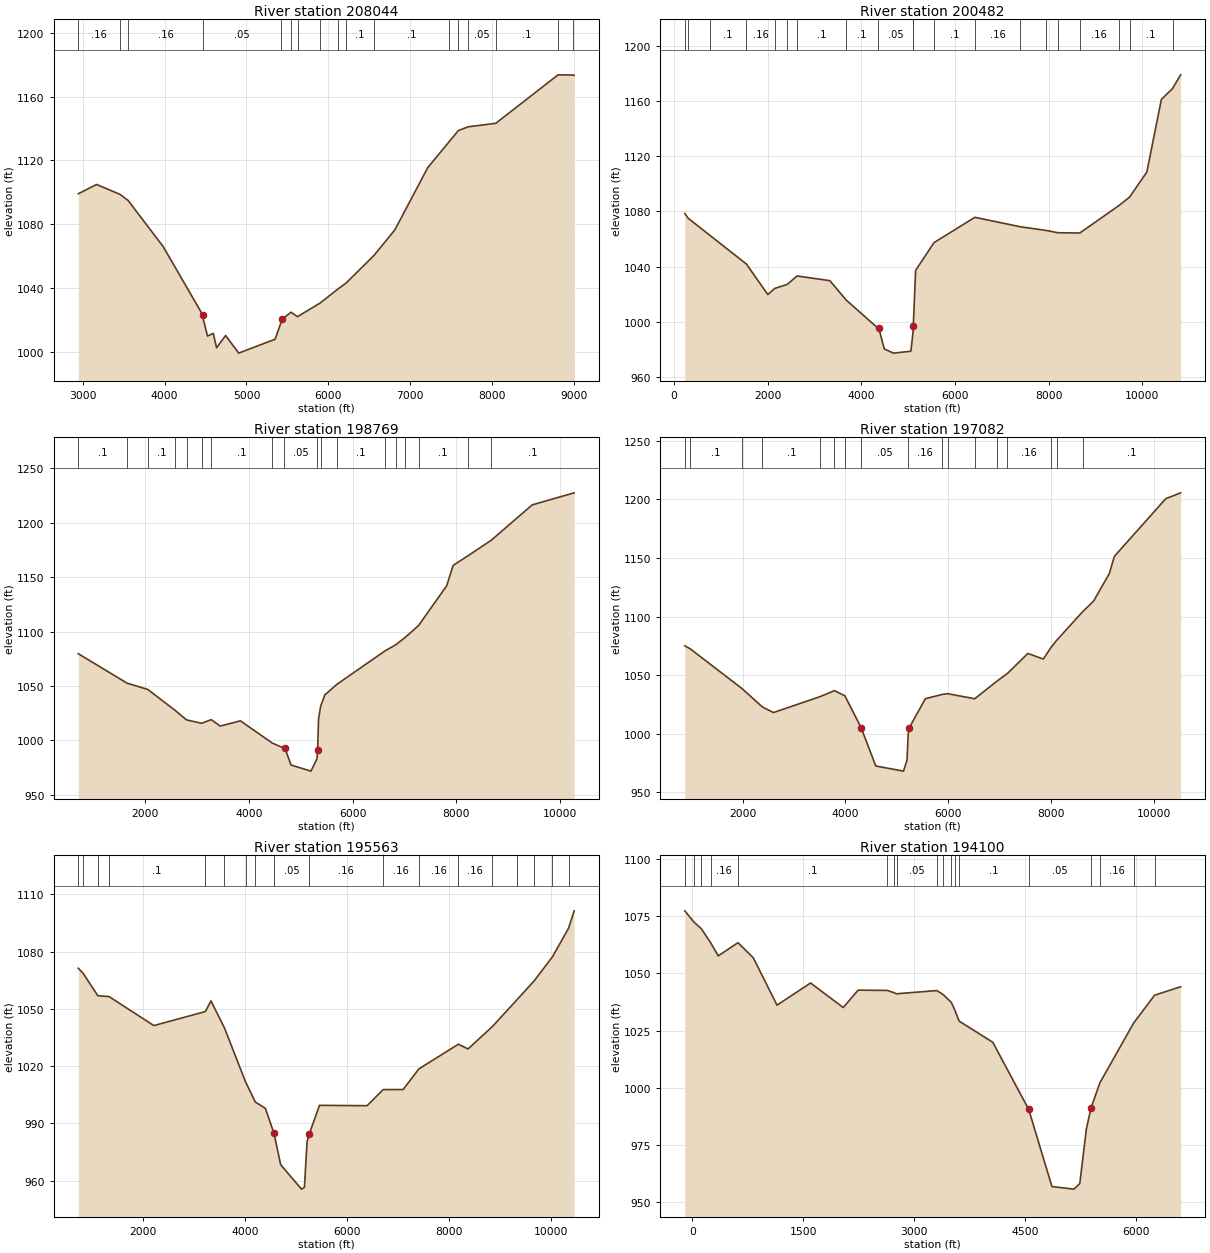
Type RM Length L Ch R = 1 ,208044  ,1673,1673,1673
BEGIN DESCRIPTION:
Mapping XS f7433aed
END DESCRIPTION:
XS GIS Cut Line= 2
      2927931.13     10076148.07      2921896.13     10075594.82
#Sta/Elev= 30
  2944.8 1099.09  3168.4  1104.9  3454.6 1098.68  3553.3 1094.88  3981.8 1065.95
  4463.8 1023.27    4470 1020.76  4524.1 1009.84  4594.3 1011.57  4634.5 1002.52
    4745 1010.21  4904.7  999.16    5350 1007.89  5427.8 1019.14  5437.9 1020.49
  5544.6 1024.81  5623.9 1022.03  5899.9 1030.55  6119.6 1039.42  6218.3 1043.13
  6557.9 1060.37  6813.6 1076.44  7215.3 1115.42  7480.1 1131.92  7589.1 1138.64
  7706.9 1141.02  8047.4 1143.25  8808.5 1173.63  8992.8 1173.49  9005.1 1173.34
#Mann= 17 ,-1 , 0
  2944.8     .16       0  3454.6      .1       0  3553.3     .16       0
    4470     .05       0  5427.8     .05       0  5544.6      .1       0
  5623.9     .05       0  5899.9     .16       0  6119.6     .05       0
  6218.3      .1       0  6557.9      .1       0  7480.1     .05       0
  7589.1      .1       0  7706.9     .05       0  8047.4      .1       0
  8808.5     .05       0  8992.8      .1       0
Bank Sta=4463.8,5437.9
XS Rating Curve= 0 ,0
Exp/Cntr=0.3,0.1

Type RM Length L Ch R = 1 ,200482  ,1713,1713,1713
BEGIN DESCRIPTION:
Mapping XS cfa8be4a
END DESCRIPTION:
XS GIS Cut Line= 4
      2928842.39     10074330.25      2929523.22     10071907.94
      2928122.56      10065792.4      2929073.99     10064264.11
#Sta/Elev= 30
   230.3 1078.51   304.3 1075.04   766.2 1062.66  1546.7 1041.84  2002.9  1019.7
  2152.4 1024.15  2419.2 1027.08  2628.8 1033.19    3329 1029.75  3675.2 1015.78
  4351.2  995.45  4371.7  995.62    4491   980.2  4689.5  977.18    5059  978.56
  5105.7   992.5  5110.3   996.9  5160.3 1037.19  5552.8 1057.37  6426.1 1075.76
  7392.1 1068.92  7954.5 1066.19  8199.9 1064.56  8667.7 1064.37  9495.3  1084.1
    9729 1090.37 10098.6 1108.54   10409 1161.28 10647.4  1169.2 10820.6 1179.16
#Mann= 20 ,-1 , 0
   230.3      .1       0   304.3      .1       0   766.2      .1       0
  1546.7     .16       0  2152.4      .1       0  2419.2     .16       0
  2628.8      .1       0  3675.2      .1       0  4351.2     .05       0
  5105.7      .1       0  5105.7     .16       0  5552.8      .1       0
  6426.1     .16       0  7392.1      .1       0  7954.5      .1       0
  8199.9     .16       0  8667.7     .16       0  9495.3     .05       0
    9729      .1       0 10647.4      .1       0
Bank Sta=4371.7,5110.3
XS Rating Curve= 0 ,0
Exp/Cntr=0.3,0.1

Type RM Length L Ch R = 1 ,198769  ,1687,1687,1687
BEGIN DESCRIPTION:
Mapping XS 6c0cd8b1
END DESCRIPTION:
XS GIS Cut Line= 3
      2928921.95     10074640.19      2931075.64     10068916.48
      2930262.51     10065573.03
#Sta/Elev= 30
   713.6 1079.65    1655 1052.54  2051.1 1046.84  2578.3  1027.6  2798.4 1018.82
  3089.4 1015.68  3275.5 1019.03  3447.1  1013.1  3838.2 1017.93  4453.2  997.43
  4681.1  992.75  4691.5  993.36  4812.7  977.32  5197.1  971.68  5313.7  983.09
  5325.5  991.27    5344 1019.95    5384 1031.37  5464.9 1041.82  5697.3  1051.5
  6625.2 1082.28    6832 1087.89  7015.1 1094.73  7270.6 1105.55  7813.2 1142.13
  7938.4 1160.92  8217.7 1169.56  8672.9 1184.03  9461.7 1216.54   10270 1227.62
#Mann= 18 ,-1 , 0
   713.6      .1       0    1655     .16       0  2051.1      .1       0
  2578.3      .1       0  2798.4      .1       0  3089.4     .16       0
  3275.5      .1       0  4453.2      .1       0  4681.1     .05       0
  5313.7      .1       0    5384     .16       0  5697.3      .1       0
  6625.2     .16       0    6832      .1       0  7015.1     .16       0
  7270.6      .1       0  8217.7     .16       0  8672.9      .1       0
Bank Sta=4691.5,5325.5
XS Rating Curve= 0 ,0
Exp/Cntr=0.3,0.1

Type RM Length L Ch R = 1 ,197082  ,1519,1519,1519
BEGIN DESCRIPTION:
Mapping XS 52befbc8
END DESCRIPTION:
XS GIS Cut Line= 4
      2929024.06     10074808.13      2931407.61     10072420.69
      2932351.04     10070244.69      2931020.97     10066582.35
#Sta/Elev= 30
   875.3 1075.13   984.7 1072.41  1983.4 1038.78  2383.5 1022.97  2599.8 1018.13
    3508 1031.76  3784.4 1036.82  3988.3 1032.46  4303.2 1005.32  4589.7  972.53
  5128.2  968.17  5196.5  977.61    5220  999.77  5237.4 1004.97  5553.5 1029.99
    5882 1033.62  5987.3 1034.23  6513.5 1029.94  6942.7 1044.85  7150.1 1051.56
  7546.4 1068.58  7847.2 1063.79  8000.3 1073.97  8106.6 1079.78  8610.4 1104.16
  8823.9 1113.23    9130 1136.71  9228.2 1151.39 10228.3 1200.67   10517 1205.64
#Mann= 17 ,-1 , 0
   875.3     .16       0   984.7      .1       0  1983.4     .16       0
  2383.5      .1       0    3508     .16       0  3784.4      .1       0
  3988.3     .16       0  4303.2     .05       0    5220     .16       0
    5882      .1       0  5987.3      .1       0  6513.5      .1       0
  6942.7     .05       0  7150.1     .16       0  8000.3      .1       0
  8106.6     .16       0  8610.4      .1       0
Bank Sta=4303.2,5237.4
XS Rating Curve= 0 ,0
Exp/Cntr=0.3,0.1

Type RM Length L Ch R = 1 ,195563  ,1463,1463,1463
BEGIN DESCRIPTION:
Mapping XS 1cf03ccc
END DESCRIPTION:
XS GIS Cut Line= 4
      2929092.45     10074967.01      2931275.77     10073618.76
      2934044.39     10072111.05      2934967.04     10068207.19
#Sta/Elev= 30
   733.6 1071.26   827.7 1068.61  1117.4 1056.86    1336 1056.44  2215.3 1041.24
  3226.2 1048.58  3336.4 1054.14  3601.2 1040.05  4015.9 1011.72  4206.7  1001.2
  4404.7  997.89  4573.8  984.73  4704.8  968.37  5112.9  955.59  5170.1  956.53
  5222.4  980.51  5266.1  984.54  5466.2  999.47    6400  999.29  6715.6 1007.71
  7107.1 1007.74  7415.3 1018.53  8191.1 1031.49  8381.2    1029  8856.8 1040.69
    9341 1054.75  9676.8  1064.6   10038 1077.27 10353.4 1092.21 10463.6 1101.34
#Mann= 18 ,-1 , 0
   733.6     .16       0   827.7      .1       0  1117.4     .16       0
    1336      .1       0  3226.2     .16       0  3601.2     .16       0
  4015.9      .1       0  4206.7     .16       0  4573.8     .05       0
  5266.1     .16       0  6715.6     .16       0  7415.3     .16       0
  8191.1     .16       0  8856.8      .1       0    9341     .05       0
  9676.8     .05       0   10038     .16       0 10353.4      .1       0
Bank Sta=4573.8,5266.1
XS Rating Curve= 0 ,0
Exp/Cntr=0.3,0.1

Type RM Length L Ch R = 1 ,194100  ,1862,1862,1862
BEGIN DESCRIPTION:
Mapping XS aee10ab1
END DESCRIPTION:
XS GIS Cut Line= 3
      2928498.48     10075194.08      2930962.68     10074937.87
      2934963.62     10073580.82
#Sta/Elev= 30
  -102.2  1077.4    18.3 1072.62   123.1 1069.49   246.3 1063.49   350.2  1057.7
   616.5 1063.47   823.8 1056.85  1144.5 1036.13  1597.7 1045.83  2039.3  1035.1
  2240.3 1042.69  2635.6 1042.58  2729.8 1041.54  2759.6 1041.11  3305.8 1042.52
    3394 1040.66  3499.7 1037.38  3546.1 1034.14  3605.4 1029.18  4060.4 1019.92
  4546.1  990.57  4860.4  956.79  5158.3  955.65  5237.3  958.09  5326.2  982.02
    5389  991.16  5508.5 1002.12  5963.2 1028.23  6248.5 1040.49  6600.1 1044.19
#Mann= 18 ,-1 , 0
  -102.2      .1       0    18.3     .16       0   123.1      .1       0
   246.3     .16       0   616.5      .1       0  2635.6     .05       0
  2729.8      .1       0  2759.6     .05       0  3305.8      .1       0
    3394     .05       0  3499.7      .1       0  3546.1     .05       0
  3605.4      .1       0  4546.1     .05       0    5389     .16       0
  5508.5     .16       0  5963.2      .1       0  6248.5     .16       0
Bank Sta=4546.1,5389
XS Rating Curve= 0 ,0
Exp/Cntr=0.3,0.1

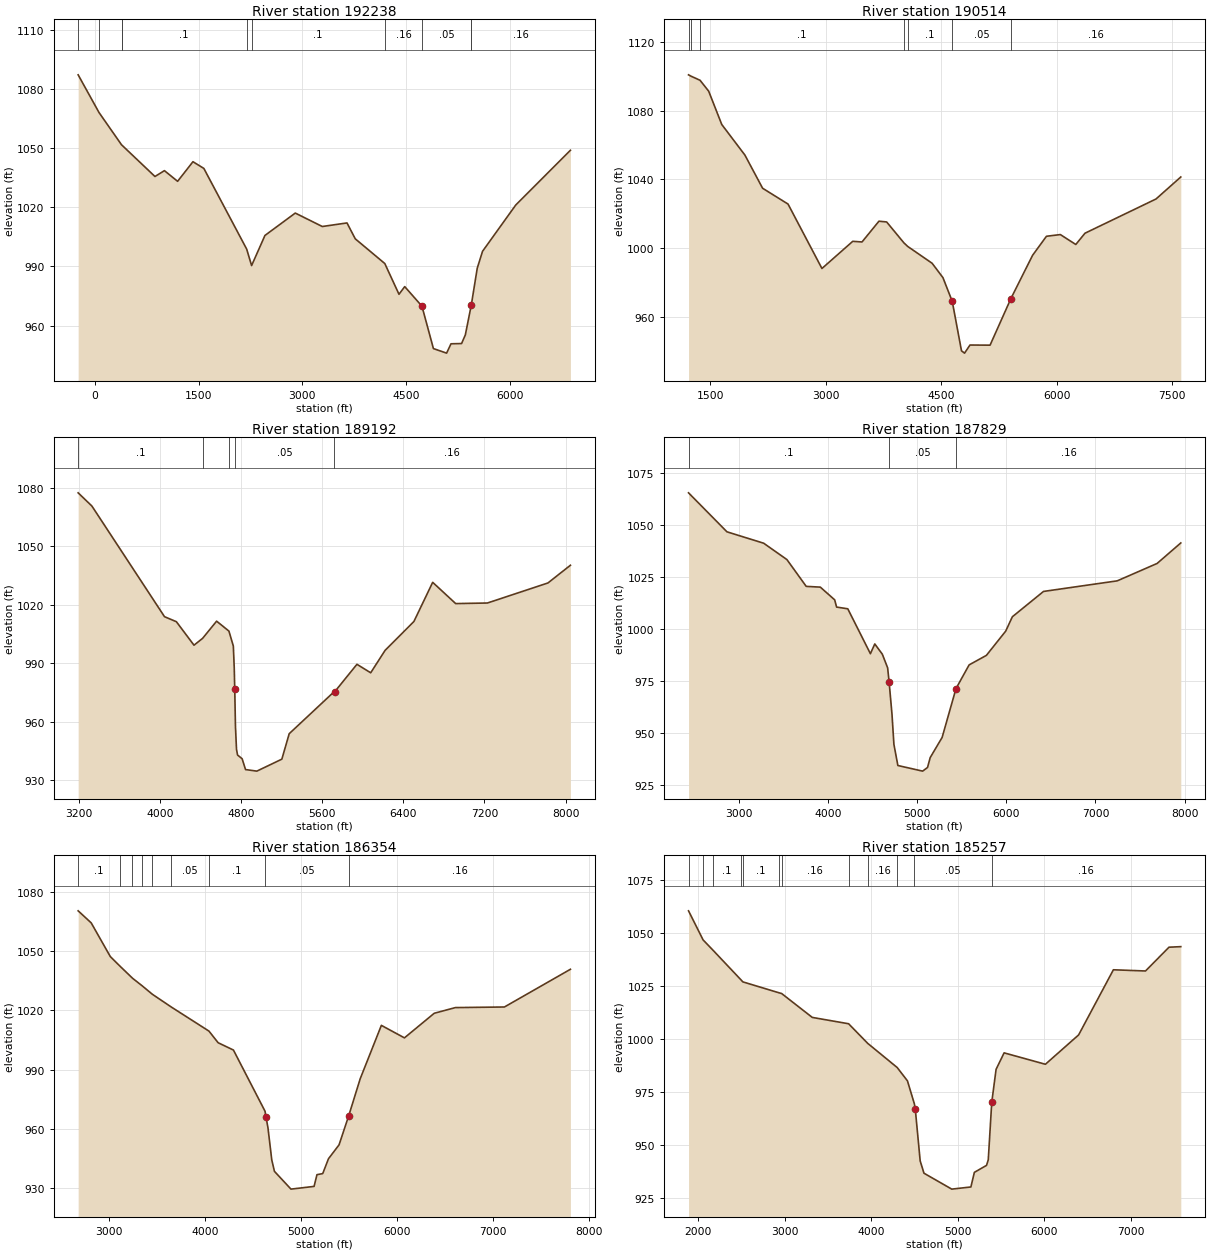
Type RM Length L Ch R = 1 ,192238  ,1724,1724,1724
BEGIN DESCRIPTION:
Mapping XS 31e63607
END DESCRIPTION:
XS GIS Cut Line= 3
      2928402.46     10075596.56      2932092.07     10076279.91
       2935355.4     10075474.12
#Sta/Elev= 30
  -240.6 1087.15      61 1068.03   385.8 1051.69   386.4 1051.67   869.3 1035.58
  1006.3 1038.55  1196.7 1033.14  1418.4 1043.08  1575.8 1039.68  2194.8  998.76
    2266  990.41  2458.7 1005.68    2897 1017.03  3287.5 1010.22  3644.5 1012.03
  3763.7 1003.98  4190.8  991.44  4395.9  975.85  4478.8  979.73  4727.5  969.81
  4893.4   948.3  5083.8     946  5147.3  950.73  5300.3  950.86  5354.5  955.23
  5440.9  970.44  5526.9  989.11  5603.3  997.65  6083.1 1021.12  6873.1 1048.89
#Mann= 10 ,-1 , 0
  -240.6     .16       0      61      .1       0   385.8     .16       0
   386.4      .1       0  2194.8     .05       0    2266      .1       0
  4190.8     .16       0  4727.5     .05       0  5440.9      .1       0
  5440.9     .16       0
Bank Sta=4727.5,5440.9
XS Rating Curve= 0 ,0
Exp/Cntr=0.3,0.1

Type RM Length L Ch R = 1 ,190514  ,1322,1322,1322
BEGIN DESCRIPTION:
Mapping XS 2c89a7d6
END DESCRIPTION:
XS GIS Cut Line= 4
      2929407.12     10077549.06      2932428.23     10077534.08
      2934535.91     10077677.17      2935547.64     10076934.39
#Sta/Elev= 30
  1220.4 1100.86  1250.1 1100.12  1369.8 1097.69  1481.8 1091.34  1651.8 1071.91
  1951.8 1054.11  2181.8 1034.76  2511.8 1025.54  2951.8  987.99  3351.8 1003.83
  3471.8 1003.45  3691.8 1015.56  3791.8 1015.11  4015.7 1002.93    4065 1000.85
  4382.1  991.03  4522.4  982.65 4643.18  968.81    4763     940  4802.8  938.67
  4873.2  943.39  5133.8  943.31  5404.5  970.49  5685.1  995.64  5865.5 1006.77
  6045.9 1007.76  6246.4 1001.99  6365.9 1008.56  7287.7  1028.5  7609.2 1041.33
#Mann= 7 ,-1 , 0
  1220.4      .1       0  1250.1     .16       0  1369.8      .1       0
  4015.7     .05       0    4065      .1       0 4643.18     .05       0
  5404.5     .16       0
Bank Sta=4643.18,5404.5
XS Rating Curve= 0 ,0
Exp/Cntr=0.3,0.1

Type RM Length L Ch R = 1 ,189192  ,1363,1363,1363
BEGIN DESCRIPTION:
Mapping XS 21c20cbf
END DESCRIPTION:
XS GIS Cut Line= 3
      2931548.63     10079354.92      2933791.86     10078709.72
      2935732.17     10077105.94
#Sta/Elev= 30
  3195.3 1077.55  3330.9 1070.75  4046.5 1013.88  4163.2 1011.31  4336.9  999.23
  4421.5 1002.73  4559.9 1011.58  4681.3 1006.48  4724.7  998.79  4733.5  987.75
  4738.7  976.49  4745.5  957.71  4755.9  945.73  4766.3  942.78  4811.3  940.87
    4845   935.3  4956.3   934.5  5202.8  940.65  5275.4  953.74  5716.3  975.23
  5722.8  975.23  5942.9  989.41  6078.4  985.05  6220.4  996.58  6504.4 1011.42
  6689.4 1031.54    6916 1020.62  7228.7 1020.91  7825.3 1031.22  8046.8 1040.32
#Mann= 5 ,-1 , 0
  3195.3      .1       0  4421.5     .16       0  4681.3      .1       0
  4738.7     .05       0  5716.3     .16       0
Bank Sta=4738.7,5722.8
XS Rating Curve= 0 ,0
Exp/Cntr=0.3,0.1

Type RM Length L Ch R = 1 ,187829  ,1475,1475,1475
BEGIN DESCRIPTION:
Mapping XS b890d0d6
END DESCRIPTION:
XS GIS Cut Line= 3
      2933469.39     10081993.58      2934915.21     10078246.08
       2935862.8     10077074.96
#Sta/Elev= 30
  2434.6 1065.61  2865.6 1046.86  3277.6 1041.38  3538.4 1033.51  3754.9 1020.63
  3913.3 1020.26  4074.4 1014.15  4095.8 1010.67  4221.5 1009.84  4475.1  988.25
  4524.4  992.93  4608.9  988.02  4668.8  981.41  4685.3  974.52  4717.5  959.08
  4738.9  944.65  4783.4  934.48  5061.4  931.78  5116.2  933.54  5146.2   938.3
  5279.9  947.98  5435.6  971.47  5582.8  982.86  5776.5  987.44    5993  999.09
    6068 1006.01  6417.5 1018.19  7244.5 1023.28  7692.1 1031.65  7957.8 1041.51
#Mann= 3 , 0 , 0
  2434.6      .1       0  4685.3     .05       0  5435.6     .16       0
Bank Sta=4685.3,5435.6
XS Rating Curve= 0 ,0
Exp/Cntr=0.3,0.1

Type RM Length L Ch R = 1 ,186354  ,1097,1097,1097
BEGIN DESCRIPTION:
Mapping XS 67e10a41
END DESCRIPTION:
XS GIS Cut Line= 3
       2935355.7     10082136.13      2935809.54     10080524.93
      2935938.68     10077077.35
#Sta/Elev= 30
  2681.6 1070.29  2817.4  1064.2  3016.5 1047.15  3113.6 1042.47  3247.2 1036.22
  3348.1 1032.36  3454.2 1028.09    3651 1021.65  4043.2 1009.47  4138.6 1003.59
  4297.9  999.89  4626.9  968.94  4636.9  965.97  4656.9  960.73  4696.9  944.34
  4724.8  938.55  4896.8  929.56  5137.2  930.94  5167.3  936.87  5227.3  937.41
  5287.4  944.94  5397.4  951.96  5497.5   966.6  5617.6  985.39  5837.7 1012.37
  6077.9 1006.05  6388.1 1018.49  6608.3 1021.36  7118.6 1021.66  7805.5 1040.73
#Mann= 9 ,-1 , 0
  2681.6      .1       0  3113.6     .05       0  3247.2      .1       0
  3348.1     .05       0  3454.2      .1       0    3651     .05       0
  4043.2      .1       0  4626.9     .05       0  5497.5     .16       0
Bank Sta=4636.9,5497.5
XS Rating Curve= 0 ,0
Exp/Cntr=0.3,0.1

Type RM Length L Ch R = 1 ,185257  ,1041,1041,1041
BEGIN DESCRIPTION:
Mapping XS 67f809a9
END DESCRIPTION:
XS GIS Cut Line= 3
      2935729.15     10082299.14      2937047.54     10080974.18
       2936651.7     10077167.94
#Sta/Elev= 30
  1885.7 1060.64  2054.1 1046.91    2165  1042.2  2491.5  1028.1    2514 1027.09
  2931.1 1021.95  2963.7 1021.57  3317.4 1010.31  3737.9 1007.31  3959.1  998.05
  4300.2  986.64  4418.8  980.34  4499.3  969.42  4509.3  967.06  4566.1  942.52
  4609.9  936.74  4931.3  929.22  5152.8  930.24    5193  937.14  5333.7  940.44
  5353.9  943.06  5394.1  970.18  5444.3  985.79  5537.1  993.57    6015  988.18
  6399.4 1002.04  6801.6  1032.8  7173.2 1032.23  7445.1 1043.46  7581.6 1043.72
#Mann= 12 ,-1 , 0
  1885.7      .1       0  2054.1     .05       0    2165      .1       0
  2491.5     .05       0    2514      .1       0  2931.1     .05       0
  2963.7     .16       0  3737.9      .1       0  3959.1     .16       0
  4300.2      .1       0  4499.3     .05       0  5394.1     .16       0
Bank Sta=4509.3,5394.1
XS Rating Curve= 0 ,0
Exp/Cntr=0.3,0.1

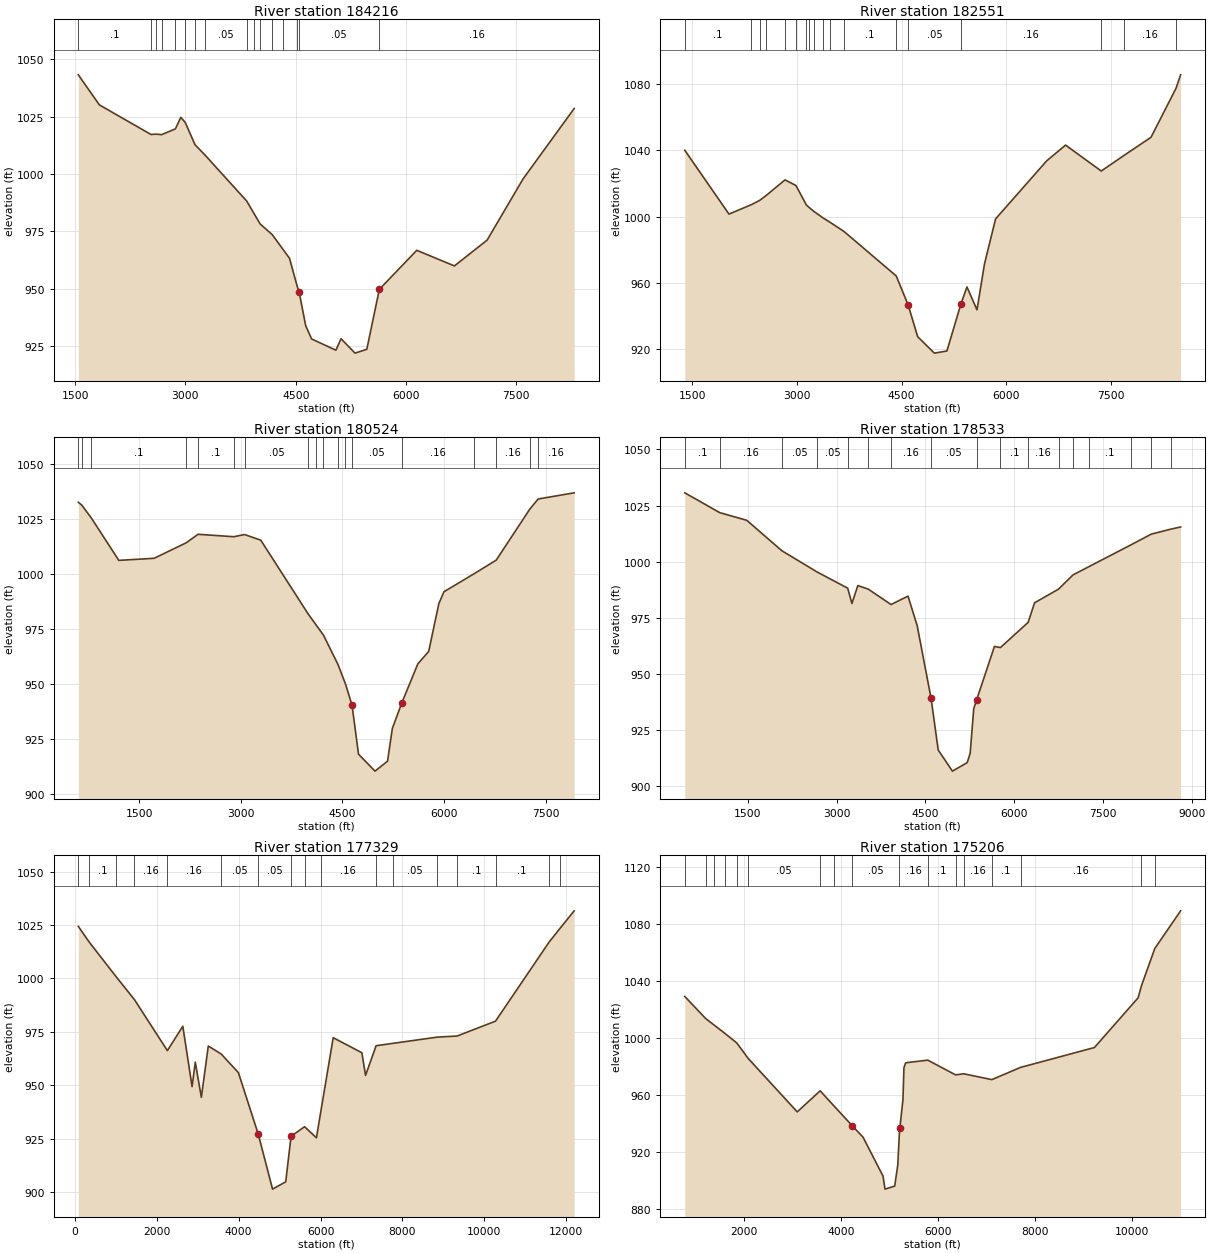
Type RM Length L Ch R = 1 ,184216  ,1665,1665,1665
BEGIN DESCRIPTION:
Mapping XS 5781f7d6
END DESCRIPTION:
XS GIS Cut Line= 4
      2936144.78      10082382.4       2937881.4     10080932.35
      2938039.07     10077639.93      2937125.21     10076887.61
#Sta/Elev= 30
  1544.2 1043.22  1829.9 1030.14  2532.1 1017.24  2597.8 1017.38  2678.1 1017.18
  2864.4  1019.7  2937.5 1024.71  2997.7 1022.51    3131 1012.77  3262.2 1008.44
  3833.3  988.27  3931.5  982.91  4015.7  978.31  4180.7  973.63  4327.1  967.21
  4415.9  963.32  4521.1  951.03  4546.1  948.75  4636.2  933.94  4716.3   928.2
  5046.6  923.31  5116.7  928.28  5306.7  922.02  5467.1  923.69  5637.3  949.79
  6146.2  966.79  6658.5     960  7102.8  971.23  7590.9  997.84  8286.5 1028.54
#Mann= 16 ,-1 , 0
  1544.2      .1       0  2532.1     .05       0  2597.8      .1       0
  2678.1     .05       0  2864.4     .16       0  2997.7      .1       0
    3131      .1       0  3262.2     .05       0  3833.3      .1       0
  3931.5     .16       0  4015.7      .1       0  4180.7     .16       0
  4327.1      .1       0  4521.1     .05       0  4546.1     .05       0
  5637.3     .16       0
Bank Sta=4546.1,5637.3
XS Rating Curve= 0 ,0
Exp/Cntr=0.3,0.1

Type RM Length L Ch R = 1 ,182551  ,2027,2027,2027
BEGIN DESCRIPTION:
Mapping XS f110a0e2
END DESCRIPTION:
XS GIS Cut Line= 4
      2936310.98     10082631.84      2938906.24     10081244.43
      2939887.42     10079811.15      2940125.17     10077406.97
#Sta/Elev= 30
  1396.4 1040.12  2028.6 1001.55  2347.3 1007.21  2468.2 1009.84  2554.3 1012.56
  2830.3 1022.22    2987 1018.84  3136.8 1007.03  3180.2 1005.41  3241.3 1003.26
  3373.5  999.27  3470.3  996.73  3673.8  991.08  4422.8  964.13  4594.2  946.42
  4728.9  927.46  4967.7   917.5  5147.3  918.78  5347.7  947.17  5434.4  957.51
  5577.9  943.67  5685.5  971.45    5844  998.64    6576 1033.75  6845.6 1043.25
    7356 1027.59  7681.4 1036.98  8068.3 1047.97  8426.3 1077.58  8492.1 1085.73
#Mann= 18 ,-1 , 0
  1396.4      .1       0  2347.3     .16       0  2468.2      .1       0
  2554.3     .05       0  2830.3     .16       0    2987      .1       0
  3136.8     .05       0  3180.2      .1       0  3241.3     .05       0
  3373.5     .16       0  3470.3     .05       0  3673.8      .1       0
  4422.8      .1       0  4594.2     .05       0  5347.7     .16       0
    7356      .1       0  7681.4     .16       0  8426.3      .1       0
Bank Sta=4594.2,5347.7
XS Rating Curve= 0 ,0
Exp/Cntr=0.3,0.1

Type RM Length L Ch R = 1 ,180524  ,1991,1991,1991
BEGIN DESCRIPTION:
Mapping XS 3410d31a
END DESCRIPTION:
XS GIS Cut Line= 3
      2938521.78     10086037.34      2940918.85     10081704.74
      2940308.95      10079418.6
#Sta/Elev= 30
   601.5 1032.44   654.1  1031.1   793.5 1025.31  1199.1 1006.11  1720.2 1007.05
    2194 1014.08  2368.2 1017.93  2897.2 1016.83  3054.2 1017.82  3293.7 1015.28
    3993  981.84  4105.2  977.07  4218.8  972.25  4434.6  958.84  4544.4  950.05
 4640.91  940.48  4736.6  918.25  4980.3  910.56    5165  915.08    5236  929.93
  5376.8  941.59  5611.8  959.17  5772.2  964.83  5922.3  986.51  5997.3  991.88
  6433.6  999.88  6769.3 1006.23  7264.2 1029.33    7387 1033.92  7919.1 1036.73
#Mann= 18 ,-1 , 0
   601.5      .1       0   654.1     .05       0   793.5      .1       0
    2194     .16       0  2368.2      .1       0  2897.2     .05       0
  3054.2     .05       0    3993     .05       0  4105.2      .1       0
  4218.8      .1       0  4434.6     .05       0  4544.4      .1       0
 4640.91     .05       0  5376.8     .16       0  6433.6      .1       0
  6769.3     .16       0  7264.2      .1       0    7387     .16       0
Bank Sta=4640.91,5376.8
XS Rating Curve= 0 ,0
Exp/Cntr=0.3,0.1

Type RM Length L Ch R = 1 ,178533  ,1204,1204,1204
BEGIN DESCRIPTION:
Mapping XS 3a03abcc
END DESCRIPTION:
XS GIS Cut Line= 4
      2939245.24     10086501.97      2942161.74     10084402.37
      2942261.75       10081565.      2941174.79       10079950.
#Sta/Elev= 30
   433.9 1030.66  1024.3 1021.83  1481.3 1018.42  2074.2 1004.85  2667.9  995.42
  3186.8  988.17  3258.5  981.35  3358.1  989.33  3534.8  987.75  3919.3  980.88
  4206.3  984.62  4360.9  971.49  4596.5  939.03  4716.6  916.06  4956.5  906.64
  5206.9  910.43  5256.9  914.61    5317  934.48    5367   938.5  5667.2  962.22
  5767.7  961.69  6236.6  972.93  6345.1  981.65  6750.3  987.75  6994.4  994.07
  7261.6  997.73  7970.6 1007.43  8318.1 1012.26  8650.5 1014.49  8813.4 1015.45
#Mann= 17 ,-1 , 0
   433.9      .1       0  1024.3     .16       0  2074.2     .05       0
  2667.9     .05       0  3186.8     .16       0  3534.8      .1       0
  3919.3     .16       0  4596.5     .05       0    5367     .16       0
  5767.7      .1       0  6236.6     .16       0  6750.3     .05       0
  6994.4     .16       0  7261.6      .1       0  7970.6     .05       0
  8318.1      .1       0  8650.5     .05       0
Bank Sta=4596.5,5367
XS Rating Curve= 0 ,0
Exp/Cntr=0.3,0.1

Type RM Length L Ch R = 1 ,177329  ,2123,2123,2123
BEGIN DESCRIPTION:
Mapping XS 7138c78d
END DESCRIPTION:
XS GIS Cut Line= 4
      2940260.01      10087272.9      2943368.36     10084394.43
      2943322.82     10079628.14      2941399.72     10077182.54
#Sta/Elev= 30
    83.2 1024.34   343.2 1017.16  1013.4 1000.64  1452.9  990.12  2258.9  966.23
    2636  977.64  2862.3   949.4  2940.5  960.83    3089  944.38  3258.6  968.39
  3575.9  964.61  3994.5  955.91  4480.3  927.08  4828.3  901.44  5150.4  904.87
  5280.4  926.14  5610.4  930.63  5900.4  925.47    6003  937.22  6310.4  972.27
  7010.5  965.25  7100.5  954.63  7358.6  968.52  7773.9  969.64  8856.2  972.55
  9335.9  973.04 10275.8  980.01 11582.3 1016.92 11858.2 1023.57 12197.3 1031.62
#Mann= 17 ,-1 , 0
    83.2     .05       0   343.2      .1       0  1013.4     .16       0
  1452.9     .16       0  2258.9     .16       0  3575.9     .05       0
  4480.3     .05       0  5280.4     .16       0  5610.4      .1       0
    6003     .16       0  7358.6      .1       0  7773.9     .05       0
  8856.2     .16       0  9335.9      .1       0 10275.8      .1       0
 11582.3     .05       0 11858.2     .05       0
Bank Sta=4480.3,5280.4
XS Rating Curve= 0 ,0
Exp/Cntr=0.3,0.1

Type RM Length L Ch R = 1 ,175206  ,2131,2131,2131
BEGIN DESCRIPTION:
Mapping XS 95bb0334
END DESCRIPTION:
XS GIS Cut Line= 3
      2942851.32     10088320.41      2943842.58     10086066.96
      2948992.14     10080270.83
#Sta/Elev= 30
   782.9 1029.24  1211.7  1013.8  1384.3 1009.25  1602.8  1003.5    1854  996.63
  2087.3  985.82  3099.3  948.23  3571.8  963.01  3862.7  952.15  4235.8  938.37
  4455.1  930.46  4866.5  903.17  4908.1  893.99  5107.4  896.11  5170.9     911
  5206.1  934.72  5213.6  937.16  5277.1  956.64    5298  979.26    5334   982.7
  5789.3  984.55  6360.6  974.21  6529.8  974.96  7108.6  970.87  7699.3  979.44
  9222.5  993.41 10122.3 1028.31 10191.6 1036.83 10466.2 1062.94   10998 1089.38
#Mann= 17 ,-1 , 0
   782.9      .1       0  1211.7     .05       0  1384.3      .1       0
  1602.8     .05       0    1854     .05       0  2087.3     .05       0
  3571.8      .1       0  3862.7     .05       0  4235.8     .05       0
  5206.1     .16       0  5789.3      .1       0  6360.6      .1       0
  6529.8     .16       0  7108.6      .1       0  7699.3     .16       0
 10191.6      .1       0 10466.2     .16       0
Bank Sta=4235.8,5213.6
XS Rating Curve= 0 ,0
Exp/Cntr=0.3,0.1

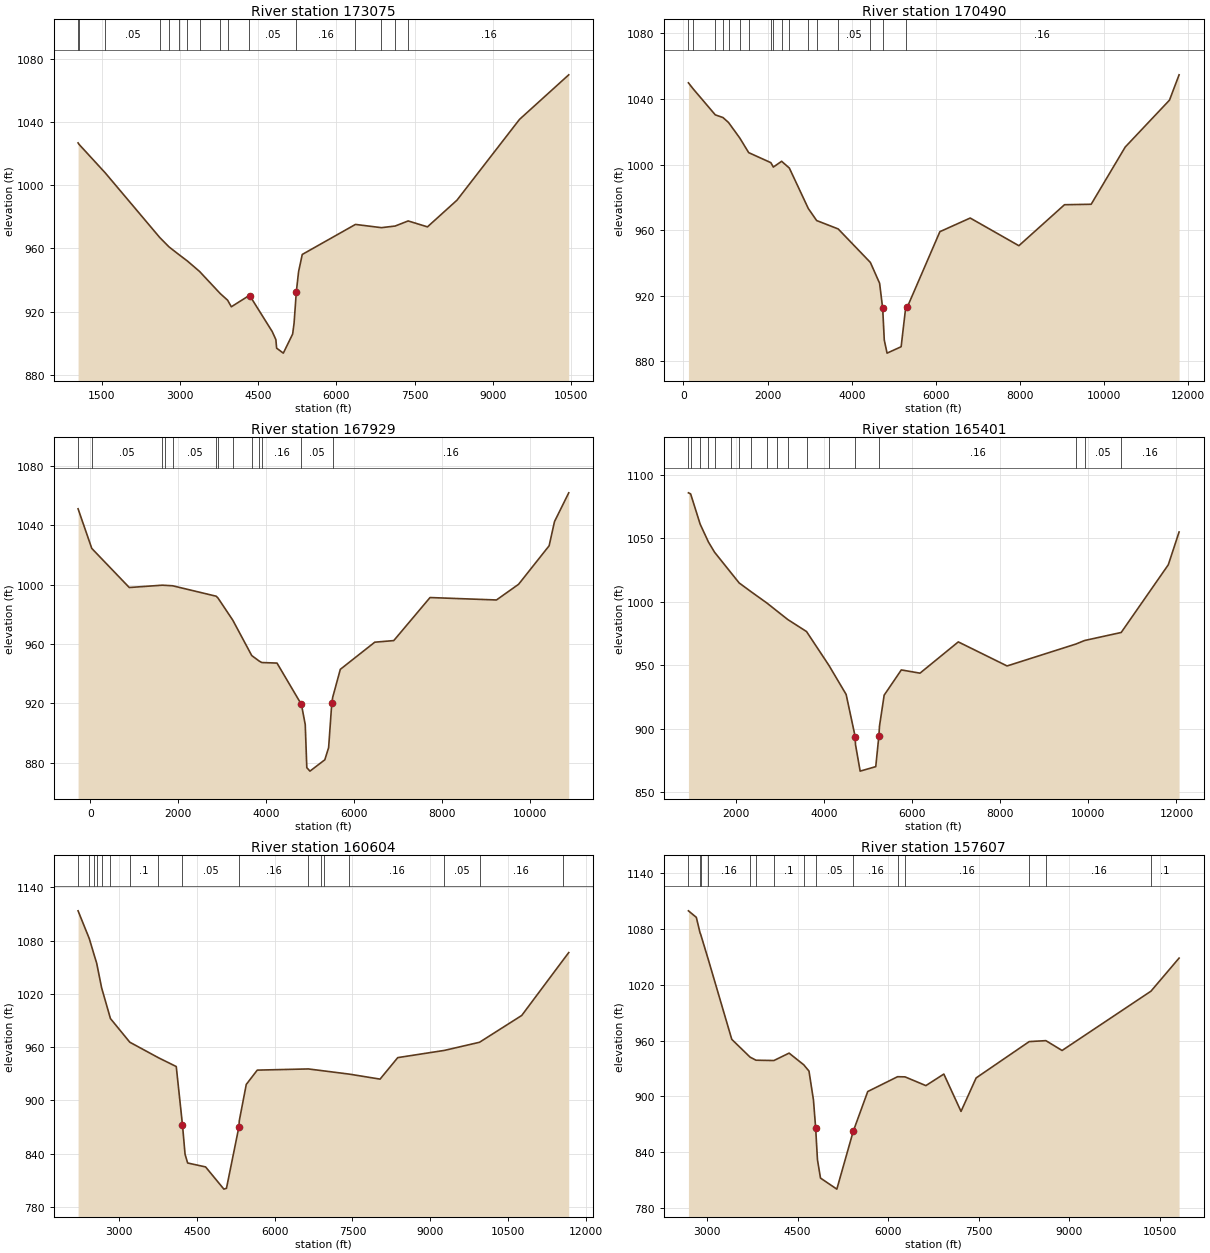
Type RM Length L Ch R = 1 ,173075  ,2585,2585,2585
BEGIN DESCRIPTION:
Mapping XS 212ea356
END DESCRIPTION:
XS GIS Cut Line= 3
      2943209.75     10088819.64      2948915.14      10084410.6
      2949228.35     10082227.84
#Sta/Elev= 30
  1041.5 1026.69  1060.5 1025.77  1563.4 1007.71  2609.6  966.81  2787.7  960.87
  2985.4  955.81  3138.6  951.99  3372.2  945.39  3766.6  931.47  3912.1  927.14
  3982.4  923.02    4313  929.88  4338.4  929.92  4766.7  907.37  4837.3  902.22
  4851.8  896.82  4980.2  893.69  5158.9  905.76    5186  912.43  5229.5  932.41
    5273  945.22  5343.6  956.12  6364.2  975.11  6862.1  973.07  7125.8  974.09
  7376.3  977.32  7746.2  973.57  8312.5  990.45  9512.1 1041.55 10457.1 1069.76
#Mann= 16 ,-1 , 0
  1041.5     .05       0  1060.5      .1       0  1563.4     .05       0
  2609.6     .05       0  2787.7     .16       0  2985.4     .05       0
  3138.6      .1       0  3372.2     .16       0  3766.6      .1       0
  3912.1     .16       0    4313     .05       0  5229.5     .16       0
  6364.2     .16       0  6862.1      .1       0  7125.8      .1       0
  7376.3     .16       0
Bank Sta=4338.4,5229.5
XS Rating Curve= 0 ,0
Exp/Cntr=0.3,0.1

Type RM Length L Ch R = 1 ,170490  ,2561,2561,2561
BEGIN DESCRIPTION:
PEDERNALES RIVER 24.0
END DESCRIPTION:
XS GIS Cut Line= 3
      2942857.68     10090980.16      2948361.22     10088161.54
      2950138.87     10082976.85
#Sta/Elev= 30
   118.5 1049.82   232.6  1046.1   757.2 1030.29   940.8 1028.64  1072.1 1025.62
  1339.8 1016.15  1551.5 1007.24  2077.3 1001.14  2137.6  998.44    2334 1001.97
  2517.7  997.84  2968.9  973.14  3166.9  965.82  3679.1  960.69  4444.4  940.25
  4663.4  927.56    4737  912.19  4774.4  892.93  4840.7  884.94  5175.2  888.84
  5279.4  911.82  5323.9  913.13  6096.5  959.03  6817.5  967.35  7974.4  950.47
  9058.7  975.47  9692.9  975.75 10501.8 1010.64 11554.6 1039.27 11782.8 1054.71
#Mann= 17 ,-1 , 0
   118.5     .05       0   232.6      .1       0   757.2     .16       0
   940.8      .1       0  1072.1     .16       0  1339.8     .16       0
  1551.5      .1       0  2077.3     .05       0  2137.6      .1       0
    2334     .05       0  2517.7      .1       0  2968.9     .05       0
  3166.9     .16       0  3679.1     .05       0  4444.4     .16       0
    4737     .05       0  5279.4     .16       0
Bank Sta=4737,5323.9
XS Rating Curve= 0 ,0
Exp/Cntr=0.3,0.1

Type RM Length L Ch R = 1 ,167929  ,2528,2528,2528
BEGIN DESCRIPTION:
PEDERNALES RIVER 23.0
END DESCRIPTION:
XS GIS Cut Line= 4
      2946312.21       10095455.      2947662.45     10091543.61
      2950354.58     10089688.71        2950726.     10085960.63
#Sta/Elev= 30
  -278.2 1051.23    33.4 1024.49   885.9   998.1  1637.2  999.68  1702.4  999.57
  1871.2  999.28  2862.1  992.23  2904.1  990.95  3238.5   976.1  3669.5   952.2
  3836.4  948.53  3897.3  947.49    4244  947.12  4799.2  919.18  4885.8  905.64
  4921.6  876.54    4993  874.21  5330.7  881.86  5417.3  890.05    5489  919.99
  5509.9     924  5683.1  942.89  6465.8  961.21  6898.3   962.3  7722.4  991.34
  9232.7   989.7  9736.1  1000.3 10430.2 1026.29 10551.6 1042.57 10875.5    1062
#Mann= 13 ,-1 , 0
  -278.2     .16       0    33.4     .05       0  1637.2      .1       0
  1702.4     .16       0  1871.2     .05       0  2862.1      .1       0
  2904.1     .05       0  3238.5      .1       0  3669.5     .16       0
  3836.4      .1       0  3897.3     .16       0  4799.2     .05       0
  5509.9     .16       0
Bank Sta=4799.2,5489
XS Rating Curve= 0 ,0
Exp/Cntr=0.3,0.1

Type RM Length L Ch R = 1 ,165401  ,4797,4797,4797
BEGIN DESCRIPTION:
PEDERNALES RIVER 270.0
END DESCRIPTION:
XS GIS Cut Line= 3
       2947461.4     10095706.95      2951524.09      10091460.1
       2951093.8     10086220.31
#Sta/Elev= 30
   925.6 1085.75   975.9  1084.9  1192.6 1061.01  1381.1  1046.9  1517.4 1039.01
  1893.4 1022.69  2077.2 1014.72  2351.7 1007.71  2701.2  999.04  2939.2   992.5
  3179.6   985.9  3605.7  976.42  4114.7  949.72  4504.6  926.85  4709.6  893.63
  4716.9  887.39  4822.6  866.41  5176.7  869.95  5247.4  894.06  5261.6  901.91
  5367.6  926.29  5756.6  946.17  6180.9  943.62  7049.9  968.26  8156.6   949.3
  9718.3  966.57  9916.3  969.36 10746.8  975.69 11815.4 1029.03 12060.2 1054.88
#Mann= 18 ,-1 , 0
   925.6     .05       0   975.9      .1       0  1192.6     .05       0
  1381.1     .05       0  1517.4      .1       0  1893.4      .1       0
  2077.2     .05       0  2351.7     .05       0  2701.2     .05       0
  2939.2      .1       0  3179.6     .16       0  3605.7     .05       0
  4114.7     .16       0  4716.9     .05       0  5261.6     .16       0
  9718.3      .1       0  9916.3     .05       0 10746.8     .16       0
Bank Sta=4709.6,5247.4
XS Rating Curve= 0 ,0
Exp/Cntr=0.3,0.1

Type RM Length L Ch R = 1 ,160604  ,2997,2997,2997
BEGIN DESCRIPTION:
PEDERNALES RIVER 271.0
END DESCRIPTION:
XS GIS Cut Line= 3
      2956209.67     10093731.34      2951941.59     10089277.71
      2951435.06      10086017.5
#Sta/Elev= 30
  2205.2 1113.61  2421.8 1082.28  2522.1 1062.62  2563.8 1054.71  2658.7 1027.06
  2829.7  992.21  3203.4  965.53  3756.7  948.01  4099.7  938.11  4220.1  872.17
  4269.5  839.33  4319.2   829.4  4665.8  824.96    5019  799.94  5068.9  800.91
  5309.2  870.19  5316.4  877.15  5450.7  917.93    5663  934.07  6649.8   935.4
  6896.9  933.57  6955.5  933.14  7438.5  929.56  8032.4  923.93  8373.8  948.16
  9274.1   956.3  9951.5  965.46 10766.1  995.67 11554.1 1057.32 11673.1 1066.55
#Mann= 17 ,-1 , 0
  2205.2      .1       0  2421.8      .1       0  2522.1     .05       0
  2563.8      .1       0  2658.7     .05       0  2829.7     .05       0
  3203.4      .1       0  3756.7     .16       0  4220.1     .05       0
  5316.4     .16       0  6649.8      .1       0  6896.9     .16       0
  6955.5      .1       0  7438.5     .16       0  9274.1     .05       0
  9951.5     .16       0 11554.1      .1       0
Bank Sta=4220.1,5309.2
XS Rating Curve= 0 ,0
Exp/Cntr=0.3,0.1

Type RM Length L Ch R = 1 ,157607  ,2162,2162,2162
BEGIN DESCRIPTION:
PEDERNALES RIVER 272.0
END DESCRIPTION:
XS GIS Cut Line= 3
      2957488.99     10089241.87      2952441.44     10088867.19
      2951723.18     10085890.77
#Sta/Elev= 30
  2693.4 1099.37  2824.3 1092.35  2886.7 1075.45  2894.4 1074.51    3024  1046.7
  3411.1  961.25  3714.5  942.12  3813.1  938.82    4109  938.49  4360.2  946.44
  4602.2  933.93  4689.4  927.13  4763.4  896.13  4799.7  866.14  4829.8  831.84
  4879.9  812.17  5150.4  800.28  5421.4   862.3  5662.1  905.17  6155.9  921.09
  6279.1  920.93  6624.7  911.53    6922  923.94  7206.3  883.81    7457  919.81
  8335.7  958.84  8611.3  959.85  8879.7  949.28 10351.1 1013.01 10816.7 1048.57
#Mann= 15 ,-1 , 0
  2693.4      .1       0  2886.7     .16       0  2894.4      .1       0
    3024     .16       0  3714.5      .1       0  3813.1     .16       0
    4109      .1       0  4602.2     .16       0  4799.7     .05       0
  5421.4     .16       0  6155.9      .1       0  6279.1     .16       0
  8335.7     .05       0  8611.3     .16       0 10351.1      .1       0
Bank Sta=4799.7,5421.4
XS Rating Curve= 0 ,0
Exp/Cntr=0.3,0.1

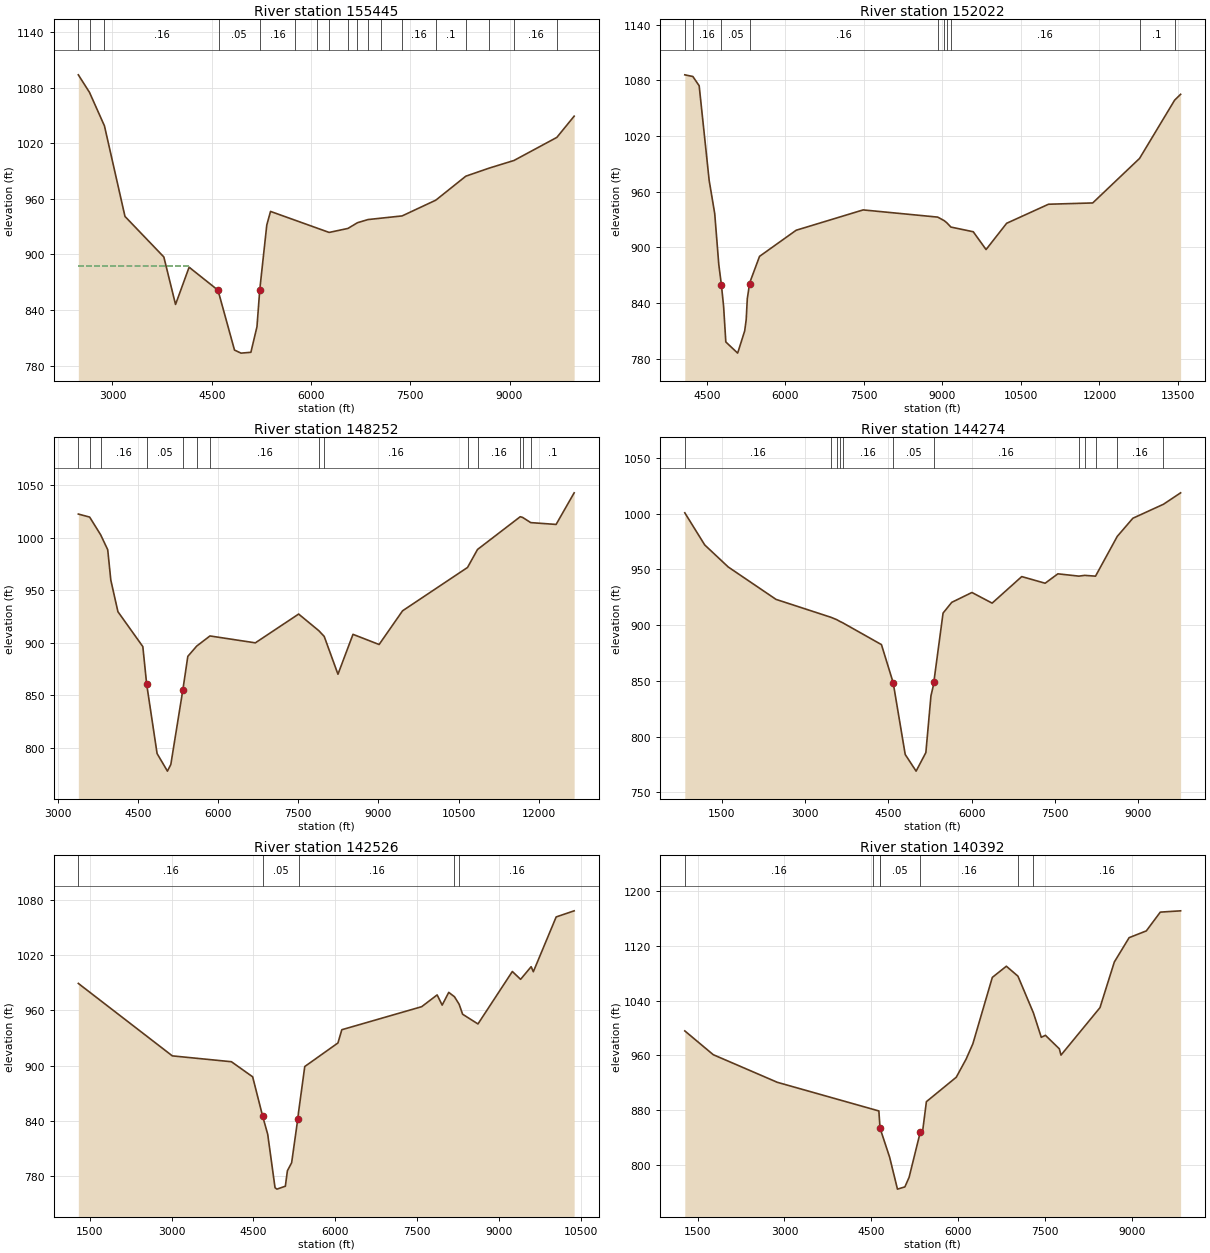
Type RM Length L Ch R = 1 ,155445  ,3423,3423,3423
BEGIN DESCRIPTION:
PEDERNALES RIVER 273.0
END DESCRIPTION:
XS GIS Cut Line= 3
      2957491.84     10089007.51      2954686.75     10086290.64
       2951207.9     10085414.45
#Sta/Elev= 30
  2483.8 1093.96  2652.6 1074.99  2878.6 1038.82  3188.9  941.01    3776  897.23
  3952.7  845.95  4157.9  886.18  4589.3  861.64  4603.5  858.96  4843.8  796.69
  4942.5  793.38  5091.4  794.27  5183.3  821.92  5225.7     862  5331.7  931.79
  5388.3  946.43  5761.1  936.88  6097.2  928.27  6274.1  923.74  6558.4  928.07
  6702.3  934.24  6860.4  937.63  7061.8  939.17  7376.9  941.58  7885.5  958.58
  8339.4  984.49  8689.2  993.13  9067.7 1001.47  9714.8 1026.38  9976.4 1049.31
#Mann= 18 ,-1 , 0
  2483.8     .16       0  2652.6      .1       0  2878.6     .16       0
  4603.5     .05       0  5225.7     .16       0  5761.1      .1       0
  6097.2     .16       0  6274.1     .16       0  6558.4      .1       0
  6702.3      .1       0  6860.4     .05       0  7061.8     .16       0
  7376.9     .16       0  7885.5      .1       0  8339.4      .1       0
  8689.2      .1       0  9067.7     .16       0  9714.8      .1       0
#XS Ineff= 2 , 0
         4172.73  887.11
Permanent Ineff=
       F       F
Bank Sta=4589.3,5225.7
XS Rating Curve= 0 ,0
Exp/Cntr=0.3,0.1

Type RM Length L Ch R = 1 ,152022  ,3770,3770,3770
BEGIN DESCRIPTION:
PEDERNALES RIVER 274.0
END DESCRIPTION:
XS GIS Cut Line= 3
      2959556.26     10088434.01      2957190.58     10085982.94
      2951296.61     10084556.16
#Sta/Elev= 30
  4080.1 1086.07  4234.5 1084.26  4354.6 1074.28  4545.5  972.29  4651.5  936.61
  4729.4  881.65  4778.8  859.98  4821.3   836.6  4863.7  798.17  5089.8  786.14
  5224.4  810.17  5252.7  822.05    5274  844.79  5316.5  860.76  5323.4  862.45
  5507.4  890.41  6207.3  918.57  7486.6  940.48  8911.2  932.73  9036.6  928.87
  9086.9  926.52  9162.6     922    9590  916.94  9834.6  897.77 10227.7  926.07
 11027.6  946.61 11871.8  947.99 12766.2  995.97   13436 1058.74 13550.8 1065.09
#Mann= 10 ,-1 , 0
  4080.1      .1       0  4234.5     .16       0  4778.8     .05       0
  5323.4     .16       0  8911.2      .1       0  9036.6     .16       0
  9086.9      .1       0  9162.6     .16       0 12766.2      .1       0
   13436     .16       0
Bank Sta=4778.8,5316.5
XS Rating Curve= 0 ,0
Exp/Cntr=0.3,0.1

Type RM Length L Ch R = 1 ,148252  ,3978,3978,3978
BEGIN DESCRIPTION:
PEDERNALES RIVER 275.0
END DESCRIPTION:
XS GIS Cut Line= 3
      2960054.12     10083960.89      2956005.98     10084900.61
      2950993.11     10083849.34
#Sta/Elev= 30
  3383.4 1022.31  3595.4 1019.43  3800.9 1002.61  3933.3  988.43  3991.4  959.45
  4124.4  929.49  4590.3  896.31  4662.2  860.55  4857.2  794.61  5050.5  777.91
  5113.9  784.18  5339.7  855.37  5432.1  887.02  5598.7  896.81  5846.2  906.43
  6695.3  899.87  7505.8  927.24  7884.3  911.39  7984.2  905.98  8241.7  870.03
  8522.7  907.96  9011.5   898.3  9450.5  930.33 10665.6  971.53 10852.6  988.63
 11652.4 1019.79 11696.1 1019.13 11848.9 1014.18 12323.3 1012.45 12661.1  1042.5
#Mann= 14 ,-1 , 0
  3383.4     .16       0  3595.4      .1       0  3800.9     .16       0
  4662.2     .05       0  5339.7     .16       0  5598.7      .1       0
  5846.2     .16       0  7884.3      .1       0  7984.2     .16       0
 10665.6      .1       0 10852.6     .16       0 11652.4      .1       0
 11696.1     .16       0 11848.9      .1       0
Bank Sta=4662.2,5339.7
XS Rating Curve= 0 ,0
Exp/Cntr=0.3,0.1

Type RM Length L Ch R = 1 ,144274  ,1748,1748,1748
BEGIN DESCRIPTION:
PEDERNALES RIVER 276.0
END DESCRIPTION:
XS GIS Cut Line= 3
      2959371.63     10082285.78      2956851.02     10081838.04
      2950685.76     10083402.78
#Sta/Elev= 30
   837.9 1000.88  1196.6  972.03  1619.8  952.24  2480.3  923.15  3469.8  907.06
  3572.7  904.94  3635.7   903.2  3675.6  902.27    4376  882.59  4587.1  848.41
  4803.7  783.96  4999.5  769.03  5175.1  785.68  5266.8  836.63  5312.9  846.49
  5319.6  849.34  5484.6  910.88  5640.6  920.51    6004  929.36  6367.5   919.8
    6900  943.64  7321.1  937.67  7550.2  946.11  7928.6  944.04  8033.6  944.73
  8227.3  944.01  8618.5   979.7  8899.6     996  9449.8 1008.55  9758.7 1018.81
#Mann= 12 ,-1 , 0
   837.9     .16       0  3469.8      .1       0  3572.7     .16       0
  3635.7      .1       0  3675.6     .16       0  4587.1     .05       0
  5312.9     .16       0  7928.6      .1       0  8033.6     .16       0
  8227.3      .1       0  8618.5     .16       0  9449.8      .1       0
Bank Sta=4587.1,5319.6
XS Rating Curve= 0 ,0
Exp/Cntr=0.3,0.1

Type RM Length L Ch R = 1 ,142526  ,2134,2134,2134
BEGIN DESCRIPTION:
PEDERNALES RIVER 277.0
END DESCRIPTION:
XS GIS Cut Line= 4
      2959322.71     10082024.75      2956596.41     10081366.15
      2953353.73     10078227.17      2953661.42     10076487.39
#Sta/Elev= 30
  1291.4  989.27  3013.8  910.63  4096.1  904.29  4485.3  887.92  4669.2  845.02
  4761.3  825.56  4895.5  767.55  4930.5  766.02  5084.5  769.18  5121.9  785.95
  5199.6  794.62  5312.8  842.33  5326.9  849.76  5440.1  899.08  6048.2  924.66
    6119  939.02  7582.9  964.04  7865.7  976.81  7957.7  965.73  8077.9  979.55
  8182.6  974.83  8268.7  966.67  8332.5  955.83  8613.5  945.29  9243.4 1002.21
  9394.7  993.71  9588.3 1007.44  9628.2 1001.96 10046.5 1061.43   10376 1068.06
#Mann= 5 ,-1 , 0
  1291.4     .16       0  4669.2     .05       0  5326.9     .16       0
  8182.6      .1       0  8268.7     .16       0
Bank Sta=4669.2,5312.8
XS Rating Curve= 0 ,0
Exp/Cntr=0.3,0.1

Type RM Length L Ch R = 1 ,140392  ,2210,2210,2210
BEGIN DESCRIPTION:
PEDERNALES RIVER 278.0
END DESCRIPTION:
XS GIS Cut Line= 3
      2959504.06     10082105.15      2956123.43     10077480.01
      2954274.93     10075321.73
#Sta/Elev= 30
  1276.9  995.83  1768.6  961.09  2876.8  920.76    4530  881.37  4631.2  878.96
  4652.1  853.78  4817.3  811.51    4953  764.82  5081.3   768.1    5154  782.01
  5346.3  847.73  5390.3  850.98  5452.9  892.49  5969.5   928.2  6140.9  954.87
    6256  976.95  6592.5 1073.92  6835.2 1090.25  7035.5 1075.73  7303.1 1022.09
  7439.1  986.47  7510.5   989.4  7751.4  969.63  7779.4  960.48  8453.3 1029.75
  8701.4 1096.37  8957.1 1131.94  9254.6 1141.84  9496.1 1169.24  9847.5 1171.13
#Mann= 7 ,-1 , 0
  1276.9     .16       0    4530      .1       0  4652.1     .16       0
  4652.1     .05       0  5346.3     .16       0  7035.5      .1       0
  7303.1     .16       0
Bank Sta=4652.1,5346.3
XS Rating Curve= 0 ,0
Exp/Cntr=0.3,0.1