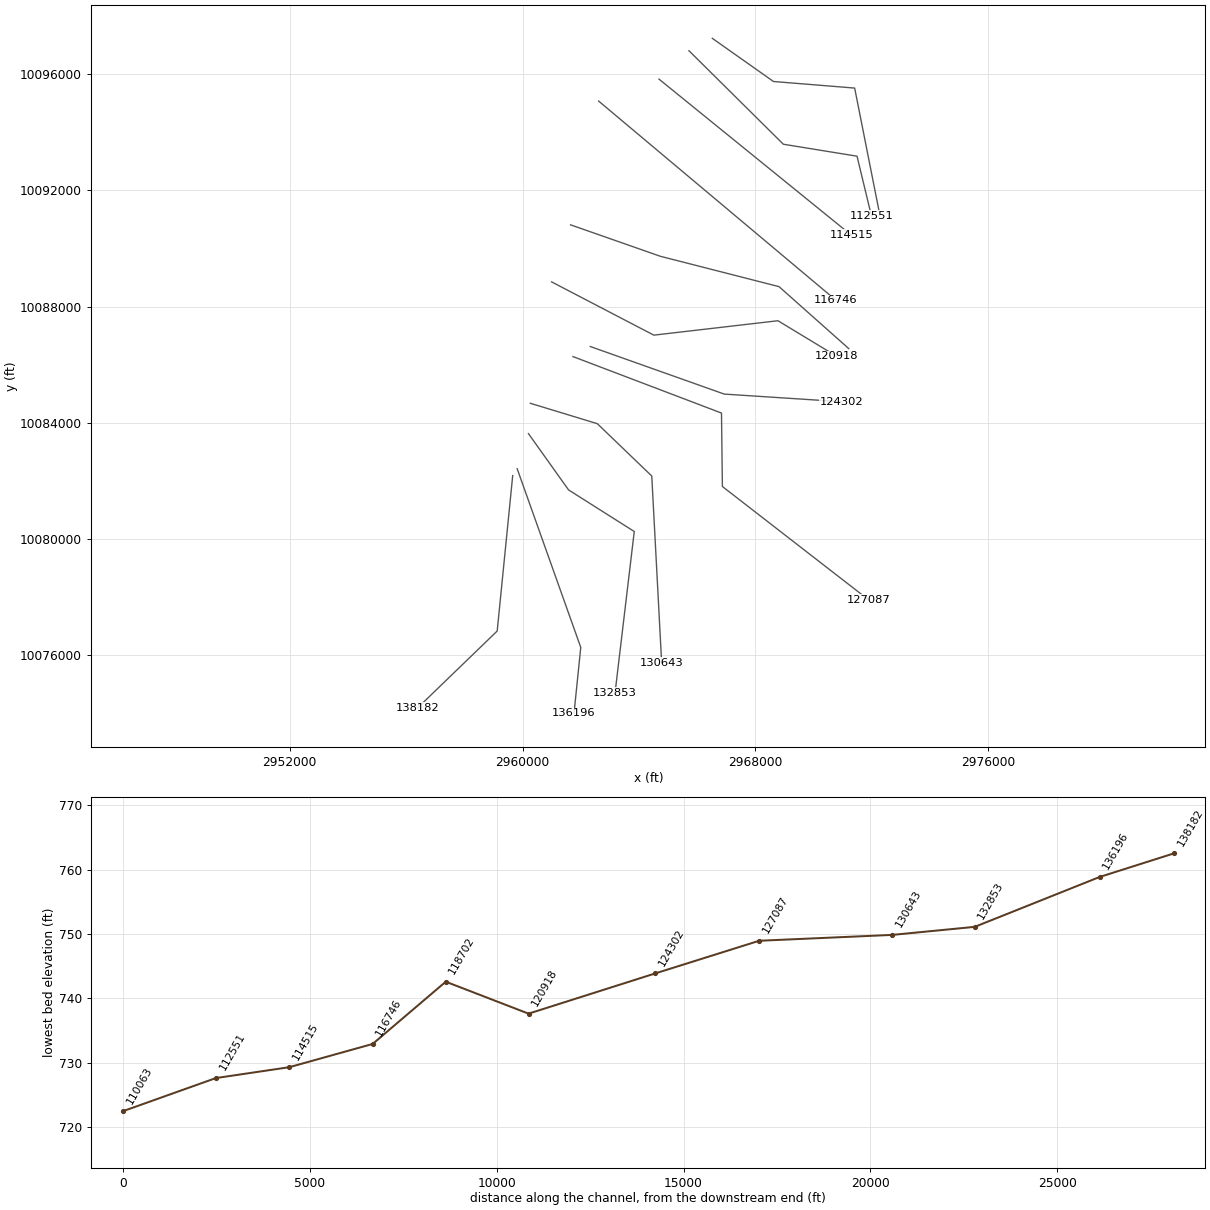
HEC-RAS study PEDERNALES RIVER.prj: PEDERNALES RIVER Base Level Engineering

--- PEDERNALES RIVER.g02 (geometry) --- (continued)

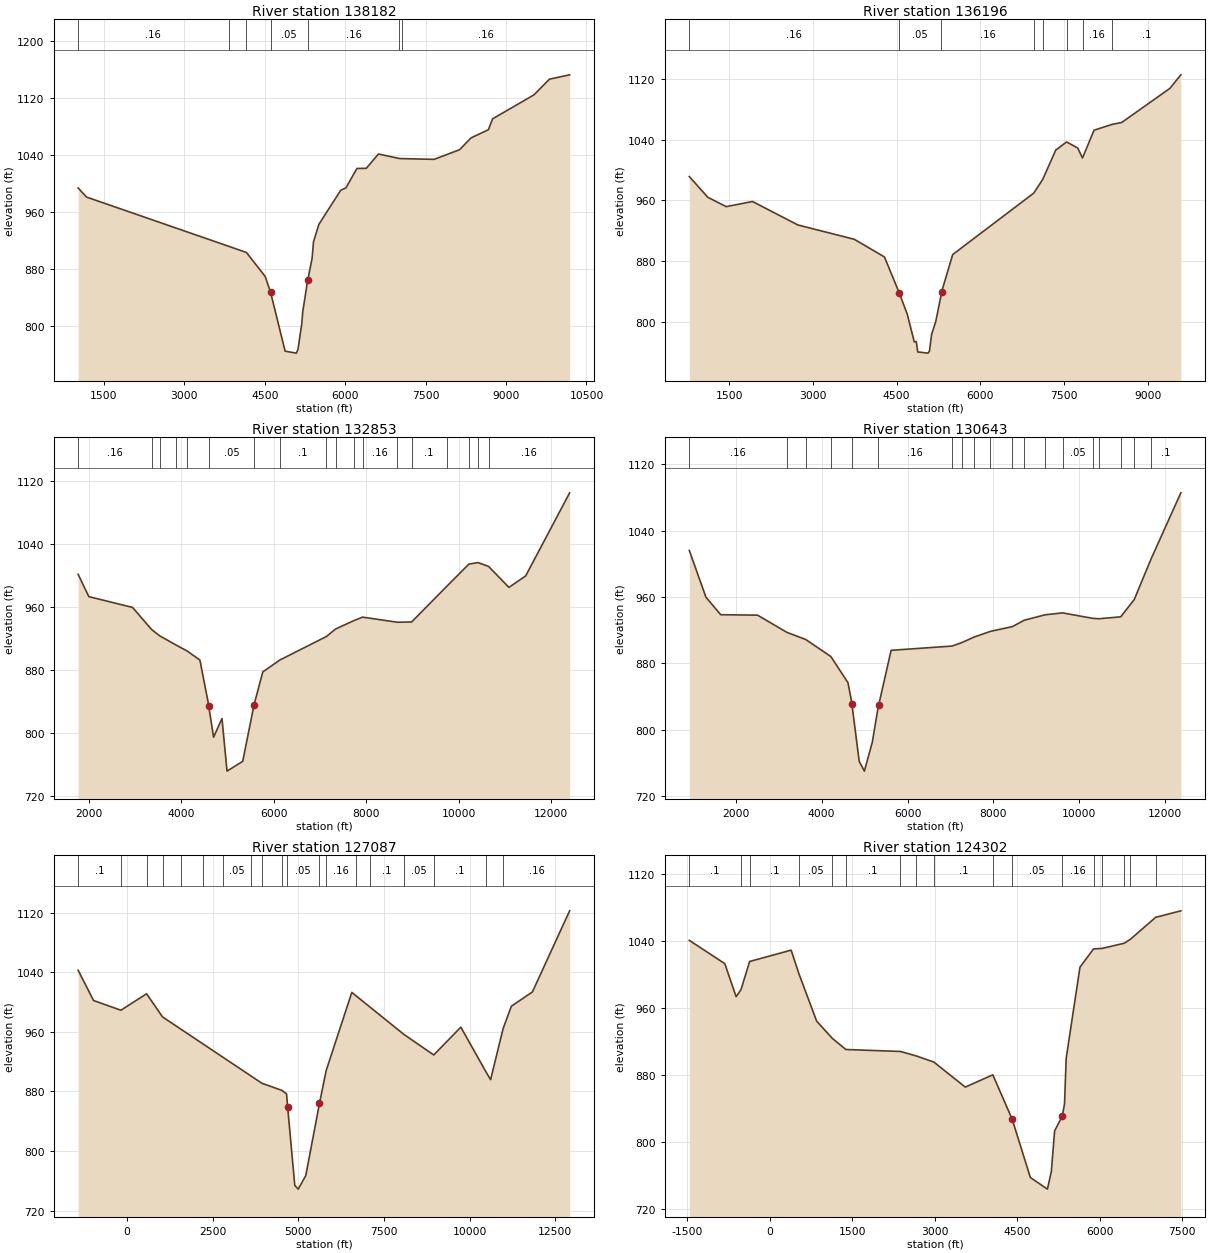
Type RM Length L Ch R = 1 ,138182  ,1986,1986,1986
BEGIN DESCRIPTION:
PEDERNALES RIVER 279.0
END DESCRIPTION:
XS GIS Cut Line= 3
      2959659.31     10082185.19       2959126.2      10076839.9
      2956398.19     10074202.03
#Sta/Elev= 30
  1019.2  994.17  1177.6  981.33  3824.4  912.42  4158.2  903.65  4508.5     870
  4609.1  847.66  4879.7  765.22  5090.5   762.5  5120.9  768.24  5191.3  804.24
  5207.9  820.32  5301.8  865.21  5382.2  895.09  5409.1  918.75  5509.8  943.21
  5917.3  990.99  6012.9  994.15  6219.2 1021.48  6393.8 1021.72  6620.1 1041.78
  7008.2 1035.53  7051.4  1035.3  7659.7 1034.27  8133.5 1047.79  8345.7 1064.33
  8670.9 1075.85  8748.8 1091.08  9519.5 1124.66  9809.7 1146.75 10185.8 1152.82
#Mann= 7 ,-1 , 0
  1019.2     .16       0  3824.4      .1       0  4158.2     .16       0
  4609.1     .05       0  5301.8     .16       0  7008.2      .1       0
  7051.4     .16       0
Bank Sta=4609.1,5301.8
XS Rating Curve= 0 ,0
Exp/Cntr=0.3,0.1

Type RM Length L Ch R = 1 ,136196  ,3343,3343,3343
BEGIN DESCRIPTION:
PEDERNALES RIVER 280.0
END DESCRIPTION:
XS GIS Cut Line= 3
      2959812.65     10082421.41      2961997.82     10076276.32
      2961765.41     10074008.25
#Sta/Elev= 30
   786.6  991.37  1117.9  964.01  1446.6  951.72  1918.8  958.46  2730.4   927.6
  3741.9  908.69  4281.2  885.44  4548.2  837.75  4689.9  810.03  4815.2  773.63
  4851.3  774.12  4876.8   760.4  5061.7  758.84  5087.4  761.52    5125  783.47
  5199.3  800.37    5298  835.97  5305.5  839.76  5503.3  888.62  6952.5  969.37
  7112.8  987.21  7348.9 1026.19  7543.9 1036.88  7741.1 1028.98    7828 1015.83
    8034 1052.34  8354.8 1059.95  8530.6 1062.55  9392.1  1107.4  9588.6 1125.26
#Mann= 8 ,-1 , 0
   786.6     .16       0  4548.2     .05       0    5298     .16       0
  6952.5      .1       0  7112.8     .16       0  7543.9      .1       0
    7828     .16       0  8354.8      .1       0
Bank Sta=4548.2,5305.5
XS Rating Curve= 0 ,0
Exp/Cntr=0.3,0.1

Type RM Length L Ch R = 1 ,132853  ,2210,2210,2210
BEGIN DESCRIPTION:
PEDERNALES RIVER 281.0
END DESCRIPTION:
XS GIS Cut Line= 4
      2960200.13     10083629.46      2961578.22     10081693.24
      2963835.49     10080262.69      2963174.86     10074708.11
#Sta/Elev= 30
  1762.7  1001.6  1994.7  973.15  2941.5  959.41  3352.1  931.39  3529.8  923.23
  3881.4  911.59  4115.7  904.27    4400  892.43  4595.7  833.46  4601.6  829.78
    4696  794.27  4877.9  818.04  4986.9  751.09    5327  763.56  5572.7  835.67
  5761.5  877.34    6133  892.57  7138.3  922.35  7337.3  931.92  7735.5  942.65
  7920.5  947.04  8676.8  940.56  8983.7  940.87  9745.6  986.28 10223.9 1014.53
   10423 1016.46 10650.9 1011.58 11090.6  984.91 11453.1  999.48 12405.4 1105.23
#Mann= 18 ,-1 , 0
  1762.7     .16       0  3352.1      .1       0  3529.8     .16       0
  3881.4      .1       0  4115.7     .16       0  4601.6     .05       0
  5572.7     .16       0    6133      .1       0  7138.3     .16       0
  7337.3     .16       0  7735.5      .1       0  7920.5     .16       0
  8676.8     .05       0  8983.7      .1       0  9745.6     .16       0
 10223.9     .08       0   10423      .1       0 10650.9     .16       0
Bank Sta=4595.7,5572.7
XS Rating Curve= 0 ,0
Exp/Cntr=0.3,0.1

Type RM Length L Ch R = 1 ,130643  ,3556,3556,3556
BEGIN DESCRIPTION:
PEDERNALES RIVER 282.0
END DESCRIPTION:
XS GIS Cut Line= 4
      2960265.41     10084671.92      2962565.79     10083971.09
      2964436.97      10082171.2      2964776.66     10075742.96
#Sta/Elev= 30
     922 1016.11  1308.6  959.75  1652.6  938.56  2510.1  938.04  3189.6  917.37
  3632.5  908.61    4215  888.16    4614  856.59  4698.9  833.57  4705.8   830.7
  4875.6  761.61  4995.5  749.84  5179.7  784.59  5321.2  828.43  5328.4  829.46
  5618.4   895.6  7038.1  900.75  7260.1  904.88  7557.5  911.76  7929.5  918.47
  8440.3  924.21  8716.6  931.94  9207.9   938.5  9607.1  940.79 10305.3  934.21
 10455.4  933.72 10961.6  936.03 11276.9  956.96 11664.4 1005.46 12360.3 1085.64
#Mann= 19 ,-1 , 0
     922     .16       0  3189.6      .1       0  3632.5      .1       0
    4215     .16       0  4698.9     .05       0  5321.2     .16       0
  7038.1     .05       0  7260.1     .16       0  7557.5     .16       0
  7929.5     .05       0  8440.3      .1       0  8716.6     .05       0
  9207.9     .05       0  9607.1     .05       0 10305.3      .1       0
 10455.4     .05       0 10961.6     .16       0 11276.9     .16       0
 11664.4      .1       0
Bank Sta=4705.8,5328.4
XS Rating Curve= 0 ,0
Exp/Cntr=0.3,0.1

Type RM Length L Ch R = 1 ,127087  ,2785,2785,2785
BEGIN DESCRIPTION:
PEDERNALES RIVER 283.0
END DESCRIPTION:
XS GIS Cut Line= 4
      2961730.06     10086278.53       2966832.2      10084336.2
      2966863.35     10081810.49      2971884.47     10077914.82
#Sta/Elev= 30
 -1420.7 1042.77  -969.6 1002.14  -172.1  989.09   576.8 1011.21    1042  980.15
  1584.3  963.48  2217.9  944.01  2808.6  925.86  3630.1  900.62  3941.1  891.06
  4526.4  881.46  4661.2   876.8  4691.2  859.61  4901.2  753.85  5000.9  748.93
  5221.2   767.1  5621.2  864.09  5816.5  908.13  6564.6 1013.04  6674.1 1008.98
  7082.7  993.82  8085.8  956.61  8955.8  929.05    9745  966.39 10477.2  906.52
   10614  895.86 10980.2  964.71 11219.6  994.46 11833.3 1013.66 12919.7 1122.56
#Mann= 19 ,-1 , 0
 -1420.7      .1       0  -172.1     .16       0   576.8     .05       0
    1042      .1       0  1584.3      .1       0  2217.9     .05       0
  2808.6     .05       0  3630.1     .16       0  3941.1      .1       0
  4526.4     .16       0  4661.2     .05       0  5621.2     .16       0
  5816.5     .16       0  6674.1      .1       0  7082.7      .1       0
  8085.8     .05       0  8955.8      .1       0 10477.2     .16       0
 10980.2     .16       0
Bank Sta=4691.2,5621.2
XS Rating Curve= 0 ,0
Exp/Cntr=0.3,0.1

Type RM Length L Ch R = 1 ,124302  ,3384,3384,3384
BEGIN DESCRIPTION:
PEDERNALES RIVER 284.0
END DESCRIPTION:
XS GIS Cut Line= 3
      2962324.77      10086624.4      2966928.33     10084988.44
      2970968.09     10084725.77
#Sta/Elev= 30
 -1458.7 1040.41  -813.7 1012.63  -608.3  973.29  -520.2  981.45  -362.7 1015.22
   391.8 1028.72   538.7  999.66   855.6  944.14  1142.9  923.42    1388  910.28
  2378.7  907.96  2663.8  902.67    2987  895.28  3557.3  865.47  4057.6  880.09
  4409.1  827.27  4739.8  757.74  5050.2  743.85  5121.7  764.96  5180.7  813.19
    5321  831.11  5361.1  845.51  5391.2  899.71  5641.7 1008.41  5888.4 1030.19
  6043.5 1030.78  6444.9 1036.94  6556.2 1041.58  7016.8 1067.81  7475.2  1075.6
#Mann= 17 ,-1 , 0
 -1458.7      .1       0  -520.2     .16       0  -362.7      .1       0
   538.7     .05       0  1142.9     .05       0    1388      .1       0
  2378.7      .1       0  2663.8     .05       0    2987      .1       0
  4057.6     .16       0  4409.1     .05       0    5321     .16       0
  5888.4      .1       0  6043.5     .16       0  6444.9      .1       0
  6556.2     .16       0  7016.8      .1       0
Bank Sta=4409.1,5321
XS Rating Curve= 0 ,0
Exp/Cntr=0.3,0.1

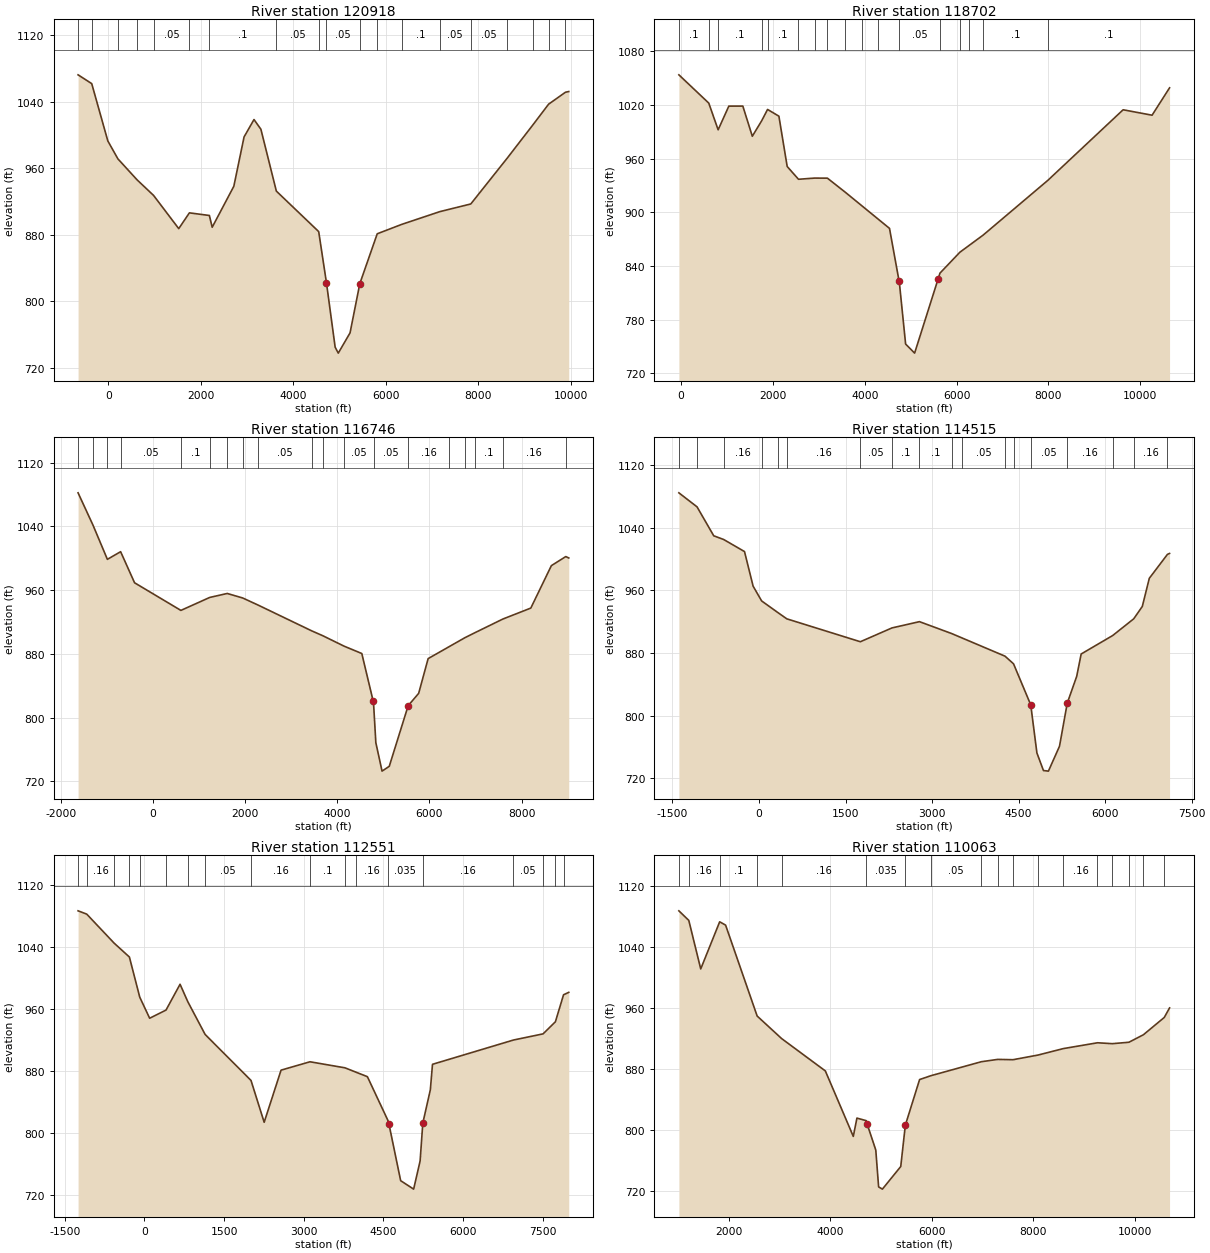
Type RM Length L Ch R = 1 ,120918  ,2216,2216,2216
BEGIN DESCRIPTION:
PEDERNALES RIVER 285.0
END DESCRIPTION:
XS GIS Cut Line= 4
      2960995.19     10088847.66      2964507.45     10087015.91
      2968772.24     10087511.23      2970792.64     10086286.11
#Sta/Elev= 30
  -657.7 1072.56  -362.5 1061.98     -14  993.01   204.4  971.41   622.8  945.96
   975.5  927.46  1520.6  887.45    1751  906.43  2183.5  903.28  2244.5  889.11
    2713  938.47    2934  997.79  3149.2 1018.76  3298.2 1007.06  3632.7  932.61
  4549.1  883.87  4716.9  822.26  4905.2  744.75  4972.5  737.61  5227.4  761.98
  5438.8  821.24  5815.6  881.24  6343.2  892.51  7168.5  907.88    7840  917.14
  8627.5  972.23    9182 1012.17  9523.8 1037.23    9889 1051.62  9959.8 1052.44
#Mann= 19 ,-1 , 0
  -657.7      .1       0  -362.5     .05       0   204.4     .05       0
   622.8     .05       0   975.5     .05       0    1751      .1       0
  2183.5      .1       0  3632.7     .05       0  4549.1     .16       0
  4716.9     .05       0  5438.8     .16       0  5815.6     .05       0
  6343.2      .1       0  7168.5     .05       0    7840     .05       0
  8627.5      .1       0    9182     .16       0  9523.8     .16       0
    9889     .16       0
Bank Sta=4716.9,5438.8
XS Rating Curve= 0 ,0
Exp/Cntr=0.3,0.1

Type RM Length L Ch R = 1 ,118702  ,1956,1956,1956
BEGIN DESCRIPTION:
PEDERNALES RIVER 286.0
END DESCRIPTION:
XS GIS Cut Line= 4
      2961648.17     10090808.83      2964734.44     10089727.09
      2968809.86     10088683.59      2971204.71      10086552.8
#Sta/Elev= 30
   -45.3 1053.73   605.6  1022.1   809.3  992.26  1042.3 1018.73  1347.1 1018.77
  1553.5  985.04    1759 1002.52  1885.5 1015.03  2132.2  1007.5  2312.9  951.23
  2558.9  936.96  2908.4  938.27    3188  938.21  3575.2  922.55  3952.2  906.73
  4292.4  892.45  4540.2  882.05  4745.9  823.93  4751.1  823.42  4891.2  752.73
    5087  742.57  5597.6  825.31  5638.4  831.98  6072.5  855.38  6260.5  862.49
  6579.9  874.57  7986.5   935.7  9626.3 1014.65 10256.8 1008.58 10637.5  1039.2
#Mann= 17 ,-1 , 0
   -45.3      .1       0   605.6     .05       0   809.3      .1       0
    1759     .16       0  1885.5      .1       0  2558.9     .05       0
  2908.4      .1       0    3188     .05       0  3575.2      .1       0
  3952.2      .1       0  4292.4     .16       0  4745.9     .05       0
  5638.4     .16       0  6072.5      .1       0  6260.5     .16       0
  6579.9      .1       0  7986.5      .1       0
Bank Sta=4751.1,5597.6
XS Rating Curve= 0 ,0
Exp/Cntr=0.3,0.1

Type RM Length L Ch R = 1 ,116746  ,2231,2231,2231
BEGIN DESCRIPTION:
PEDERNALES RIVER 287.0
END DESCRIPTION:
XS GIS Cut Line= 2
      2962611.33     10095065.52      2970768.79     10088212.98
#Sta/Elev= 30
 -1629.5 1082.13 -1306.6 1041.71  -993.1  998.66  -705.7 1008.27  -402.7  969.25
   603.1  934.59  1228.1  950.84  1609.4  955.84  1945.7  950.15  2282.2  941.19
  3440.9  908.99    3686  902.75  4148.6  889.66  4531.1  880.49  4779.3   820.4
  4786.1  817.87  4835.6   768.6  4970.6   732.9  5126.9  738.93    5538  815.03
  5765.6  830.51  5971.1  874.09  6425.3  889.02  6767.7  900.28  6996.7  906.88
  7594.1  923.76  8200.6  937.51  8646.8  990.75  8959.7 1002.14  9024.2 1000.38
#Mann= 19 ,-1 , 0
 -1629.5      .1       0 -1306.6      .1       0  -993.1      .1       0
  -705.7     .05       0   603.1      .1       0  1228.1     .16       0
  1609.4      .1       0  1945.7     .05       0  2282.2     .05       0
  3440.9      .1       0    3686     .05       0  4148.6     .05       0
  4786.1     .05       0    5538     .16       0  6425.3      .1       0
  6767.7     .16       0  6996.7      .1       0  7594.1     .16       0
  8959.7     .16       0
Bank Sta=4779.3,5538
XS Rating Curve= 0 ,0
Exp/Cntr=0.3,0.1

Type RM Length L Ch R = 1 ,114515  ,1964,1964,1964
BEGIN DESCRIPTION:
PEDERNALES RIVER 288.0
END DESCRIPTION:
XS GIS Cut Line= 2
      2964685.32      10095820.3      2971287.96       10090459.
#Sta/Elev= 30
 -1388.3 1084.25 -1073.6 1066.36  -784.1 1029.45  -612.4 1024.73  -250.7 1009.33
  -101.7  965.24    45.9  946.38   324.7  931.67   482.4  923.53  1757.4  894.32
  2304.7  911.92  2781.6  919.93  3337.3  904.84  3522.9  899.05  4264.3  875.93
  4412.6  866.16  4710.6  813.81  4817.6  752.47  4931.1  730.04  5017.1  729.29
  5209.1     761  5343.4  815.96  5507.4  850.17  5584.8  878.69  6131.1  902.24
  6495.9  923.58  6644.4  939.33  6765.8  975.24  7080.2 1005.76  7116.9 1006.93
#Mann= 18 ,-1 , 0
 -1388.3      .1       0 -1073.6      .1       0  -612.4     .16       0
    45.9     .05       0   324.7      .1       0   482.4     .16       0
  1757.4     .05       0  2304.7      .1       0  2781.6      .1       0
  3337.3      .1       0  3522.9     .05       0  4264.3      .1       0
  4412.6     .16       0  4710.6     .05       0  5343.4     .16       0
  6131.1      .1       0  6495.9     .16       0  7080.2      .1       0
Bank Sta=4710.6,5343.4
XS Rating Curve= 0 ,0
Exp/Cntr=0.3,0.1

Type RM Length L Ch R = 1 ,112551  ,2488,2488,2488
BEGIN DESCRIPTION:
PEDERNALES RIVER 289.0
END DESCRIPTION:
XS GIS Cut Line= 4
      2965714.96     10096796.53      2968957.78      10093581.3
      2971488.91     10093169.82      2971982.96     10091118.72
#Sta/Elev= 30
 -1249.2  1086.9 -1085.6 1082.62  -569.6 1045.16  -282.8 1027.27   -87.6  975.44
    98.8  948.23   406.8  958.74   671.5  992.11   816.3  969.72  1143.5   927.3
  2007.5  867.94  2255.5   813.9  2573.6  881.22  3118.6  892.01  3776.6  884.22
  3977.9  878.77  4199.5  872.77  4584.7  816.46  4604.7  811.87  4825.8  738.52
  5070.5   727.6  5192.4  764.05    5243   812.8  5384.9  855.84  5425.4  888.75
  6950.3   920.1  7508.1  928.04  7740.4   943.7  7893.3  978.52  7991.5  981.65
#Mann= 18 ,-1 , 0
 -1249.2     .16       0 -1085.6     .16       0  -569.6      .1       0
  -282.8     .16       0   -87.6      .1       0   406.8      .1       0
   816.3     .05       0  1143.5     .05       0  2007.5     .16       0
  3118.6      .1       0  3776.6      .1       0  3977.9     .16       0
  4584.7    .035       0    5243     .16       0  6950.3     .05       0
  7508.1      .1       0  7740.4     .16       0  7893.3      .1       0
Bank Sta=4604.7,5243
XS Rating Curve= 0 ,0
Exp/Cntr=0.3,0.1

Type RM Length L Ch R = 1 ,110063  ,2301,2301,2301
BEGIN DESCRIPTION:
PEDERNALES RIVER 290.0
END DESCRIPTION:
XS GIS Cut Line= 4
      2966517.02     10097223.08      2968618.66     10095738.59
      2971407.92     10095512.58      2972241.11     10091304.12
#Sta/Elev= 30
  1020.8 1087.54  1216.1 1074.96  1451.1  1011.3  1824.1 1073.13  1940.8 1068.79
    2562  949.53  3043.2  919.99  3904.7  877.52  4455.1  791.64  4526.7  815.63
  4709.4  812.27  4727.4  807.85  4897.9  773.75  4953.6   725.4  5028.1  722.45
  5389.5  752.12  5479.8   806.3  5760.7  866.21  5985.2  871.29    6976  889.58
  7297.2  892.63  7599.9  892.24  8092.4  898.33  8589.4  906.79  9263.2  914.44
  9555.4  913.27  9881.8  915.13 10167.9  924.99 10577.7  947.64 10682.4  960.17
#Mann= 18 ,-1 , 0
  1020.8      .1       0  1216.1     .16       0  1824.1      .1       0
    2562     .16       0  3043.2     .16       0  4709.4    .035       0
  5479.8     .16       0  5985.2     .05       0    6976     .16       0
  7297.2     .05       0  7599.9      .1       0  8092.4     .16       0
  8589.4     .16       0  9263.2     .05       0  9555.4     .05       0
  9881.8      .1       0 10167.9     .16       0 10577.7     .16       0
Bank Sta=4727.4,5479.8
XS Rating Curve= 0 ,0
Exp/Cntr=0.3,0.1