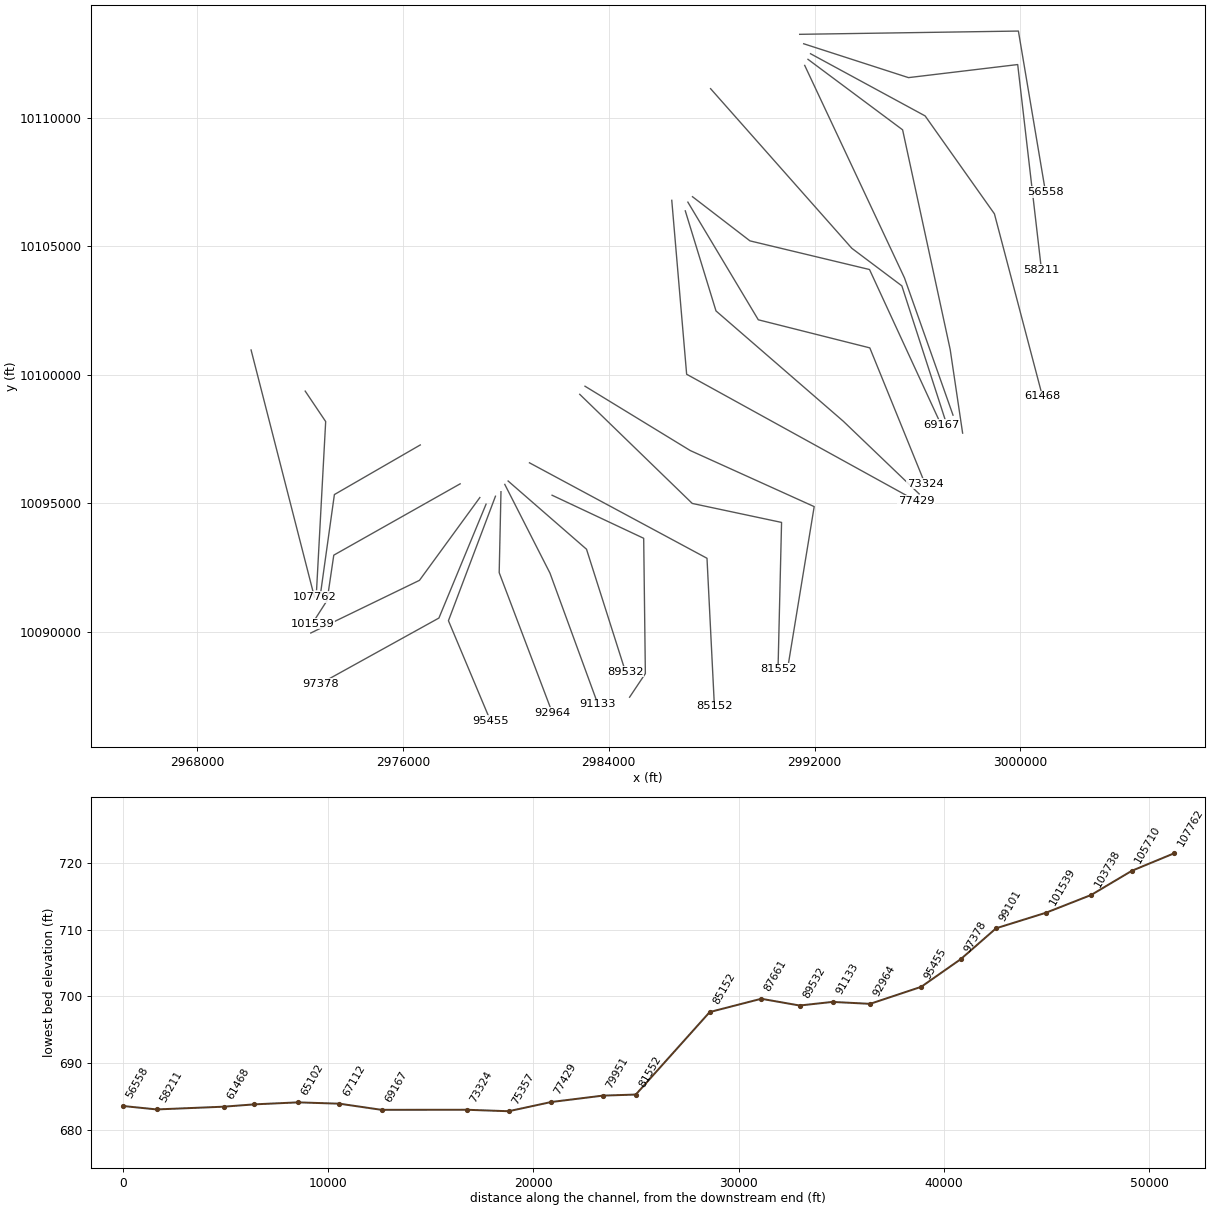
HEC-RAS study PEDERNALES RIVER.prj: PEDERNALES RIVER Base Level Engineering

--- PEDERNALES RIVER.g02 (geometry) --- (continued)

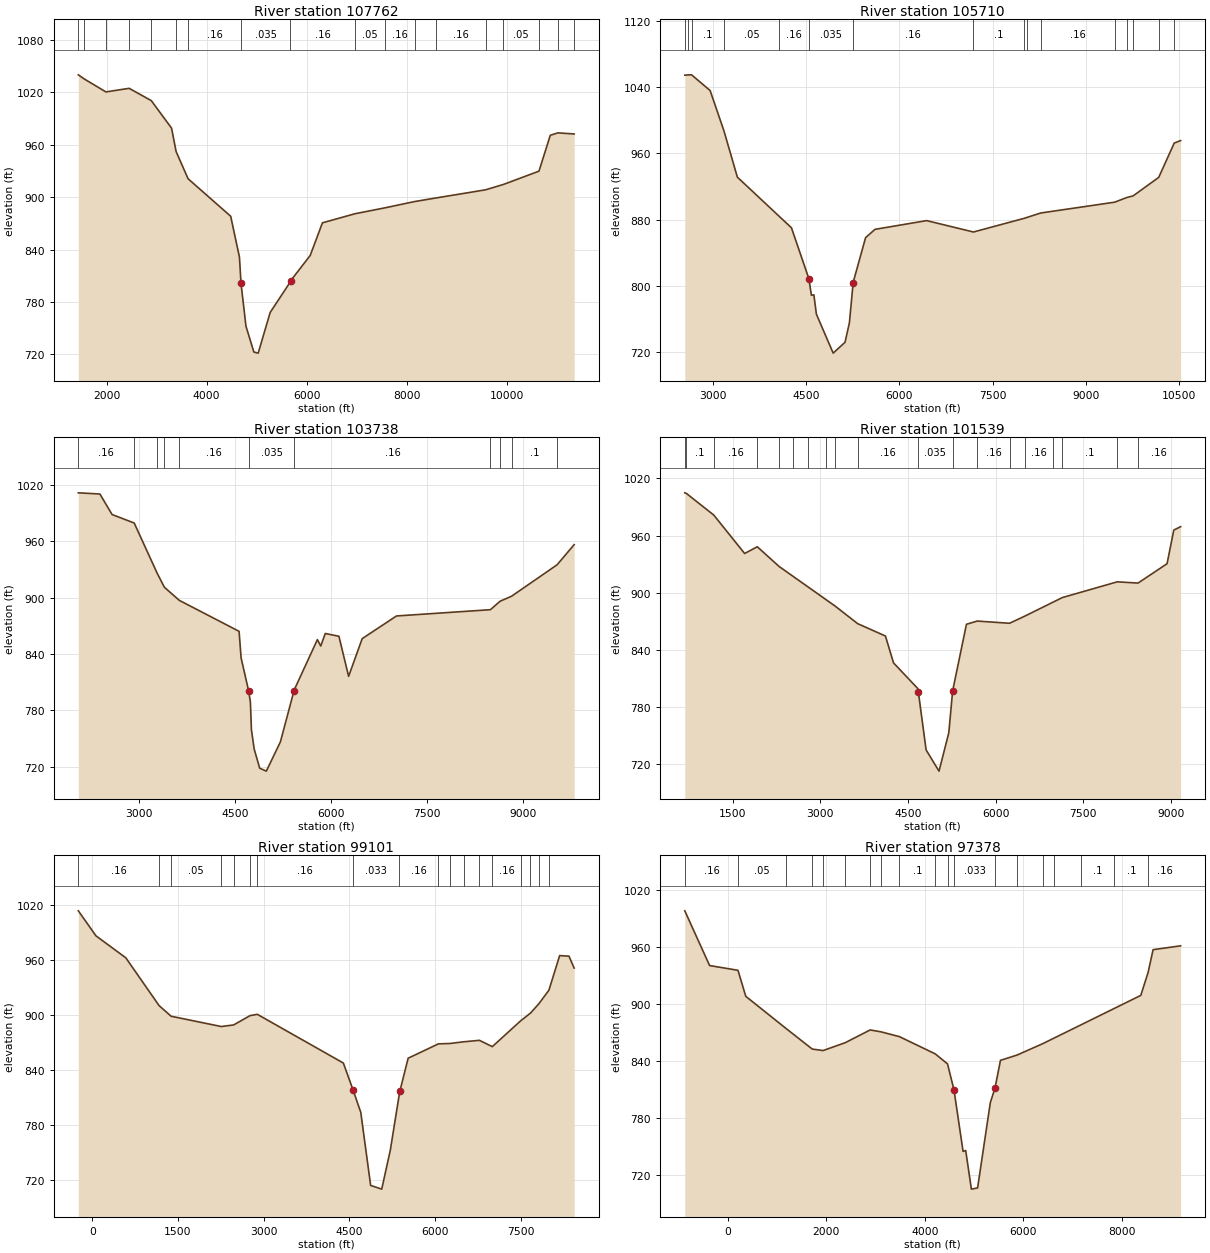
Type RM Length L Ch R = 1 ,107762  ,2052,2052,2052
BEGIN DESCRIPTION:
PEDERNALES RIVER 291.0
END DESCRIPTION:
XS GIS Cut Line= 2
      2970090.64     10100965.07      2972552.92     10091360.05
#Sta/Elev= 30
  1435.6 1039.93  1552.1 1035.28  1987.5 1020.37  2451.8 1024.49  2895.1 1010.38
  3299.9  978.93    3391  952.13  3630.6  920.98  4482.4  878.09  4657.9  831.28
  4688.8  801.42  4788.1  752.23  4946.1  722.68  5032.6  721.43  5272.4  768.03
    5675  802.92  5680.2  804.17  6072.2  833.17  6317.2  870.56  6970.8  880.98
  7573.4  887.78  8159.5  894.88  8578.4  898.91  9581.9  908.36  9936.3  914.47
 10647.5  929.68 10873.9  970.74 11025.4   973.5 11344.9  972.29 11351.2  972.15
#Mann= 18 ,-1 , 0
  1435.6      .1       0  1552.1     .16       0  1987.5     .16       0
  2451.8      .1       0  2895.1     .16       0    3391      .1       0
  3630.6     .16       0  4688.8    .035       0    5675     .16       0
  6970.8     .05       0  7573.4     .16       0  8159.5      .1       0
  8578.4     .16       0  9581.9     .16       0  9936.3     .05       0
 10647.5     .16       0 11025.4      .1       0 11344.9     .16       0
Bank Sta=4688.8,5680.2
XS Rating Curve= 0 ,0
Exp/Cntr=0.3,0.1

Type RM Length L Ch R = 1 ,105710  ,1972,1972,1972
BEGIN DESCRIPTION:
PEDERNALES RIVER 292.0
END DESCRIPTION:
XS GIS Cut Line= 3
      2972195.43     10099365.22      2972991.31     10098181.44
      2972638.06     10091646.83
#Sta/Elev= 30
  2550.7 1054.36    2601 1054.68  2659.5 1054.79  2957.8 1035.84    3179  987.42
    3396  931.26  4071.4  883.75  4265.3  870.15  4545.7  808.57  4585.7  788.72
  4625.8  789.18  4665.9  765.92    4936  718.82  5126.5  731.95  5196.6  755.35
  5246.7  795.52  5256.7  804.04    5457  858.25  5608.3  868.25  6438.4  878.79
  7191.2  865.05  8009.3  881.61  8049.2  882.58  8272.1  887.98  9461.4  901.04
  9658.8  906.74  9757.5  908.64 10169.6  931.02   10418  972.39 10521.3  975.42
#Mann= 16 ,-1 , 0
  2550.7      .1       0    2601     .05       0  2659.5      .1       0
    3179     .05       0  4071.4     .16       0  4545.7    .035       0
  5246.7     .16       0  7191.2      .1       0  8009.3     .16       0
  8049.2      .1       0  8272.1     .16       0  9461.4     .05       0
  9658.8     .16       0  9757.5      .1       0 10169.6     .16       0
   10418      .1       0
Bank Sta=4545.7,5256.7
XS Rating Curve= 0 ,0
Exp/Cntr=0.3,0.1

Type RM Length L Ch R = 1 ,103738  ,2199,2199,2199
BEGIN DESCRIPTION:
PEDERNALES RIVER 293.0
END DESCRIPTION:
XS GIS Cut Line= 3
      2976670.08     10097271.99      2973330.17     10095342.73
      2972791.98     10091496.78
#Sta/Elev= 30
  2054.5 1011.85  2391.3  1010.6  2581.3  988.73  2927.1  979.66  3282.4  926.58
  3397.8  911.22  3631.5  897.21  4564.1  864.22  4595.7  835.87  4712.5  800.99
  4740.7  788.98  4756.5   759.5  4799.6  738.83  4885.7  718.34  4989.4  715.21
  5209.1  746.42  5421.2  800.84  5428.5  802.33  5786.5  855.39    5839  848.53
  5909.7  861.93  6122.6  858.96  6274.1  816.26  6486.1  856.45  7021.3  880.59
  8487.9  887.29  8637.1  896.24  8819.1  901.68  9528.5  935.14    9795  956.63
#Mann= 11 ,-1 , 0
  2054.5     .16       0  2927.1      .1       0  3282.4     .05       0
  3397.8      .1       0  3631.5     .16       0  4712.5    .035       0
  5428.5     .16       0  8487.9      .1       0  8637.1     .16       0
  8819.1      .1       0  9528.5     .16       0
Bank Sta=4712.5,5421.2
XS Rating Curve= 0 ,0
Exp/Cntr=0.3,0.1

Type RM Length L Ch R = 1 ,101539  ,2438,2438,2438
BEGIN DESCRIPTION:
PEDERNALES RIVER 294.0
END DESCRIPTION:
XS GIS Cut Line= 4
      2978220.18     10095759.74      2973306.44     10092986.37
      2973046.06     10091225.33      2972471.27     10090328.59
#Sta/Elev= 30
   680.3 1004.91   706.3 1004.35  1177.5  981.49  1704.8  941.17    1921  948.26
  2294.4  927.57  2537.5  917.02  2783.7  906.34  3103.3  892.47  3251.7  886.03
  3640.5  867.45  4115.3  854.47  4253.4  826.26  4671.2  799.15  4678.3  795.74
  4811.4  734.83  5032.1  712.55  5199.8  752.89  5264.8  796.69  5501.7  866.81
  5686.3  870.19  6239.7  867.88    6503  875.45  6983.4  890.03    7143  894.87
  8082.8   911.4    8439  910.11  8935.9  930.45  9050.9  965.76    9168  969.35
#Mann= 19 ,-1 , 0
   680.3     .16       0   706.3      .1       0  1177.5     .16       0
    1921      .1       0  2294.4     .16       0  2537.5     .05       0
  2783.7      .1       0  3103.3     .16       0  3251.7     .05       0
  3640.5     .16       0  4671.2    .035       0  5264.8     .16       0
  5686.3     .16       0  6239.7      .1       0    6503     .16       0
  6983.4     .16       0    7143      .1       0  8082.8     .05       0
    8439     .16       0
Bank Sta=4678.3,5264.8
XS Rating Curve= 0 ,0
Exp/Cntr=0.3,0.1

Type RM Length L Ch R = 1 ,99101   ,1723,1723,1723
BEGIN DESCRIPTION:
PEDERNALES RIVER 295.0
END DESCRIPTION:
XS GIS Cut Line= 3
      2978986.28     10095226.64      2976638.87     10092007.54
      2972412.01     10089959.45
#Sta/Elev= 30
  -244.2  1013.2    64.3     986   587.3  962.04  1169.5  910.05  1380.6  898.43
  2258.8  887.23  2475.1  888.95  2761.8   899.1  2890.1  900.51  4395.9  847.49
  4565.5  818.21  4700.9  793.81  4873.8  714.24  5067.5  710.21  5218.2  752.65
  5373.8  812.92  5383.9  816.53  5530.4  852.75  6060.6  868.37  6262.5  868.77
  6500.5   870.6  6778.1  872.22  7003.7  865.34  7497.8  893.33  7672.3  901.87
  7817.5   911.9  7994.7  926.79  8182.9  964.46  8346.5  963.81  8436.8  950.89
#Mann= 18 ,-1 , 0
  -244.2     .16       0  1169.5     .05       0  1380.6     .05       0
  2258.8      .1       0  2475.1     .05       0  2761.8     .05       0
  2890.1     .16       0  4565.5    .033       0  5373.8     .16       0
  6060.6      .1       0  6262.5     .16       0  6500.5     .16       0
  6778.1      .1       0  7003.7     .16       0  7497.8     .05       0
  7672.3      .1       0  7817.5     .16       0  7994.7     .16       0
Bank Sta=4565.5,5383.9
XS Rating Curve= 0 ,0
Exp/Cntr=0.3,0.1

Type RM Length L Ch R = 1 ,97378   ,1923,1923,1923
BEGIN DESCRIPTION:
PEDERNALES RIVER 296.0
END DESCRIPTION:
XS GIS Cut Line= 3
      2979228.19     10094969.25      2977394.83     10090541.16
      2972783.04       10087989.
#Sta/Elev= 30
  -869.8  997.71  -366.1  940.26   209.7  935.28   367.9  907.96  1183.5  874.29
  1717.3  852.59  1938.2  851.05  2388.9  859.35  2892.2  872.67  3112.6  870.69
  3486.7  865.63  4212.6  847.58  4462.3   837.1  4593.7  809.81  4778.1  745.21
  4831.9  746.12    4947  705.58    5073  706.83  5331.2  796.35  5427.3  811.94
  5537.3  840.76  5873.5   846.3  6400.4  858.39  6620.5     864  7168.7  877.96
  7849.1  895.29  8385.3  908.95  8534.5  933.18  8634.9  956.93  9193.7  960.98
#Mann= 19 ,-1 , 0
  -869.8     .16       0   209.7     .05       0  1183.5      .1       0
  1717.3     .05       0  1938.2      .1       0  2388.9     .05       0
  2892.2     .16       0  3112.6     .05       0  3486.7      .1       0
  4212.6     .05       0  4462.3     .16       0  4593.7    .033       0
  5427.3     .16       0  5873.5     .16       0  6400.4     .05       0
  6620.5     .16       0  7168.7      .1       0  7849.1      .1       0
  8534.5     .16       0
Bank Sta=4593.7,5427.3
XS Rating Curve= 0 ,0
Exp/Cntr=0.3,0.1

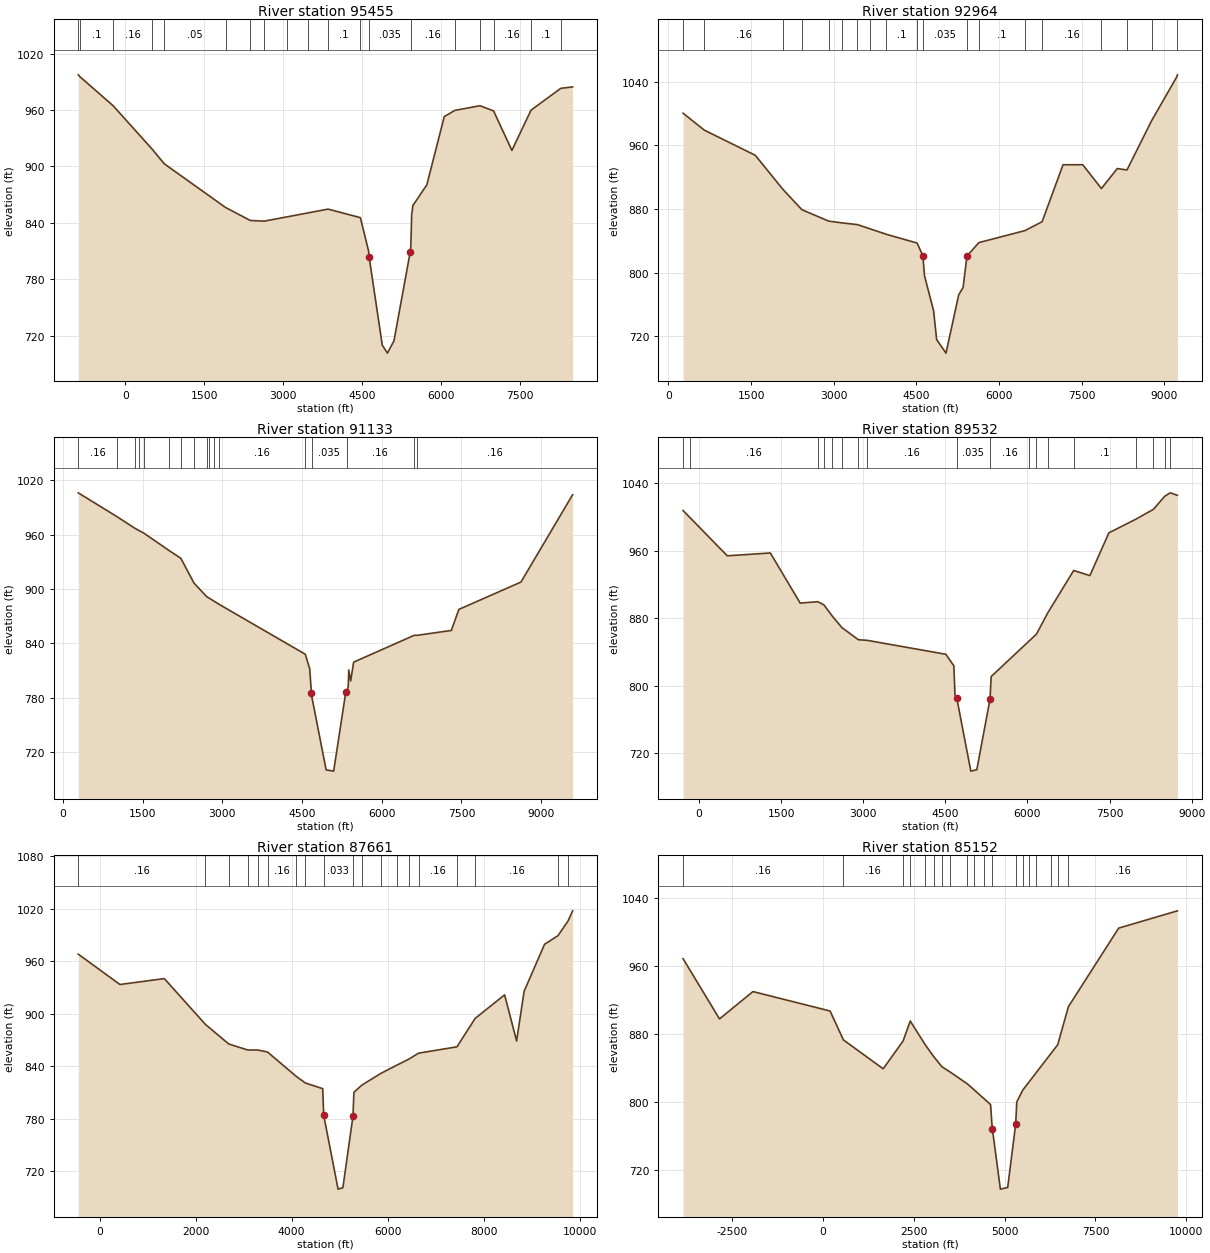
Type RM Length L Ch R = 1 ,95455   ,2491,2491,2491
BEGIN DESCRIPTION:
PEDERNALES RIVER 297.0
END DESCRIPTION:
XS GIS Cut Line= 3
       2979593.3     10095277.54      2977765.04     10090437.22
      2979397.27     10086551.07
#Sta/Elev= 30
  -896.6  997.42  -865.9  995.48  -234.7  964.58     513     918   735.9  902.86
  1901.6  856.32  2372.1  842.49  2639.6  841.85  3063.1  846.31  3474.2  850.64
  3848.9  854.59  4461.7  845.53  4617.5  810.12  4628.4  803.59  4877.8  709.94
  4975.5  701.44    5100  714.51  5406.8  808.61  5420.1  815.06  5435.9  848.14
  5459.7  858.45  5724.4  880.47  6054.9  952.96  6257.7  959.62  6733.1  964.55
  6991.1  959.09  7339.9  917.05  7702.9  959.85  8268.8  983.06  8492.5  984.56
#Mann= 19 ,-1 , 0
  -896.6     .16       0  -865.9      .1       0  -234.7     .16       0
     513      .1       0   735.9     .05       0  1901.6     .05       0
  2372.1     .16       0  2639.6     .05       0  3063.1      .1       0
  3474.2      .1       0  3848.9      .1       0  4461.7      .1       0
  4617.5    .035       0  5420.1     .16       0  6257.7      .1       0
  6733.1     .16       0  6991.1     .16       0  7702.9      .1       0
  8268.8      .1       0
Bank Sta=4628.4,5406.8
XS Rating Curve= 0 ,0
Exp/Cntr=0.3,0.1

Type RM Length L Ch R = 1 ,92964   ,1831,1831,1831
BEGIN DESCRIPTION:
PEDERNALES RIVER 298.0
END DESCRIPTION:
XS GIS Cut Line= 3
      2979808.14     10095453.83      2979738.51     10092306.24
      2981802.31     10086862.91
#Sta/Elev= 30
   265.2 1000.22     650  978.98  1575.6  947.36  2077.2  904.52  2420.9  879.03
  2906.3   864.7  3143.9  862.52  3429.3  860.28  3661.5  854.91  3954.3  848.14
  4512.1  837.11  4615.8  821.21  4646.1  795.94  4810.8  752.15  4865.7     716
  5035.7  698.89  5266.4  772.13  5346.1  781.33  5416.1  820.83  5632.9  837.73
  6465.6   852.7  6779.6  863.92  7159.4  935.48  7517.6   935.5  7855.9  905.59
  8143.4   930.7  8319.4  928.91  8764.6  990.54  9220.5 1045.56    9235 1048.43
#Mann= 19 ,-1 , 0
   265.2     .16       0     650     .16       0  2077.2     .16       0
  2420.9     .05       0  2906.3      .1       0  3143.9     .05       0
  3429.3     .16       0  3661.5     .05       0  3954.3      .1       0
  4512.1     .16       0  4615.8    .035       0  5416.1     .16       0
  5632.9      .1       0  6465.6     .05       0  6779.6     .16       0
  7855.9     .16       0  8319.4      .1       0  8764.6      .1       0
  9220.5      .1       0
Bank Sta=4615.8,5416.1
XS Rating Curve= 0 ,0
Exp/Cntr=0.3,0.1

Type RM Length L Ch R = 1 ,91133   ,1601,1601,1601
BEGIN DESCRIPTION:
PEDERNALES RIVER 299.0
END DESCRIPTION:
XS GIS Cut Line= 3
      2979956.55     10095737.77      2981713.59     10092287.23
      2983577.82     10087188.69
#Sta/Elev= 30
   290.9 1006.08  1021.1  979.74  1356.9  966.97  1441.3  964.25  1519.5  961.83
  1991.1  942.83  2221.8  933.86  2468.4  906.61  2705.6  891.69  2745.3  890.25
  2853.3  886.33  2942.8  883.08  4562.7  828.07  4645.9   811.9  4677.8  785.19
    4684  781.61  4954.7  700.51  5096.2  699.18  5324.7  786.41    5338  787.65
  5369.9   791.7  5380.5  810.75  5416.3  798.61  5472.1  819.35  6608.7  848.87
  6667.5  848.94  7310.4  854.33  7452.4  877.54  8620.4  907.66  9591.7 1003.94
#Mann= 17 ,-1 , 0
   290.9     .16       0  1021.1      .1       0  1356.9     .16       0
  1441.3      .1       0  1519.5     .16       0  1991.1      .1       0
  2221.8      .1       0  2468.4     .05       0  2705.6      .1       0
  2745.3     .05       0  2853.3      .1       0  2942.8     .16       0
  4562.7     .05       0    4684    .035       0    5338     .16       0
  6608.7      .1       0  6667.5     .16       0
Bank Sta=4677.8,5324.7
XS Rating Curve= 0 ,0
Exp/Cntr=0.3,0.1

Type RM Length L Ch R = 1 ,89532   ,1871,1871,1871
BEGIN DESCRIPTION:
PEDERNALES RIVER 300.0
END DESCRIPTION:
XS GIS Cut Line= 3
      2980085.16     10095869.54      2983134.42     10093216.25
       2984647.2     10088460.59
#Sta/Elev= 30
  -292.9  1007.9  -171.7  999.78   514.6  954.15  1301.7   957.5  1846.7  898.03
  2168.5   899.7  2279.5  895.97  2435.8   882.4  2608.1  869.04  2910.2  854.54
  3076.1   853.8  4508.6  837.29  4654.2  823.65  4675.2  789.13  4707.3  785.54
  4964.9  698.64    5074  700.31  5315.3  784.06  5336.3  810.85  6024.6  852.76
  6163.7  861.21  6367.4  886.07  6844.2  936.74  7139.9  930.64  7487.5  981.41
  7985.3  997.76    8302 1009.36  8505.7 1024.69  8607.5 1028.88  8739.6 1025.98
#Mann= 18 ,-1 , 0
  -292.9      .1       0  -171.7     .16       0  2168.5      .1       0
  2279.5      .1       0  2435.8     .16       0  2608.1     .05       0
  2910.2     .16       0  3076.1     .16       0  4707.3    .035       0
  5315.3     .16       0  6024.6     .16       0  6163.7      .1       0
  6367.4     .16       0  6844.2      .1       0  7985.3     .16       0
    8302      .1       0  8505.7     .16       0  8607.5      .1       0
Bank Sta=4707.3,5315.3
XS Rating Curve= 0 ,0
Exp/Cntr=0.3,0.1

Type RM Length L Ch R = 1 ,87661   ,2509,2509,2509
BEGIN DESCRIPTION:
PEDERNALES RIVER 320.0
END DESCRIPTION:
XS GIS Cut Line= 4
      2981795.05      10095316.6      2985357.45     10093641.85
      2985422.46     10088382.18       2984808.8     10087463.12
#Sta/Elev= 30
  -446.8  967.96   421.1   933.3  1347.1  940.02  2203.7   887.7  2689.2  865.38
  3084.1  858.53  3296.2  858.46  3498.3  856.17    4088  828.75  4284.6  820.87
  4647.8  814.34  4667.8  784.07  4967.6  699.65  5067.9  701.26  5277.9  782.83
  5297.9  810.33  5464.1  818.44  5856.3  831.71  6193.1  841.21    6447   848.2
  6643.6  854.87    7445  862.13  7823.1  894.52  8438.1  921.48  8688.1  868.81
    8844  925.44  9270.5  979.21  9549.4  989.02    9761 1005.88  9854.8 1017.41
#Mann= 19 ,-1 , 0
  -446.8     .16       0  2203.7     .05       0  2689.2     .16       0
  3084.1     .05       0  3296.2     .16       0  3498.3     .16       0
    4088     .05       0  4284.6     .16       0  4667.8    .033       0
  5277.9     .16       0  5464.1      .1       0  5856.3     .05       0
  6193.1      .1       0    6447     .05       0  6643.6     .16       0
    7445      .1       0  7823.1     .16       0  9549.4      .1       0
    9761     .16       0
Bank Sta=4667.8,5277.9
XS Rating Curve= 0 ,0
Exp/Cntr=0.3,0.1

Type RM Length L Ch R = 1 ,85152   ,3600,3600,3600
BEGIN DESCRIPTION:
PEDERNALES RIVER 301.0
END DESCRIPTION:
XS GIS Cut Line= 3
      2980915.77     10096577.44      2987819.33     10092864.99
      2988107.51     10087108.96
#Sta/Elev= 30
   -3847   968.9 -2844.8  898.07 -1923.9  930.25   198.2  907.36   564.3  873.34
  1659.1  839.32    2207  872.11  2403.5  895.58  2814.5  867.72  3043.8  854.01
  3273.1  841.81  3502.4   835.5  3974.1   821.6  4161.7  814.56  4431.6   804.2
  4613.5  797.21  4653.5  772.59  4663.6  768.37  4883.6  697.66  5084.1  699.57
  5304.4  774.16  5334.4  800.29  5496.8   814.1  5667.4  823.58  5871.1   834.9
  6264.1  856.74  6460.6  867.65  6755.4  912.49  8137.9 1004.93  9754.7 1025.31
#Mann= 19 ,-1 , 0
   -3847     .16       0   564.3     .16       0    2207      .1       0
  2403.5     .16       0  2814.5     .16       0  3043.8     .05       0
  3273.1     .05       0  3502.4     .16       0  3974.1     .05       0
  4161.7     .05       0  4431.6     .16       0  4653.5    .033       0
  5304.4     .16       0  5496.8      .1       0  5667.4     .05       0
  5871.1     .16       0  6264.1     .05       0  6460.6      .1       0
  6755.4     .16       0
Bank Sta=4663.6,5304.4
XS Rating Curve= 0 ,0
Exp/Cntr=0.3,0.1

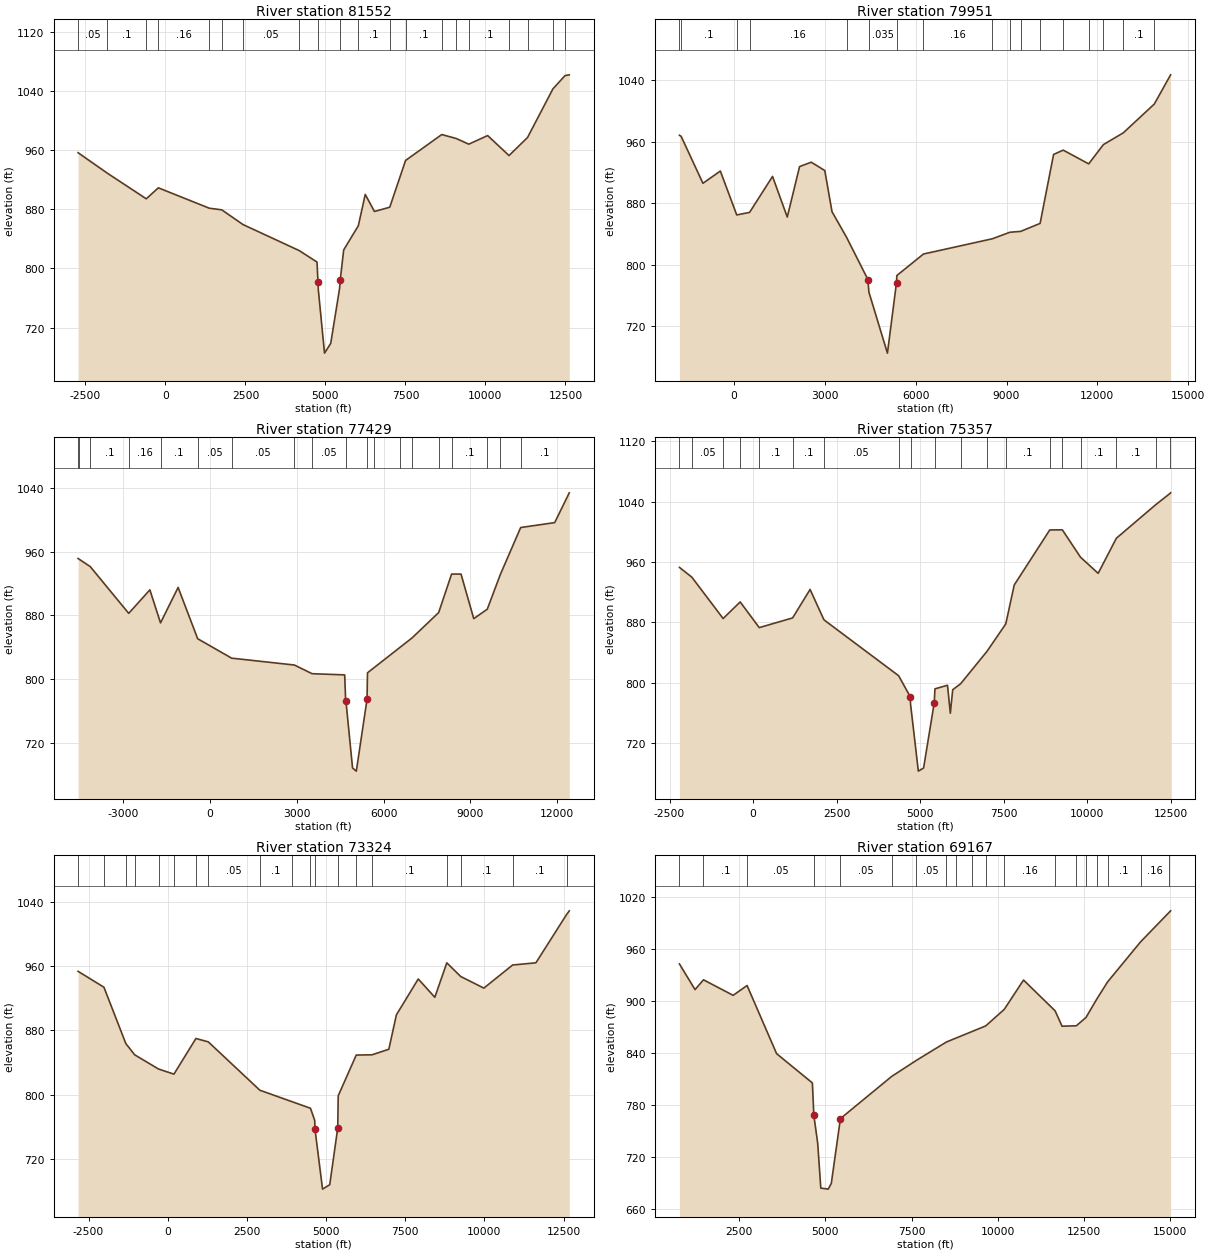
Type RM Length L Ch R = 1 ,81552   ,1601,1601,1601
BEGIN DESCRIPTION:
PEDERNALES RIVER 302.0
END DESCRIPTION:
XS GIS Cut Line= 4
      2982870.73     10099240.47      2987246.08     10094997.67
      2990718.78     10094259.36        2990581.     10088554.41
#Sta/Elev= 30
 -2730.4  956.69 -1816.2  928.95  -599.4  894.28  -222.3  909.15  1367.3  881.57
  1761.7   879.3  2425.6  859.36  4179.3  824.19  4736.7  808.65  4767.3  781.68
  4777.6  771.28  4971.6   685.3  5166.1   698.6  5442.1  772.82  5462.5  784.31
  5570.5     825  6028.6  857.83  6244.5  900.19  6531.9   877.1  7010.8  882.89
  7504.5  946.18  8636.7   981.3  9087.4  975.95  9481.3  968.28 10071.1   979.9
   10738  952.85 11316.9  977.29 12111.3 1043.19 12488.1  1061.1 12621.2 1062.16
#Mann= 20 ,-1 , 0
 -2730.4     .05       0 -1816.2      .1       0  -599.4      .1       0
  -222.3     .16       0  1367.3     .16       0  1761.7     .16       0
  2425.6     .05       0  4179.3     .16       0  4777.6    .035       0
  5442.1      .1       0  6028.6      .1       0  7010.8     .16       0
  7504.5      .1       0  8636.7     .05       0  9087.4     .16       0
  9481.3      .1       0   10738     .16       0 11316.9     .16       0
 12111.3     .16       0 12488.1      .1       0
Bank Sta=4767.3,5462.5
XS Rating Curve= 0 ,0
Exp/Cntr=0.3,0.1

Type RM Length L Ch R = 1 ,79951   ,2522,2522,2522
BEGIN DESCRIPTION:
PEDERNALES RIVER 303.0
END DESCRIPTION:
XS GIS Cut Line= 4
      2983075.13     10099555.52      2987168.58     10097054.02
      2991987.23     10094874.01      2990994.39     10088819.99
#Sta/Elev= 30
 -1802.4  968.12 -1745.4  966.68 -1026.6  905.72  -451.8  921.65    89.9  864.63
   513.5  867.89    1272  914.64  1758.4  861.85  2164.9  927.45    2550  933.15
  2997.6  922.31  3236.2  868.83  3716.2  835.64  4421.6  780.73  4454.5  764.38
  5066.5  685.14    5366  776.72  5376.5   785.9    6256  813.85  8532.3  833.67
  9112.4  842.15  9465.2  843.25 10108.4  853.61 10553.9  943.19 10871.3  948.81
 11713.9  930.94   12198  955.95 12857.6  971.32 13880.2 1008.68 14418.6 1046.61
#Mann= 17 ,-1 , 0
 -1802.4     .05       0 -1745.4      .1       0    89.9      .1       0
   513.5     .16       0  3716.2     .16       0  4454.5    .035       0
  5376.5     .05       0    6256     .16       0  8532.3      .1       0
  9112.4      .1       0  9465.2     .05       0 10108.4     .16       0
 10871.3      .1       0 11713.9      .1       0   12198     .05       0
 12857.6      .1       0 13880.2     .16       0
Bank Sta=4421.6,5366
XS Rating Curve= 0 ,0
Exp/Cntr=0.3,0.1

Type RM Length L Ch R = 1 ,77429   ,2072,2072,2072
BEGIN DESCRIPTION:
PEDERNALES RIVER 304.0
END DESCRIPTION:
XS GIS Cut Line= 3
      2986449.34     10106784.64      2987027.73     10100021.03
      2995942.75     10095105.22
#Sta/Elev= 30
 -4554.1   951.6 -4533.8  951.11 -4133.3  941.37 -2805.4  882.61 -2074.2  912.16
 -1706.7  870.61 -1098.8  915.21  -423.2  850.69   749.8  826.26  2918.8  817.62
  3529.6  806.71    4656  805.21  4690.2  772.17  4699.7  772.14  4927.8  688.13
  5058.2  684.18  5427.5  774.41  5443.6  807.81  5685.6  814.71  6582.6  840.28
  6984.3  851.73  7902.2  883.54  8349.6     932  8674.8     932  9114.9  875.94
  9582.6  887.85 10036.7  931.76 10736.5  990.54 11911.7  996.72 12414.7 1034.18
#Mann= 19 ,-1 , 0
 -4554.1      .1       0 -4533.8     .16       0 -4133.3      .1       0
 -2805.4     .16       0 -1706.7      .1       0  -423.2     .05       0
   749.8     .05       0  2918.8     .05       0  3529.6     .05       0
  4690.2    .035       0  5443.6     .16       0  5685.6     .16       0
  6582.6     .05       0  6984.3     .05       0  7902.2      .1       0
  8349.6      .1       0  9582.6     .16       0 10036.7      .1       0
 10736.5      .1       0
Bank Sta=4699.7,5427.5
XS Rating Curve= 0 ,0
Exp/Cntr=0.3,0.1

Type RM Length L Ch R = 1 ,75357   ,2033,2033,2033
BEGIN DESCRIPTION:
PEDERNALES RIVER 305.0
END DESCRIPTION:
XS GIS Cut Line= 4
      2986975.23     10106374.53      2988169.17     10102483.05
      2993118.02      10098195.3      2996068.88       10095368.
#Sta/Elev= 30
 -2203.6  952.71 -1832.5  939.77  -895.5  884.96  -384.9  906.97   185.5  872.91
  1184.5  885.77  1707.6  923.48  2123.8   883.2  4358.5   809.2    4709  781.16
  4715.7  771.56    4949   682.8    5106  686.93  5425.2   773.5    5446   791.8
  5822.1  796.56  5906.6  759.51  5977.9  790.67  6212.9  798.46  7006.6  841.63
  7566.5  877.83  7820.4  929.44  8883.1 1002.31  9259.4 1002.47  9804.3   966.2
   10333  944.84   10877  991.31 12057.7 1035.83 12489.2 1050.88 12501.6 1051.49
#Mann= 19 ,-1 , 0
 -2203.6     .16       0 -1832.5     .05       0  -895.5      .1       0
  -384.9      .1       0   185.5      .1       0  1184.5      .1       0
  2123.8     .05       0  4358.5     .05       0  4715.7    .033       0
    5446     .16       0  6212.9      .1       0  7006.6     .05       0
  7566.5      .1       0  8883.1     .05       0  9259.4      .1       0
  9804.3      .1       0   10877      .1       0 12057.7      .1       0
 12489.2      .1       0
Bank Sta=4709,5425.2
XS Rating Curve= 0 ,0
Exp/Cntr=0.3,0.1

Type RM Length L Ch R = 1 ,73324   ,4157,4157,4157
BEGIN DESCRIPTION:
PEDERNALES RIVER 306.0
END DESCRIPTION:
XS GIS Cut Line= 4
      2987075.22     10106714.25      2989814.04     10102138.81
      2994150.46     10101046.62      2996299.19     10095760.73
#Sta/Elev= 30
 -2831.2  953.41 -2015.9  933.74 -1323.5  863.73 -1044.3  849.78  -291.8  832.16
     195  825.79   890.4  870.08  1280.6  865.84  2907.7  805.83  3924.6  791.58
  4507.4  783.41  4640.5  768.35  4650.8   757.2  4887.8  683.02  5114.9  688.53
  5367.6  758.89    5383  798.91  5951.7  849.47    6452  849.79  6981.4  856.72
  7219.7  899.36  7910.3  943.92  8433.6  921.24    8812  963.99    9250  947.05
  9982.2   932.6 10889.7  961.28 11625.8  964.02 12592.9 1023.88 12679.1 1028.56
#Mann= 19 ,-1 , 0
 -2831.2     .16       0 -2015.9     .05       0 -1323.5      .1       0
 -1044.3      .1       0  -291.8     .05       0     195     .05       0
   890.4      .1       0  1280.6     .05       0  2907.7      .1       0
  3924.6     .05       0  4507.4     .05       0  4640.5    .033       0
  5367.6     .16       0  5951.7     .05       0    6452      .1       0
    8812     .05       0    9250      .1       0 10889.7      .1       0
 12592.9     .16       0
Bank Sta=4650.8,5367.6
XS Rating Curve= 0 ,0
Exp/Cntr=0.3,0.1

Type RM Length L Ch R = 1 ,69167   ,2055,2055,2055
BEGIN DESCRIPTION:
PEDERNALES RIVER 307.0
END DESCRIPTION:
XS GIS Cut Line= 4
      2987254.86     10106924.86      2989489.64      10105207.7
       2994138.8     10104093.33      2996921.81     10098060.04
#Sta/Elev= 30
   770.1  942.45  1222.8  912.85  1467.6  924.15  2327.5  906.27  2731.5  917.59
  3587.6  839.07  4625.8  805.33    4667   768.3  4780.1  735.68  4869.3  684.19
  5084.2  683.01  5173.7  689.56  5438.2  764.26  6921.8  812.76    7630  831.07
  8511.5  852.49  8783.9  856.92  9249.9   864.5  9652.5  871.06 10189.2  890.09
 10748.5  923.89 11663.4  888.44 11865.7  870.71 12279.6  871.18 12560.2  880.79
 12874.4  902.08 13187.9  921.82 14141.4  967.84 14959.8 1001.42 15013.5 1003.62
#Mann= 19 ,-1 , 0
   770.1      .1       0  1467.6      .1       0  2731.5     .05       0
    4667    .033       0  5438.2     .05       0  6921.8     .05       0
    7630     .05       0  8511.5      .1       0  8783.9     .05       0
  9249.9     .05       0  9652.5     .16       0 10189.2     .16       0
 11663.4      .1       0 12279.6     .16       0 12560.2      .1       0
 12874.4     .16       0 13187.9      .1       0 14141.4     .16       0
 14959.8      .1       0
Bank Sta=4667,5438.2
XS Rating Curve= 0 ,0
Exp/Cntr=0.3,0.1

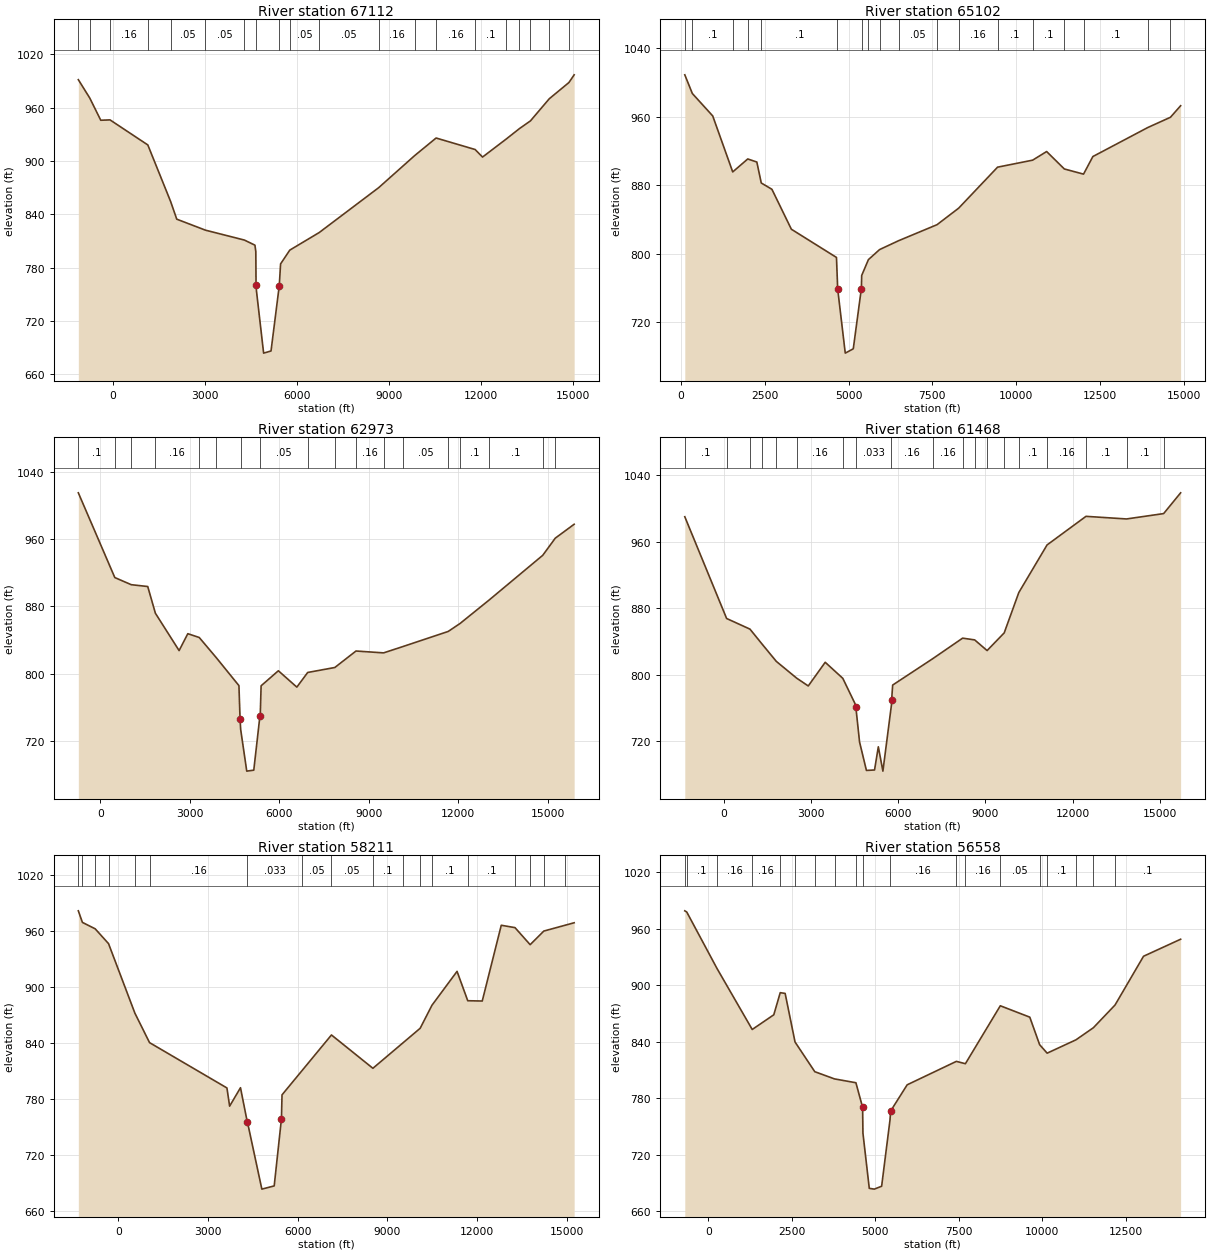
Type RM Length L Ch R = 1 ,67112   ,2010,2010,2010
BEGIN DESCRIPTION:
PEDERNALES RIVER 308.0
END DESCRIPTION:
XS GIS Cut Line= 4
      2987958.15     10111126.17      2993451.52     10104918.16
      2995396.66     10103457.86      2997075.45     10098270.27
#Sta/Elev= 30
 -1130.1  991.34  -759.3  970.84  -398.4  945.74   -95.3  946.13  1136.7  917.98
  1880.7  854.39  2080.8  834.52    3018  822.15  4285.5  811.06  4631.1  805.31
  4659.5     798  4667.1  760.39  4681.3  753.74  4914.4  683.93  5155.6  686.35
  5424.9  759.78  5467.6  784.24    5767  799.71  6728.4  819.52  8667.8  869.95
  9843.6  906.06 10540.9  925.76 11813.9  912.83 12055.6  904.34 12832.8  924.74
 13258.7  936.33 13618.5  945.02 14232.9  969.91 14874.2  988.17 15044.2   996.8
#Mann= 20 ,-1 , 0
 -1130.1     .16       0  -759.3      .1       0   -95.3     .16       0
  1136.7      .1       0  1880.7     .05       0    3018     .05       0
  4285.5     .16       0  4681.3    .033       0  5424.9     .05       0
    5767     .05       0  6728.4     .05       0  8667.8     .16       0
  9843.6      .1       0 10540.9     .16       0 11813.9      .1       0
 12832.8      .1       0 13258.7     .16       0 13618.5      .1       0
 14232.9     .16       0 14874.2      .1       0
Bank Sta=4667.1,5424.9
XS Rating Curve= 0 ,0
Exp/Cntr=0.3,0.1

Type RM Length L Ch R = 1 ,65102   ,2129,2129,2129
BEGIN DESCRIPTION:
PEDERNALES RIVER 309.0
END DESCRIPTION:
XS GIS Cut Line= 3
      2991618.75     10112030.85      2995496.94      10103771.6
      2997385.97     10098430.36
#Sta/Elev= 30
   116.7 1008.61   341.8  986.83   949.4   960.7    1546  895.39  1994.9  910.52
  2265.5  906.92  2398.1  882.49  2715.5  875.15  3295.2   828.6  4641.3  795.69
  4669.6  766.75  4676.2  759.22    4903  684.13  5142.4  689.17  5383.2  759.31
  5393.3  774.64  5593.6  793.14  5926.3  804.84  6495.2  815.22  7639.7  833.87
  8286.1  853.15  9446.4  900.95 10491.9  909.11 10909.9  919.17 11437.5  898.85
 12010.6  892.84 12289.1  913.34 13927.3  947.16 14603.1  959.12 14906.6  972.57
#Mann= 18 ,-1 , 0
   116.7     .05       0   341.8      .1       0    1546     .16       0
  1994.9      .1       0  2398.1      .1       0  4669.6    .033       0
  5393.3     .16       0  5593.6     .05       0  5926.3     .16       0
  6495.2     .05       0  7639.7     .05       0  8286.1     .16       0
  9446.4      .1       0 10491.9      .1       0 11437.5     .16       0
 12010.6      .1       0 13927.3      .1       0 14603.1     .16       0
Bank Sta=4676.2,5383.2
XS Rating Curve= 0 ,0
Exp/Cntr=0.3,0.1

Type RM Length L Ch R = 1 ,62973   ,1505,1505,1505
BEGIN DESCRIPTION:
PEDERNALES RIVER 310.0
END DESCRIPTION:
XS GIS Cut Line= 4
      2991746.05     10112266.76      2995425.74     10109525.87
      2997276.26     10100981.13      2997759.19     10097731.86
#Sta/Elev= 30
  -732.7 1015.06   489.9  914.21    1041  905.72  1593.4  903.54  1849.7  871.75
  2644.4   827.3  2936.3   847.4  3319.6  842.87  3886.5  819.02  4649.4   785.6
  4686.6  746.45    4707  733.63  4911.4  683.83    5147  684.98  5351.6  749.04
  5361.9  747.79  5392.6  785.39  5970.8  803.28    6590  783.82  6953.9  801.25
    7863  807.16  8572.2  826.78  9497.5  824.57 10146.6  832.11 11663.4  850.09
 12061.6   859.6 13038.2   887.6 14831.5  940.72 15250.1  961.09 15883.4  977.66
#Mann= 18 ,-1 , 0
  -732.7      .1       0   489.9      .1       0    1041      .1       0
  1849.7     .16       0  3319.6     .05       0  3886.5      .1       0
    4707    .033       0  5361.9     .05       0  6953.9     .05       0
    7863      .1       0  8572.2     .16       0  9497.5     .05       0
 10146.6     .05       0 11663.4      .1       0 12061.6      .1       0
 13038.2      .1       0 14831.5      .1       0 15250.1      .1       0
Bank Sta=4686.6,5351.6
XS Rating Curve= 0 ,0
Exp/Cntr=0.3,0.1

Type RM Length L Ch R = 1 ,61468   ,3257,3257,3257
BEGIN DESCRIPTION:
PEDERNALES RIVER 311.0
END DESCRIPTION:
XS GIS Cut Line= 4
      2991844.61       10112485.      2996301.56     10110066.22
      2998996.23     10106258.47      3000863.52     10099163.76
#Sta/Elev= 30
 -1352.4  990.27    87.6  867.56   892.1  854.72  1298.9  837.11  1798.4  815.84
  2501.1  795.56  2898.6   786.2  3482.3  814.74  4088.5  795.37  4529.8  763.31
  4535.9  761.14  4664.9  718.64  4901.4  684.33  5180.8  684.84  5311.3  712.82
  5468.6  683.48    5763  763.35  5769.1  768.99  5804.8  787.27  7181.2     819
  8213.7  843.85  8628.6  841.74  9056.5  828.89  9645.3  850.19 10148.1  898.83
 11120.3  956.22   12461  990.74 13856.6  987.59   15135  994.06 15719.7  1019.1
#Mann= 19 ,-1 , 0
 -1352.4      .1       0    87.6     .16       0   892.1      .1       0
  1298.9     .05       0  1798.4     .16       0  2501.1     .16       0
  4088.5     .16       0  4529.8    .033       0    5763     .16       0
  7181.2     .16       0  8213.7      .1       0  8628.6     .05       0
  9056.5     .16       0  9645.3      .1       0 10148.1      .1       0
 11120.3     .16       0   12461      .1       0 13856.6      .1       0
   15135     .16       0
Bank Sta=4535.9,5769.1
XS Rating Curve= 0 ,0
Exp/Cntr=0.3,0.1

Type RM Length L Ch R = 1 ,58211   ,1653,1653,1653
BEGIN DESCRIPTION:
PEDERNALES RIVER 312.0
END DESCRIPTION:
XS GIS Cut Line= 4
      2991579.46     10112872.32       2995653.8     10111555.57
      2999900.91     10112063.86      3000824.29      10104089.3
#Sta/Elev= 30
   -1335  981.14 -1198.6  968.77  -771.1  961.87  -324.5  946.01   556.7  871.59
  1047.1  839.99  3636.4  791.43  3726.4  771.93  4089.6  791.69    4318  754.86
  4323.1  754.84  4804.4  683.07  5217.6  686.52  5459.3  758.14  5479.4  784.06
  6144.2  809.84  7133.1  848.19  8519.1  812.49  9509.9  839.33 10100.9  855.35
 10494.9  879.98 11334.7  916.31 11692.1  884.86 12177.3  884.52 12813.6  965.67
 13272.5  963.16 13780.1  944.88   14238  959.48 14944.9  965.66 15252.1  968.35
#Mann= 18 ,-1 , 0
   -1335      .1       0 -1198.6     .16       0  -771.1     .16       0
  -324.5      .1       0   556.7     .05       0  1047.1     .16       0
  4323.1    .033       0  6144.2     .05       0  7133.1     .05       0
  8519.1      .1       0  9509.9     .16       0 10100.9     .16       0
 10494.9      .1       0 11692.1      .1       0 13272.5     .16       0
 13780.1     .16       0   14238     .05       0 14944.9     .16       0
Bank Sta=4318,5459.3
XS Rating Curve= 0 ,0
Exp/Cntr=0.3,0.1

Type RM Length L Ch R = 1 ,56558   ,1997,1997,1997
BEGIN DESCRIPTION:
PEDERNALES RIVER 313.0
END DESCRIPTION:
XS GIS Cut Line= 3
      2991422.98     10113239.31      2999928.19     10113366.26
      3000982.13     10107108.25
#Sta/Elev= 30
  -701.9  979.02  -643.8  977.79   263.6  917.78  1318.1  853.06  1963.9  868.66
  2156.9  892.13  2303.9  891.36  2600.4  839.76  3192.3  808.24  3783.5  800.59
  4423.8  796.53  4624.4  770.41  4634.2  743.04  4824.2  684.44    4974  683.59
  5194.2  686.67  5444.3  756.81  5464.3  766.52  5959.5  794.33  7433.8  819.22
  7703.2  816.72  8749.2  878.23  9632.2  866.14  9926.9  836.92 10152.5  827.92
 11015.9  842.09 11538.1  854.95 12185.8  879.03 13039.5  930.79 14150.4  948.87
#Mann= 19 ,-1 , 0
  -701.9     .16       0  -643.8      .1       0   263.6     .16       0
  1318.1     .16       0  2156.9     .05       0  2600.4     .05       0
  3192.3     .16       0  3783.5      .1       0  4423.8     .16       0
  4634.2    .033       0  5444.3     .16       0  7433.8      .1       0
  7703.2     .16       0  8749.2     .05       0  9926.9     .05       0
 10152.5      .1       0 11015.9     .16       0 11538.1      .1       0
 12185.8      .1       0
Bank Sta=4624.4,5464.3
XS Rating Curve= 0 ,0
Exp/Cntr=0.3,0.1