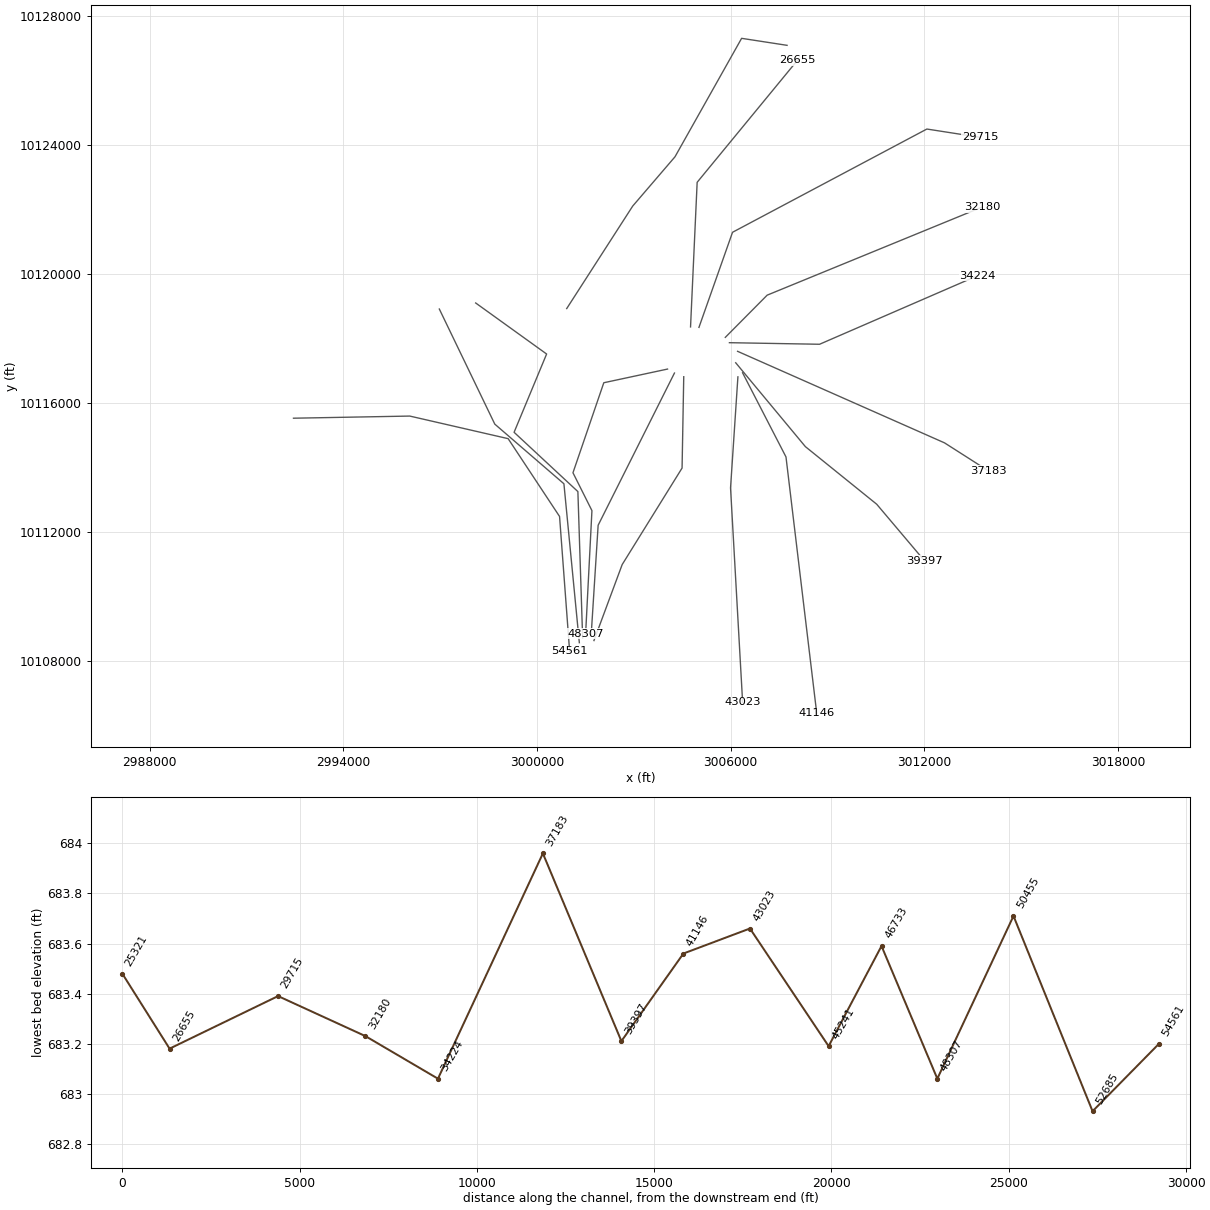
HEC-RAS study PEDERNALES RIVER.prj: PEDERNALES RIVER Base Level Engineering

--- PEDERNALES RIVER.g02 (geometry) --- (continued)

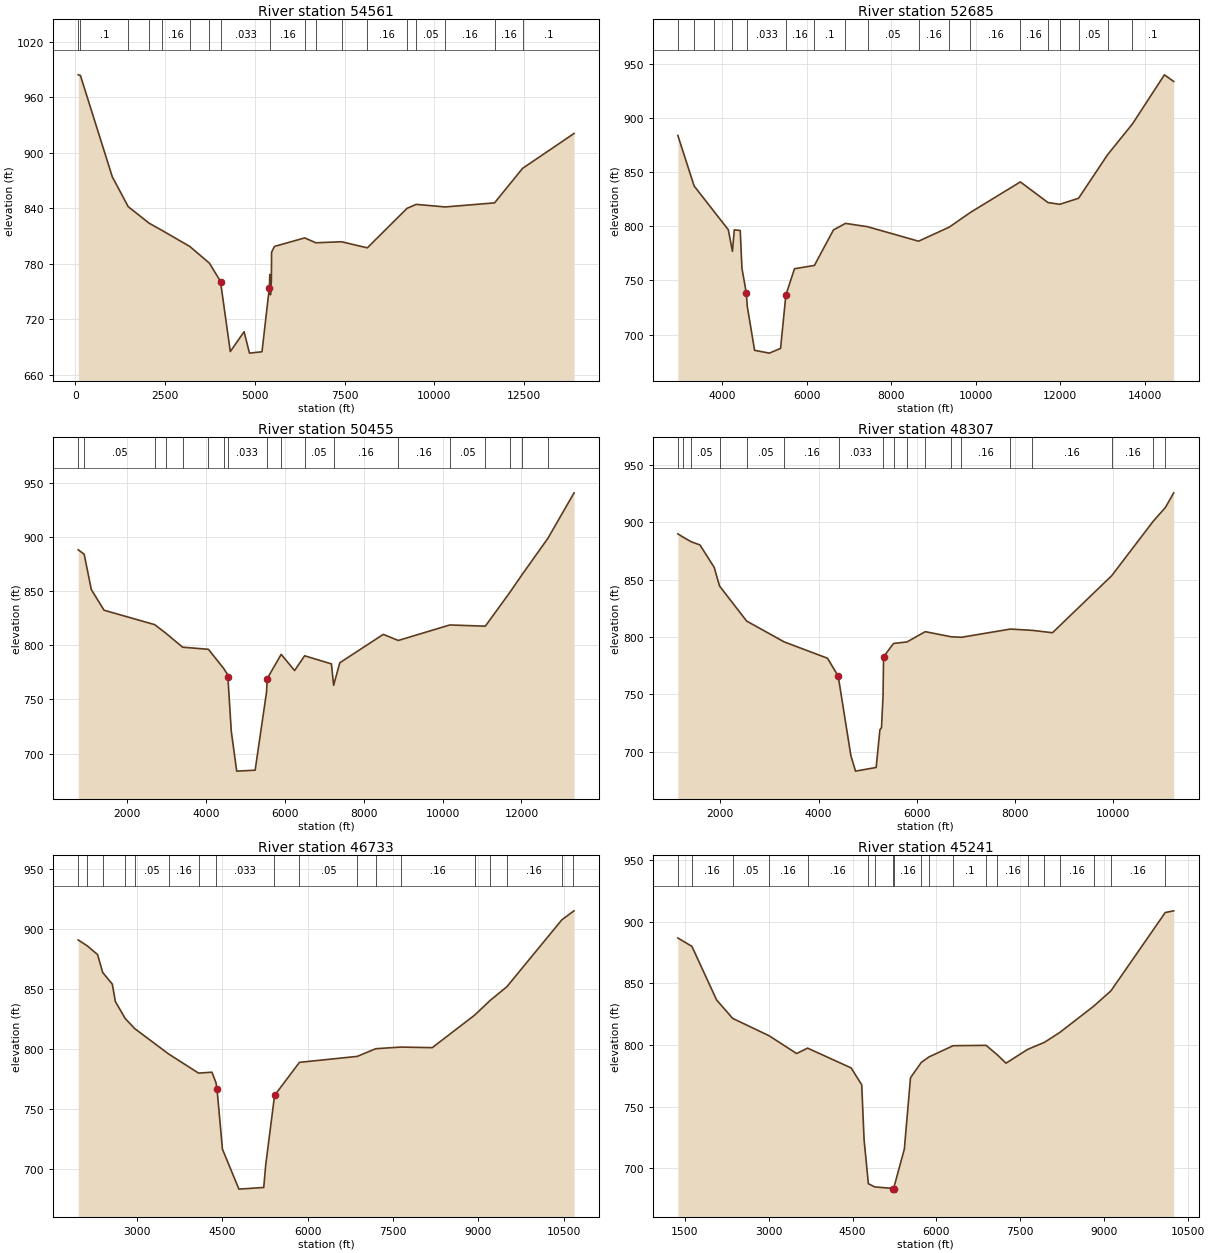
Type RM Length L Ch R = 1 ,54561   ,1876,1876,1876
BEGIN DESCRIPTION:
PEDERNALES RIVER 314.0
END DESCRIPTION:
XS GIS Cut Line= 5
      2992458.01     10115530.71      2996059.51     10115596.97
      2999106.31     10114896.85      3000698.62     10112486.06
      3001010.85     10108301.59
#Sta/Elev= 30
    79.2  984.54   140.4   983.9  1029.8  874.04  1472.1  841.79  2052.7  823.96
  2421.2  815.92  3185.8  798.76  3734.5  780.62  4049.6  760.47  4059.9   756.2
  4316.4   684.9  4700.8   706.4  4849.7   683.2  5198.8  684.67    5404  754.21
  5417.2  768.41  5434.8  746.39    5460  760.97  5465.6  792.39  5545.7  798.74
  6389.9  807.97  6696.7  802.69    7414  803.79  8133.1   797.2  9239.9  839.99
  9495.3  844.27 10301.9  841.49 11677.9   845.9 12456.1   883.2 13892.8  921.06
#Mann= 18 ,-1 , 0
    79.2     .16       0   140.4      .1       0  1472.1     .05       0
  2052.7      .1       0  2421.2     .16       0  3185.8     .05       0
  3734.5     .16       0  4059.9    .033       0  5434.8     .16       0
  6389.9     .16       0  6696.7     .05       0    7414     .16       0
  8133.1     .16       0  9239.9      .1       0  9495.3     .05       0
 10301.9     .16       0 11677.9     .16       0 12456.1      .1       0
Bank Sta=4049.6,5404
XS Rating Curve= 0 ,0
Exp/Cntr=0.3,0.1

Type RM Length L Ch R = 1 ,52685   ,2230,2230,2230
BEGIN DESCRIPTION:
PEDERNALES RIVER 315.0
END DESCRIPTION:
XS GIS Cut Line= 4
      2996974.94     10118913.86      2998692.75     10115347.45
      3000833.65       10113499.      3001311.29     10108574.43
#Sta/Elev= 30
  2949.3  883.69  3334.8   837.1  3793.8  814.17  4143.4  796.75  4241.1  776.82
  4284.7  796.63    4426  796.02  4465.7  761.41    4570  738.27  4592.2  726.11
  4765.3  685.52  5115.5  682.93  5380.2   687.3  5505.8  736.52  5709.4  760.73
    6181  763.81    6631  796.52  6914.9  802.58  7437.5  799.53  8646.3  786.16
  9375.3   799.2  9874.2  812.73 11054.8  840.82   11709  821.79 11986.2  820.18
 12432.1  825.76 13120.8  866.01 13708.2  894.34 14463.7  939.59   14684  933.47
#Mann= 18 ,-1 , 0
  2949.3      .1       0  3334.8     .05       0  3793.8     .05       0
  4241.1     .16       0  4592.2    .033       0  5505.8     .16       0
    6181      .1       0  6914.9     .16       0  7437.5     .05       0
  8646.3     .16       0  9375.3     .05       0  9874.2     .16       0
 11054.8     .16       0   11709     .05       0 11986.2     .16       0
 12432.1     .05       0 13120.8     .16       0 13708.2      .1       0
Bank Sta=4570,5505.8
XS Rating Curve= 0 ,0
Exp/Cntr=0.3,0.1

Type RM Length L Ch R = 1 ,50455   ,2148,2148,2148
BEGIN DESCRIPTION:
PEDERNALES RIVER 316.0
END DESCRIPTION:
XS GIS Cut Line= 5
      2998101.07     10119101.42      3000297.76     10117520.05
      2999290.49     10115094.44      3001266.33     10113256.96
      3001413.72     10108714.58
#Sta/Elev= 30
   759.6  888.26   910.7  884.19  1092.3  851.51  1415.1  832.41  2699.2  819.09
    2980  811.25  3407.3  798.25  4061.8  796.29  4450.6  778.52  4548.5  772.87
  4555.9  770.45  4642.6  720.37  4779.3  683.71    5247  684.57  5536.6   756.9
  5552.1  769.18  5907.4  791.63  6247.5  776.67    6502  790.31  7181.7   782.8
  7237.7  762.99  7393.7  783.84  8497.4  810.09  8877.7  804.46   10185  818.79
 11084.5  817.67   11714  849.26 12008.7  864.88 12674.2  899.01 13335.7   940.9
#Mann= 18 ,-1 , 0
   759.6      .1       0   910.7     .05       0  2699.2     .16       0
    2980     .05       0  3407.3     .16       0  4061.8     .05       0
  4450.6     .16       0  4548.5    .033       0  5536.6     .16       0
  5907.4     .05       0    6502     .05       0  7237.7     .16       0
  8877.7     .16       0   10185     .05       0 11084.5     .16       0
   11714      .1       0 12008.7     .16       0 12674.2      .1       0
Bank Sta=4555.9,5552.1
XS Rating Curve= 0 ,0
Exp/Cntr=0.3,0.1

Type RM Length L Ch R = 1 ,48307   ,1574,1574,1574
BEGIN DESCRIPTION:
PEDERNALES RIVER 317.0
END DESCRIPTION:
XS GIS Cut Line= 5
      3004042.89     10117053.53      3002069.05     10116629.79
      3001114.03     10113840.24      3001701.47     10112666.98
      3001505.83      10108846.9
#Sta/Elev= 30
  1133.6  890.04  1236.4   887.3  1400.6  883.22  1584.1  880.36  1875.4  860.74
    1983  844.54  2536.8  813.93  3301.2  795.77  4183.6  781.53  4402.7  765.84
  4416.6  761.87  4659.7  696.54  4754.6  683.06  5174.4  686.25  5251.6  719.26
  5283.3  720.85  5315.1  748.72  5325.6  782.76  5528.1  794.42  5802.8  795.76
  6175.5  804.71  6703.4  800.25  6913.3  799.82  7910.8  806.98    8357  805.85
    8768   803.8  9975.2  853.57   10818   900.9 11068.8  913.08 11238.1  925.82
#Mann= 18 ,-1 , 0
  1133.6     .16       0  1236.4      .1       0  1400.6     .05       0
    1983     .05       0  2536.8     .05       0  3301.2     .16       0
  4416.6    .033       0  5315.1     .16       0  5528.1     .05       0
  5802.8     .05       0  6175.5     .16       0  6703.4     .05       0
  6913.3     .16       0  7910.8     .05       0    8357     .16       0
  9975.2     .16       0   10818     .16       0 11068.8      .1       0
Bank Sta=4402.7,5325.6
XS Rating Curve= 0 ,0
Exp/Cntr=0.3,0.1

Type RM Length L Ch R = 1 ,46733   ,1492,1492,1492
BEGIN DESCRIPTION:
PEDERNALES RIVER 318.0
END DESCRIPTION:
XS GIS Cut Line= 3
       3004257.1     10116930.28      3001893.71     10112213.64
      3001675.87     10108778.27
#Sta/Elev= 30
  1964.5  891.13  2124.7  886.19  2304.6  878.96  2395.3  864.05  2564.6  854.28
  2617.5  839.86  2790.2  825.75    2957  817.32  3557.9  796.04  4080.4  780.21
  4315.8  780.98  4388.4  771.97  4405.2  766.97  4500.1  716.92  4790.4  683.59
  5226.4  684.97  5260.3  703.43  5410.8  759.34  5416.9  761.66  5854.1  789.19
  6869.9  794.14  7194.8  800.53  7634.9   801.9  8189.5  801.43  8934.3  828.51
  9203.4  840.61  9499.8  852.11 10466.3  907.84 10661.7  914.73 10682.4  915.38
#Mann= 18 ,-1 , 0
  1964.5     .16       0  2124.7     .16       0  2395.3     .05       0
  2790.2      .1       0    2957     .05       0  3557.9     .16       0
  4080.4     .16       0  4388.4    .033       0  5410.8     .16       0
  5854.1     .05       0  6869.9     .05       0  7194.8     .05       0
  7634.9     .16       0  8934.3     .05       0  9203.4     .16       0
  9499.8     .16       0 10466.3      .1       0 10661.7     .05       0
Bank Sta=4405.2,5416.9
XS Rating Curve= 0 ,0
Exp/Cntr=0.3,0.1

Type RM Length L Ch R = 1 ,45241   ,2218,2218,2218
BEGIN DESCRIPTION:
PEDERNALES RIVER 319.0
END DESCRIPTION:
XS GIS Cut Line= 4
      3004544.98     10116816.71      3004493.23     10113986.26
      3002637.96     10110994.58      3001764.34     10108640.01
#Sta/Elev= 30
  1378.4  886.86  1629.9  880.03  2071.5  836.58  2358.5  821.65  3007.3  807.62
  3501.7  793.16  3696.6  797.55  4475.8  781.48  4664.8   767.8  4707.3  723.16
  4783.8  687.55  4897.2  685.01  5228.8  683.69  5231.6  683.19  5234.8  683.69
  5426.7  715.69  5536.6   773.5  5728.7  785.91    5865  790.35  6298.9   799.5
  6887.5  799.78  7089.4  792.06  7243.5  785.32  7629.5  796.48  7929.8  802.22
  8203.4   810.2  8811.7  831.57  9117.8  843.92 10090.2  907.51   10241  908.87
#Mann= 20 ,-1 , 0
  1378.4     .05       0  1629.9     .16       0  2358.5     .05       0
  3007.3     .16       0  3696.6     .16       0  4783.8     .07       0
  4897.2     .05       0  5228.8    .033       0  5234.8     .16       0
  5728.7     .16       0    5865     .05       0  6298.9      .1       0
  6887.5     .05       0  7089.4     .16       0  7629.5     .16       0
  7929.8     .05       0  8203.4     .16       0  8811.7     .05       0
  9117.8     .16       0 10090.2      .1       0
Bank Sta=5228.8,5234.8
XS Rating Curve= 0 ,0
Exp/Cntr=0.3,0.1

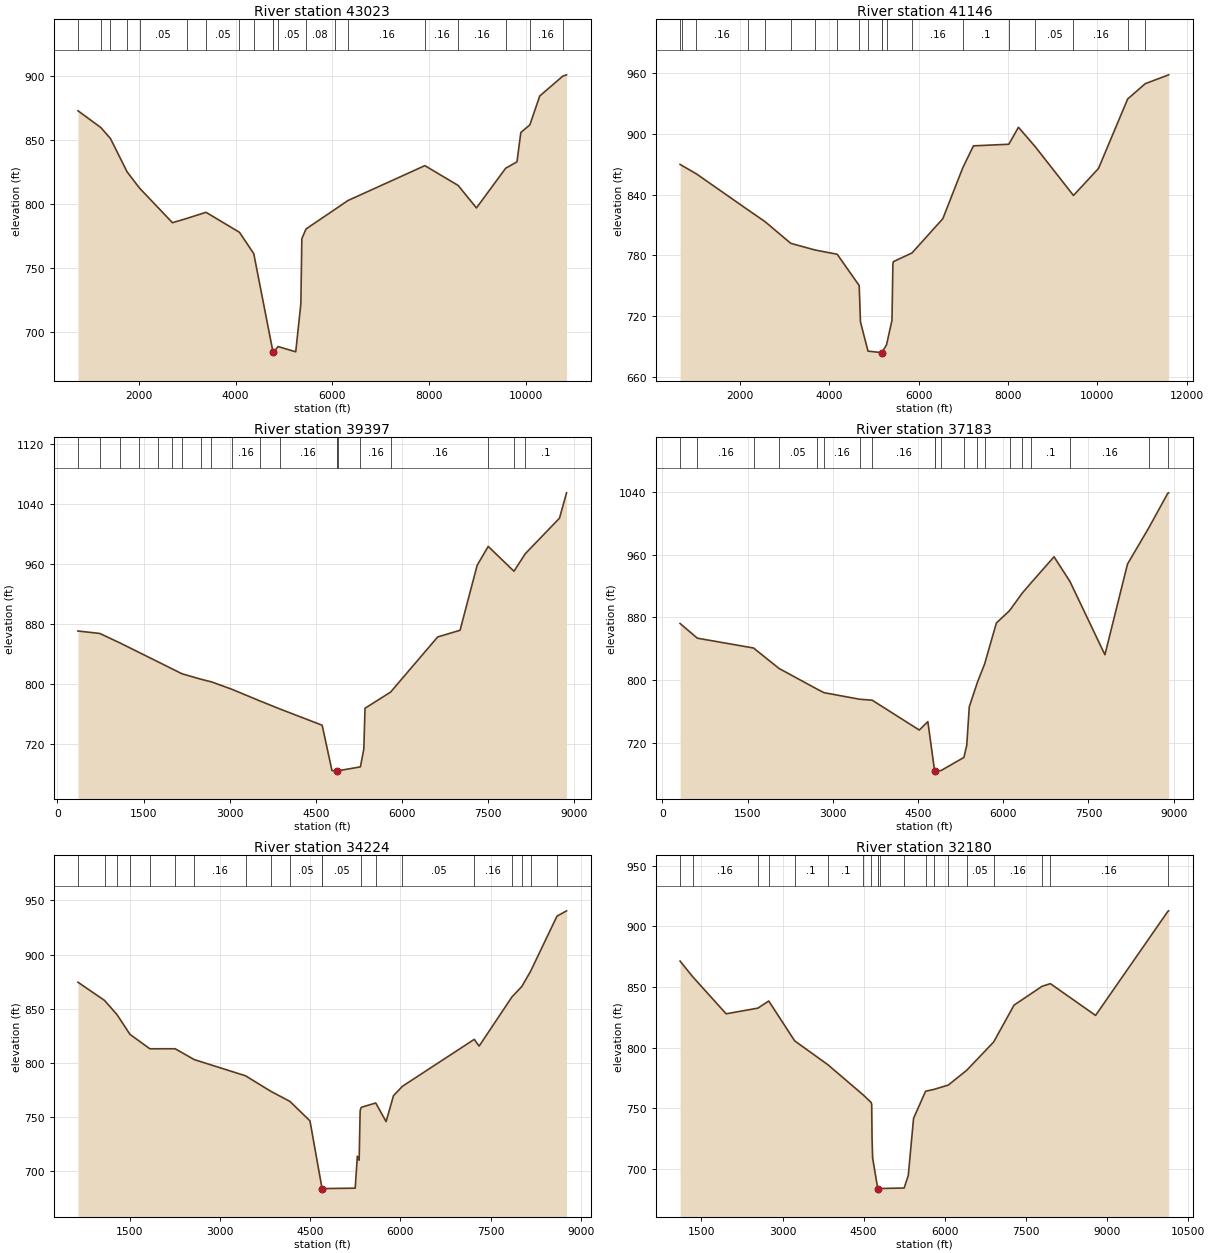
Type RM Length L Ch R = 1 ,43023   ,1877,1877,1877
BEGIN DESCRIPTION:
PEDERNALES RIVER 329.0
END DESCRIPTION:
XS GIS Cut Line= 3
      3006222.49     10116811.77      3005994.28      10113371.5
      3006368.23     10106730.35
#Sta/Elev= 30
   742.9  872.89    1216  859.79  1413.6  851.26  1757.3  825.27  2015.9  812.49
  2696.2  785.49  2994.6  788.85  3389.8  793.61  4081.5  777.99  4376.9  761.33
  4776.4  684.16  4779.2  683.66  4782.4  684.16  4879.3   688.8  5244.3  684.68
  5350.3  722.21  5370.4  773.02  5457.6   780.6  6047.1  795.69  6323.6   802.8
  7913.7  830.05  8601.5  814.59    8980  797.04  9583.9  828.02  9817.4     833
  9897.5  855.93 10084.2  861.89 10288.1  884.41 10762.9  899.89 10842.4  900.95
#Mann= 20 ,-1 , 0
   742.9      .1       0    1216     .16       0  1413.6     .05       0
  1757.3     .16       0  2015.9     .05       0  2994.6     .16       0
  3389.8     .05       0  4081.5     .05       0  4376.9      .1       0
  4776.4    .033       0  4782.4      .1       0  4879.3     .05       0
  5457.6     .08       0  6047.1     .16       0  6323.6     .16       0
  7913.7     .16       0  8601.5     .16       0  9583.9     .05       0
 10084.2     .16       0 10762.9      .1       0
Bank Sta=4776.4,4782.4
XS Rating Curve= 0 ,0
Exp/Cntr=0.3,0.1

Type RM Length L Ch R = 1 ,41146   ,1749,1749,1749
BEGIN DESCRIPTION:
PEDERNALES RIVER 330.0
END DESCRIPTION:
XS GIS Cut Line= 3
      3006366.74     10116938.56      3007711.54     10114330.26
      3008664.16     10106383.83
#Sta/Elev= 30
   657.2  869.99   702.4  868.79  1018.7  860.76  2176.3   825.1  2556.7  813.54
  3135.7  792.01  3681.5  785.39  4174.2  781.24  4666.8  750.34  4695.6  714.38
  4863.9  685.55  5166.5  684.06  5169.3  683.56  5172.5  684.06  5278.5  691.67
  5401.2  716.04  5421.3  771.05  5431.4   773.9  5849.2  782.53  6539.3  816.35
  6986.2  866.68  7224.9  888.32  8016.8  889.89  8232.5  906.67    8608  887.49
  9464.1   839.3   10024  865.95 10677.2  934.59 11071.3  949.74 11595.1  958.47
#Mann= 20 ,-1 , 0
   657.2      .1       0   702.4     .05       0  1018.7     .16       0
  2176.3     .16       0  2556.7      .1       0  3135.7     .16       0
  3681.5     .05       0  4174.2     .16       0  4666.8     .16       0
  4863.9     .05       0  5166.5    .033       0  5172.5     .05       0
  5278.5     .16       0  5849.2     .16       0  6986.2      .1       0
  8016.8      .1       0    8608     .05       0  9464.1     .16       0
 10677.2     .16       0 11071.3     .16       0
Bank Sta=5166.5,5172.5
XS Rating Curve= 0 ,0
Exp/Cntr=0.3,0.1

Type RM Length L Ch R = 1 ,39397   ,2214,2214,2214
BEGIN DESCRIPTION:
PEDERNALES RIVER 321.0
END DESCRIPTION:
XS GIS Cut Line= 4
      3006154.57     10117248.42      3008311.73     10114650.19
      3010521.31     10112865.11      3012001.36     10111112.63
#Sta/Elev= 30
   357.4  870.19   736.5  866.94  1088.8   854.3  1414.3   841.9  1747.4  829.21
  1994.4   819.8  2169.1  813.14  2502.8  805.77  2683.4  802.32  3042.2  792.33
  3530.5  776.78  3869.5  766.33  4611.4  744.45  4782.4  683.97  4864.2  683.71
    4867  683.21  4870.2  683.71  4891.7  683.76  5277.5  688.88  5337.2  712.73
  5358.1   767.1    5803  788.63  6623.7  862.26  7013.7  871.16  7311.5  957.88
  7504.4  983.08  7952.9  949.97  8150.1  973.32  8745.5 1020.71  8868.8 1054.57
#Mann= 20 ,-1 , 0
   357.4      .1       0   736.5     .05       0  1088.8     .16       0
  1414.3     .05       0  1747.4     .16       0  1994.4     .05       0
  2169.1     .16       0  2502.8     .16       0  2683.4      .1       0
  3042.2     .16       0  3530.5      .1       0  3869.5     .16       0
  4864.2    .033       0  4870.2      .1       0  4891.7     .05       0
  5277.5     .16       0    5803     .16       0  7504.4      .1       0
  7952.9     .16       0  8150.1      .1       0
Bank Sta=4864.2,4870.2
XS Rating Curve= 0 ,0
Exp/Cntr=0.3,0.1

Type RM Length L Ch R = 1 ,37183   ,2959,2959,2959
BEGIN DESCRIPTION:
PEDERNALES RIVER 322.0
END DESCRIPTION:
XS GIS Cut Line= 3
      3006212.64      10117603.3       3012622.7     10114766.13
      3013964.35     10113909.28
#Sta/Elev= 30
   310.7  872.09   614.8  853.37    1604  840.86  2050.4  814.92  2715.8  788.74
    2845  783.94    3473  775.57    3693  774.36    4522   736.3  4672.7  747.04
  4791.6  684.46  4794.4  683.96  4797.6  684.46  4902.8  684.61  5307.3  701.37
  5357.6  716.94  5402.2  765.93  5545.9  797.25  5672.7  820.59  5879.5  872.72
  6112.6  888.53  6332.6  910.65  6487.1  923.63  6894.5  957.12  7176.3  925.42
  7790.2  832.28  8188.3   947.9  8561.9   993.9  8897.4 1038.09  8912.5 1038.61
#Mann= 20 ,-1 , 0
   310.7      .1       0   614.8     .16       0    1604     .05       0
  2050.4     .05       0  2715.8      .1       0    2845     .16       0
    3473     .05       0    3693     .16       0  4791.6    .033       0
  4797.6     .16       0  4902.8     .05       0  5307.3     .16       0
  5545.9     .08       0  5672.7     .16       0  6112.6      .1       0
  6332.6      .1       0  6487.1      .1       0  7176.3     .16       0
  8561.9     .05       0  8897.4     .16       0
Bank Sta=4791.6,4797.6
XS Rating Curve= 0 ,0
Exp/Cntr=0.3,0.1

Type RM Length L Ch R = 1 ,34224   ,2044,2044,2044
BEGIN DESCRIPTION:
PEDERNALES RIVER 323.0
END DESCRIPTION:
XS GIS Cut Line= 3
      3005959.42     10117870.97      3008751.57     10117822.24
      3013641.82     10119945.32
#Sta/Elev= 30
   637.9  874.37  1079.5  857.57  1286.2  844.49  1502.7  826.16  1833.3  812.84
  2254.2  812.86  2571.5  802.82  3424.6  787.85    3846  773.47    4163  764.14
  4495.5  746.19  4696.7  683.56  4699.5  683.06  4702.7  683.56  5247.7  683.95
  5282.9   713.5  5313.1  709.78  5329.8  755.65  5348.9  758.71    5589  762.71
  5761.2  745.49    5884  769.46  6032.8  778.14    7227  821.54  7308.1  815.31
  7853.8  860.77  8017.4  870.39  8162.9  884.38  8602.7  935.47  8761.7  940.39
#Mann= 20 ,-1 , 0
   637.9     .05       0  1079.5     .16       0  1286.2      .1       0
  1502.7      .1       0  1833.3     .16       0  2254.2      .1       0
  2571.5     .16       0  3424.6     .16       0    3846      .1       0
    4163     .05       0  4696.7    .033       0  4702.7     .05       0
  5348.9     .05       0    5589     .16       0  6032.8     .05       0
    7227     .16       0  7853.8     .05       0  8017.4     .08       0
  8162.9     .05       0  8602.7     .08       0
Bank Sta=4696.7,4702.7
XS Rating Curve= 0 ,0
Exp/Cntr=0.3,0.1

Type RM Length L Ch R = 1 ,32180   ,2465,2465,2465
BEGIN DESCRIPTION:
PEDERNALES RIVER 324.0
END DESCRIPTION:
XS GIS Cut Line= 3
      3005832.31     10118036.04      3007128.59     10119343.76
      3013782.04     10122071.97
#Sta/Elev= 30
  1106.1  871.28  1336.3  858.54  1957.4   827.8  2544.3  832.48  2745.5  838.34
  3224.5  805.49    3836  785.91  4491.5  760.93  4636.1  754.81  4648.5  753.24
    4655  725.55  4665.8     709    4760  683.73  4762.8  683.23    4766  683.73
  4806.1  683.75  5247.8  684.15  5325.1  694.52  5422.3  741.58  5644.9  763.97
  5791.2  765.36  6064.3  769.03  6406.4  781.27  6903.2  804.56  7279.6  834.92
  7797.8  850.47  7951.7  852.67  8787.4  826.48 10122.7   912.2 10138.5  912.71
#Mann= 20 ,-1 , 0
  1106.1     .05       0  1336.3     .16       0  2544.3      .1       0
  2745.5      .1       0  3224.5      .1       0    3836      .1       0
  4491.5      .1       0  4636.1     .16       0    4760    .033       0
    4766     .16       0  4806.1     .05       0  5247.8     .16       0
  5644.9     .08       0  5791.2     .16       0  6064.3     .05       0
  6406.4     .05       0  6903.2     .16       0  7797.8     .05       0
  7951.7     .16       0 10122.7      .1       0
Bank Sta=4760,4766
XS Rating Curve= 0 ,0
Exp/Cntr=0.3,0.1

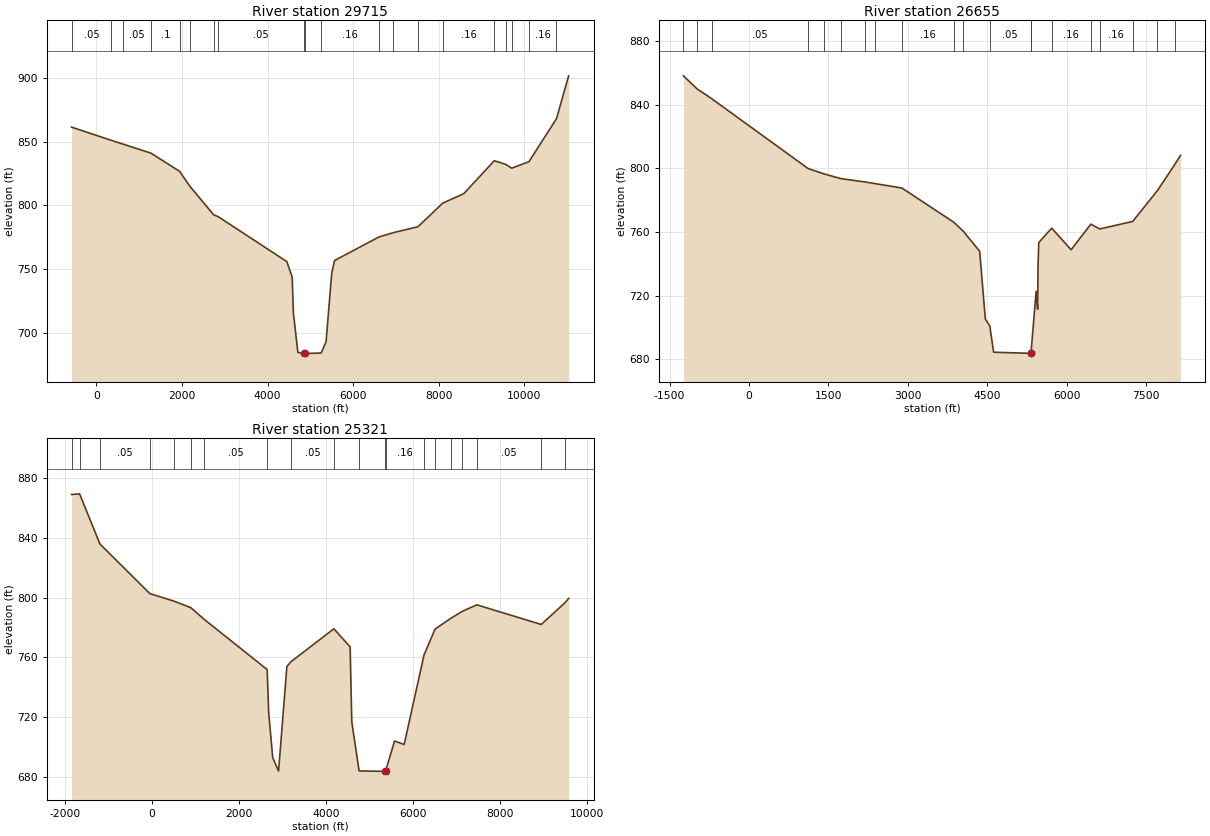
Type RM Length L Ch R = 1 ,29715   ,3060,3060,3060
BEGIN DESCRIPTION:
PEDERNALES RIVER 325.0
END DESCRIPTION:
XS GIS Cut Line= 4
      3005016.01     10118345.37      3006055.87     10121292.22
      3012075.05     10124491.72      3013727.52     10124234.43
#Sta/Elev= 30
  -579.2  861.32   348.7  850.98     614   848.1  1276.7  840.91  1944.5   826.7
  2182.8  815.11  2738.3  792.68  2847.6  791.12  4450.7  755.91  4575.8  743.81
  4604.5   715.7  4708.8  684.72  4859.6  683.89  4862.4  683.39  4865.6  683.89
  5252.6  684.26  5367.4  693.02  5499.3  746.69  5565.2  756.73  6598.7  775.16
  6937.2  778.59  7513.6  783.22  8094.9  801.76  8584.1  809.13  9297.4  834.95
  9564.6  832.14  9704.7  829.15   10107   834.2 10750.7  867.94 11034.8  901.52
#Mann= 20 ,-1 , 0
  -579.2     .05       0   348.7      .1       0     614     .05       0
  1276.7      .1       0  1944.5     .05       0  2182.8     .05       0
  2738.3      .1       0  2847.6     .05       0  4859.6    .033       0
  4865.6     .05       0  5252.6     .16       0  6598.7     .05       0
  6937.2     .05       0  7513.6      .1       0  8094.9     .16       0
  9297.4     .05       0  9564.6     .05       0  9704.7     .16       0
   10107     .16       0 10750.7      .1       0
Bank Sta=4859.6,4865.6
XS Rating Curve= 0 ,0
Exp/Cntr=0.3,0.1

Type RM Length L Ch R = 1 ,26655   ,1334,1334,1334
BEGIN DESCRIPTION:
PEDERNALES RIVER 326.0
END DESCRIPTION:
XS GIS Cut Line= 3
      3004755.43     10118359.49      3004960.33      10122841.1
      3008072.65     10126629.11
#Sta/Elev= 30
 -1237.5  858.22  -977.6  849.95  -705.3  843.89  1117.6   799.9  1418.4  796.53
  1733.8  793.59  2198.3  791.42  2375.7  790.46  2888.6  787.67  3869.6   766.1
    4048  760.51  4357.6  747.83  4464.5  705.19  4548.3  700.92  4620.9  684.38
  5320.4  683.68  5323.1  683.18  5326.4  683.68  5423.8   722.7  5452.4  711.37
    5459  737.57  5473.3  753.34  5717.8  762.43  6084.6  748.83  6457.2  764.93
  6625.8  761.89  7248.6  766.67  7712.8  785.98  8039.4   802.3  8151.4  808.23
#Mann= 20 ,-1 , 0
 -1237.5     .16       0  -977.6     .16       0  -705.3     .05       0
  1117.6      .1       0  1418.4      .1       0  1733.8     .05       0
  2198.3      .1       0  2375.7     .05       0  2888.6     .16       0
  3869.6     .05       0    4048     .16       0  4548.3     .05       0
  5320.4    .033       0  5326.4     .16       0  5717.8     .16       0
  6457.2      .1       0  6625.8     .16       0  7248.6     .05       0
  7712.8      .1       0  8039.4     .05       0
Bank Sta=5320.4,5326.4
XS Rating Curve= 0 ,0
Exp/Cntr=0.3,0.1

Type RM Length L Ch R = 1 ,25321   ,2310,2310,2310
BEGIN DESCRIPTION:
PEDERNALES RIVER 327.0
END DESCRIPTION:
XS GIS Cut Line= 5
      3000920.34     10118928.29       3002964.3     10122104.59
      3004273.48     10123631.17       3006337.3     10127302.45
      3007744.82     10127085.75
#Sta/Elev= 30
 -1849.9  868.74 -1664.5  869.19 -1198.1  835.77     -49  802.59   513.2  797.49
   891.6  793.22  1197.8  785.45  2645.7  751.93  2681.1  723.13  2773.3  693.15
  2908.3  684.23  3099.3  753.99  3189.8  757.08  4178.8  779.14  4552.7  767.04
  4590.3  717.03  4758.8  684.27  5359.4  683.98  5362.1  683.48  5365.4  683.98
  5573.4  704.25  5794.6  701.92  6250.7  761.68  6503.6  778.92  6862.2  786.04
  7129.1  790.77  7463.7  795.12  8944.1  782.01  9490.4  796.52    9574  799.39
#Mann= 20 ,-1 , 0
 -1849.9     .08       0 -1664.5     .05       0 -1198.1     .05       0
     -49     .05       0   513.2     .16       0   891.6      .1       0
  1197.8     .05       0  2645.7     .16       0  3189.8     .05       0
  4178.8     .16       0  4758.8     .05       0  5359.4    .033       0
  5365.4     .16       0  6250.7     .08       0  6503.6     .05       0
  6862.2     .05       0  7129.1     .08       0  7463.7     .05       0
  8944.1      .1       0  9490.4      .1       0
Bank Sta=5359.4,5365.4
XS Rating Curve= 0 ,0
Exp/Cntr=0.3,0.1