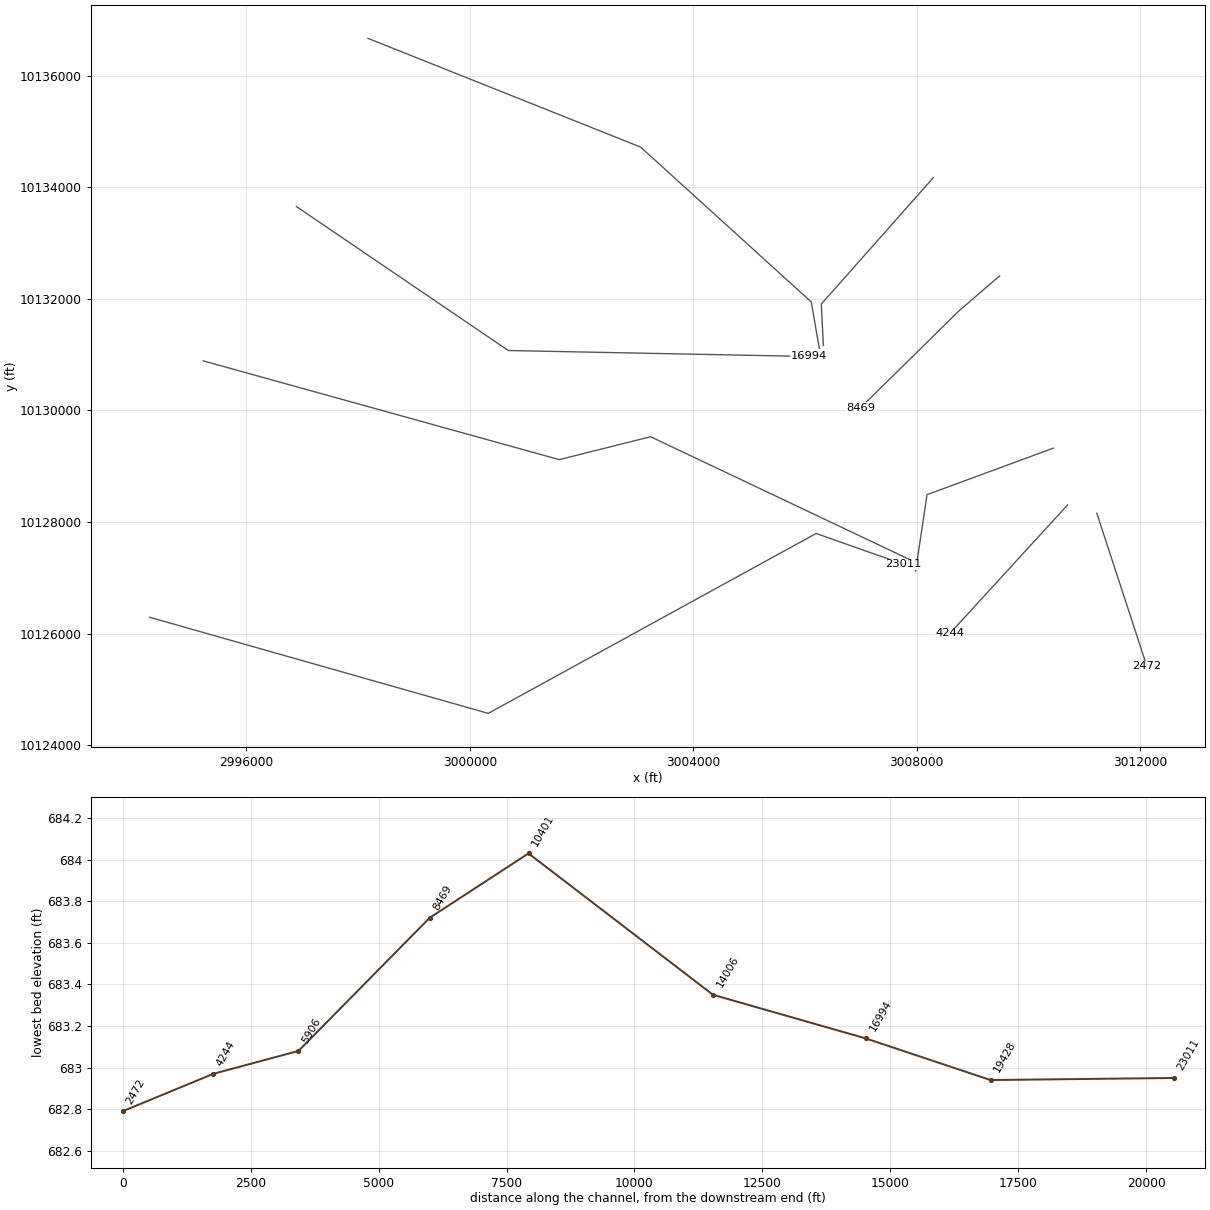
HEC-RAS study PEDERNALES RIVER.prj: PEDERNALES RIVER Base Level Engineering

--- PEDERNALES RIVER.g02 (geometry) --- (continued)

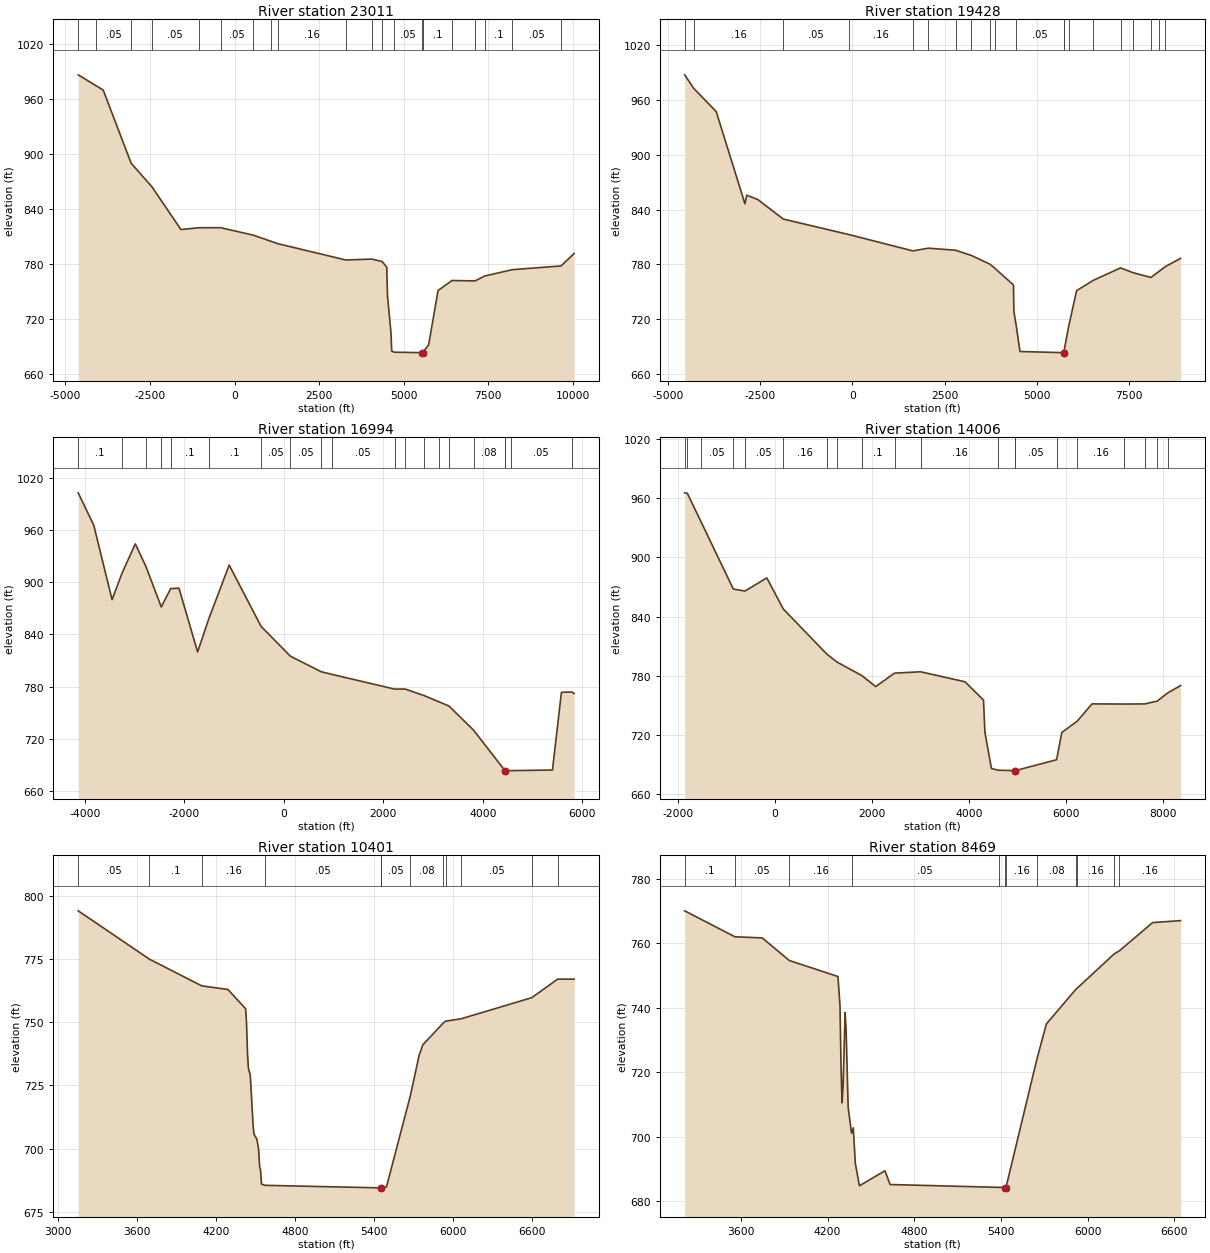
Type RM Length L Ch R = 1 ,23011   ,3583,3583,3583
BEGIN DESCRIPTION:
PEDERNALES RIVER 328.0
END DESCRIPTION:
XS GIS Cut Line= 4
      2994266.93     10126293.65      3000329.67     10124571.88
      3006200.98     10127795.53      3007770.29     10127242.08
#Sta/Elev= 30
 -4623.9  985.93 -4091.1  973.97 -3884.2  969.33 -3059.4  889.71 -2441.7  863.91
 -1586.8  817.47 -1066.8  819.46    -414   819.5   548.1  811.45  1074.1  804.72
    1279   802.1  3288.8  784.35  4059.2  785.33  4360.9  782.72  4499.3  776.44
  4521.1  745.39  4624.4  705.01  4646.2  685.24  4722.9  683.96  5550.9  683.45
  5553.6  682.95  5556.9  683.45  5738.5  691.94  6016.3   751.1  6429.6  762.01
  7111.9  761.57  7393.5  766.89  8212.3  773.81    9653  777.87 10040.7  791.45
#Mann= 20 ,-1 , 0
 -4623.9     .05       0 -4091.1     .05       0 -3059.4     .16       0
 -2441.7     .05       0 -1066.8     .16       0    -414     .05       0
   548.1     .16       0  1074.1     .05       0    1279     .16       0
  3288.8     .16       0  4059.2     .16       0  4360.9      .1       0
  4722.9     .05       0  5550.9    .033       0  5556.9      .1       0
  6429.6     .08       0  7111.9      .1       0  7393.5      .1       0
  8212.3     .05       0    9653      .1       0
Bank Sta=5550.9,5556.9
XS Rating Curve= 0 ,0
Exp/Cntr=0.3,0.1

Type RM Length L Ch R = 1 ,19428   ,2434,2434,2434
BEGIN DESCRIPTION:
PEDERNALES RIVER 331.0
END DESCRIPTION:
XS GIS Cut Line= 4
      2995225.64     10130888.67      3001601.44     10129118.71
      3003236.91     10129529.57      3007868.09     10127331.85
#Sta/Elev= 30
 -4540.9  987.28 -4298.8   972.6   -3687   947.1 -2908.6  846.21 -2860.4   855.7
 -2560.3  850.91 -1869.5  829.53   -98.1  812.64  1640.4  794.73  2059.7  797.72
  2794.8  795.45  3219.8  789.79  3724.5  780.21  3854.4  775.86  4361.7  757.51
  4374.5  728.46  4440.8  711.95  4539.2   684.7  5717.6  683.44  5720.4  682.94
  5723.6  683.44  5857.7  712.26  6072.7  751.27  6526.7  762.59  7261.2  776.14
  7609.9  770.79  8084.7   765.7  8300.8  772.25  8478.8  777.64  8888.5  786.61
#Mann= 20 ,-1 , 0
 -4540.9      .1       0 -4298.8     .16       0 -1869.5     .05       0
   -98.1     .16       0  1640.4     .05       0  2059.7     .16       0
  2794.8     .05       0  3219.8     .16       0  3724.5     .05       0
  3854.4     .05       0  4440.8     .05       0  5717.6    .033       0
  5723.6     .05       0  5857.7     .16       0  6526.7     .05       0
  7261.2      .1       0  7609.9     .05       0  8084.7      .1       0
  8300.8     .05       0  8478.8      .1       0
Bank Sta=5717.6,5723.6
XS Rating Curve= 0 ,0
Exp/Cntr=0.3,0.1

Type RM Length L Ch R = 1 ,16994   ,2988,2988,2988
BEGIN DESCRIPTION:
PEDERNALES RIVER 332.0
END DESCRIPTION:
XS GIS Cut Line= 3
      2996894.49     10133653.97      3000688.72     10131074.13
      3006064.14     10130967.13
#Sta/Elev= 30
 -4131.4 1002.55   -3819   965.4 -3450.9  879.93 -3251.5  910.28 -2983.8  943.96
 -2772.4  918.18 -2462.2  871.58 -2273.5  892.62 -2106.7  893.08 -1732.3  819.93
 -1509.3  857.73   -1098   919.6  -457.4  849.32   131.3  815.08   748.5  797.26
   961.1  794.25  2230.5  777.22  2433.8  777.43  2823.3  769.71  3119.7  762.63
  3317.3  757.91  3811.3  730.22  4444.4  683.64  4447.1  683.14  4450.4  683.64
  4554.4   683.7  5397.5  684.42  5577.6  773.59  5787.4  773.93  5833.3  772.21
#Mann= 20 ,-1 , 0
 -4131.4      .1       0 -3251.5      .1       0 -2772.4      .1       0
 -2462.2     .16       0 -2273.5      .1       0 -1509.3      .1       0
  -457.4     .05       0   131.3     .05       0   748.5      .1       0
   961.1     .05       0  2230.5     .05       0  2433.8      .1       0
  2823.3     .05       0  3119.7     .08       0  3317.3     .05       0
  3811.3     .08       0  4444.4    .033       0  4450.4      .1       0
  4554.4     .05       0  5787.4     .05       0
Bank Sta=4444.4,4450.4
XS Rating Curve= 0 ,0
Exp/Cntr=0.3,0.1

Type RM Length L Ch R = 1 ,14006   ,3605,3605,3605
BEGIN DESCRIPTION:
PEDERNALES RIVER 333.0
END DESCRIPTION:
XS GIS Cut Line= 4
      2998175.45     10136668.19      3003058.75     10134719.06
      3006113.82     10131944.53      3006256.69     10131117.62
#Sta/Elev= 30
 -1855.3  965.42 -1800.1  964.89   -1529  937.18  -852.8  867.92  -611.5  865.86
  -162.1  879.19   177.9  847.65  1072.1  802.12  1281.5  793.98  1791.7  780.36
  2082.5  769.07  2470.6  782.65  3008.1  784.05    3923  773.91  4305.5  755.38
  4333.9  722.74  4468.4  686.07  4609.2  684.27  4953.3  683.85    4956  683.35
  4959.3  683.85  5812.2  694.89  5919.2  722.46  6237.5  734.02  6542.3   751.5
  7198.7  751.34  7630.2  751.48  7884.5  754.26  8099.5  762.52  8368.7  770.09
#Mann= 20 ,-1 , 0
 -1855.3     .05       0 -1800.1     .08       0   -1529     .05       0
  -852.8      .1       0  -611.5     .05       0   177.9     .16       0
  1072.1      .1       0  1281.5     .16       0  1791.7      .1       0
  2470.6     .16       0  3008.1     .16       0  4609.2     .05       0
  4953.3    .033       0  4959.3     .05       0  5812.2     .16       0
  6237.5     .16       0  7198.7     .05       0  7630.2     .08       0
  7884.5     .05       0  8099.5     .08       0
Bank Sta=4953.3,4959.3
XS Rating Curve= 0 ,0
Exp/Cntr=0.3,0.1

Type RM Length L Ch R = 1 ,10401   ,1932,1932,1932
BEGIN DESCRIPTION:
PEDERNALES RIVER 334.0
END DESCRIPTION:
XS GIS Cut Line= 3
      3008297.28     10134169.31      3006293.14      10131906.1
      3006330.97     10131164.39
#Sta/Elev= 30
  3154.6  794.02  3693.5  774.98  4092.9  764.36  4291.2  762.94  4425.9  755.32
  4432.5  749.84  4440.1  737.65  4446.8  731.77    4461  729.17  4482.7  709.11
  4489.4  705.75  4511.1  703.78  4524.5  699.74  4532.1  692.87  4538.8  691.68
  4546.3  686.05  4572.9  685.53    5450  684.53  5452.7  684.03    5456  684.53
  5495.6  684.99  5676.7  720.95  5743.2  736.93  5771.6  741.09  5926.9  749.68
    5944  750.41  6062.1  751.35  6598.7   759.7  6795.2  767.03  6920.3  767.03
#Mann= 12 ,-1 , 0
  3154.6     .05       0  3693.5      .1       0  4092.9     .16       0
  4572.9     .05       0    5450    .033       0    5456     .05       0
  5676.7     .08       0  5926.9     .05       0    5944      .1       0
  6062.1     .05       0  6598.7     .16       0  6795.2     .05       0
Bank Sta=5450,5456
XS Rating Curve= 0 ,0
Exp/Cntr=0.3,0.1

Type RM Length L Ch R = 1 ,8469    ,2563,2563,2563
BEGIN DESCRIPTION:
PEDERNALES RIVER 335.0
END DESCRIPTION:
XS GIS Cut Line= 3
      3009487.17     10132411.43      3008756.15     10131782.18
       3006998.2     10130050.43
#Sta/Elev= 30
  3210.9  770.02  3558.2  761.98  3747.5  761.62  3935.2  754.61  4271.7  749.65
  4285.8  740.63  4292.9   721.9  4299.9  710.47  4307.1  715.63  4321.2  738.48
  4328.2  732.98  4342.4  709.07  4365.5  701.04  4377.8  702.74  4391.9  691.73
  4420.2  684.76    4597  689.42  4632.4  685.15  5384.3  684.27  5428.4  684.22
  5431.2  683.72  5434.4  684.22  5650.3  724.35  5714.3  734.95  5916.3  745.58
  5927.5  746.04  6182.3  756.62  6220.1  757.65  6449.6  766.38  6643.1  766.98
#Mann= 12 ,-1 , 0
  3210.9      .1       0  3558.2     .05       0  3935.2     .16       0
  4365.5     .05       0  5384.3     .16       0  5428.4    .033       0
  5434.4     .16       0  5650.3     .08       0  5916.3     .05       0
  5927.5     .16       0  6182.3     .05       0  6220.1     .16       0
Bank Sta=5428.4,5434.4
XS Rating Curve= 0 ,0
Exp/Cntr=0.3,0.1

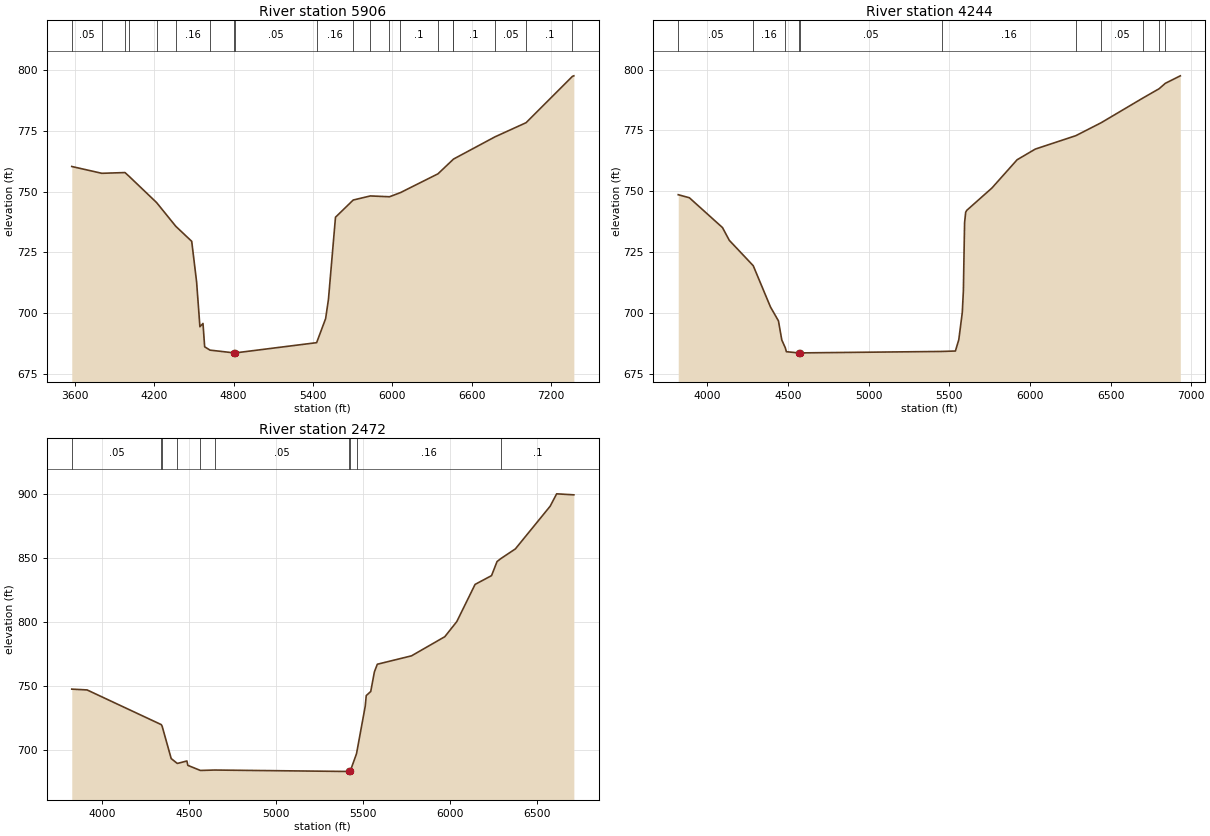
Type RM Length L Ch R = 1 ,5906    ,1662,1662,1662
BEGIN DESCRIPTION:
PEDERNALES RIVER 336.0
END DESCRIPTION:
XS GIS Cut Line= 3
      3010449.46     10129325.09      3008186.72     10128490.97
      3007982.35     10127121.32
#Sta/Elev= 30
  3576.9  760.33    3804  757.53  3979.5  757.83  4011.2  756.25  4218.3  745.48
  4363.5  735.71  4483.9  729.52  4520.8  712.84  4545.9  694.36  4569.1  695.71
  4581.7   686.1    4622  684.73  4806.3  683.58    4809  683.08  4812.3  683.58
  5428.4   687.8  5496.4   697.7  5517.7  705.59    5571  739.44  5704.8  746.52
  5834.7  748.21  5979.2  747.87  6062.4  749.58  6346.1  757.32  6462.5  763.34
  6462.9  763.37  6777.4  772.55    7012  778.36  7362.8  797.45  7373.3  797.66
#Mann= 20 ,-1 , 0
  3576.9     .05       0    3804     .16       0  3979.5      .1       0
  4011.2     .16       0  4218.3     .05       0  4363.5     .16       0
    4622     .05       0  4806.3    .033       0  4812.3     .05       0
  5428.4     .16       0  5704.8      .1       0  5834.7     .05       0
  5979.2     .16       0  6062.4      .1       0  6346.1     .05       0
  6462.5     .16       0  6462.9      .1       0  6777.4     .05       0
    7012      .1       0  7362.8     .16       0
Bank Sta=4806.3,4812.3
XS Rating Curve= 0 ,0
Exp/Cntr=0.3,0.1

Type RM Length L Ch R = 1 ,4244    ,1772,1772,1772
BEGIN DESCRIPTION:
PEDERNALES RIVER 337.0
END DESCRIPTION:
XS GIS Cut Line= 2
      3010702.98     10128306.65      3008602.54     10126010.28
#Sta/Elev= 30
  3820.1  748.52  3889.2  747.26  4094.6  734.99  4136.5  729.77    4285  719.33
  4391.8  702.37  4441.2  696.66  4462.1  688.76  4483.5  685.61  4490.5  683.97
  4565.8  683.47  4568.6  682.97  4571.8  683.47  5453.4  684.07  5538.2  684.25
  5559.2  688.92  5580.8  700.08  5587.6  709.03    5595  736.97  5601.8  741.31
  5609.2  742.13  5764.6  751.28  5920.6  762.89  6033.4  767.28  6284.9   772.8
  6441.5  778.11  6700.6  788.28    6801   792.1  6839.1  794.31  6932.2   797.4
#Mann= 11 ,-1 , 0
  3820.1     .05       0    4285     .16       0  4483.5     .05       0
  4565.8    .033       0  4571.8     .05       0  5453.4     .16       0
  6284.9      .1       0  6441.5     .05       0  6700.6     .16       0
    6801      .1       0  6839.1     .05       0
Bank Sta=4565.8,4571.8
XS Rating Curve= 0 ,0
Exp/Cntr=0.3,0.1

Type RM Length L Ch R = 1 ,2472    ,0,0,0
BEGIN DESCRIPTION:
PEDERNALES RIVER 338.0
END DESCRIPTION:
XS GIS Cut Line= 2
      3011227.61     10128156.88      3012123.98     10125414.25
#Sta/Elev= 30
  3825.1  747.54  3913.1  746.91  4339.3  719.86  4344.3  718.69  4396.5  693.37
  4431.7  689.56  4486.8  691.48  4492.1  688.07  4564.4  684.09  4645.4  684.42
  5418.8  683.29  5421.5  682.79  5424.8  683.29  5461.6  697.19  5511.7  734.26
  5517.4   742.5  5543.3   745.7  5564.3  760.99  5581.1  766.95  5777.7  773.51
  5968.9  788.43  6037.9  800.24  6142.9  829.23  6237.6  836.09  6269.2  847.07
  6291.1  849.38  6374.4  856.91  6574.3  890.22  6611.7  899.89  6710.5   899.1
#Mann= 10 ,-1 , 0
  3825.1     .05       0  4339.3     .16       0  4344.3     .08       0
  4431.7     .05       0  4564.4     .16       0  4645.4     .05       0
  5418.8    .033       0  5424.8     .05       0  5461.6     .16       0
  6291.1      .1       0
Bank Sta=5418.8,5424.8
XS Rating Curve= 0 ,0
Exp/Cntr=0.3,0.1