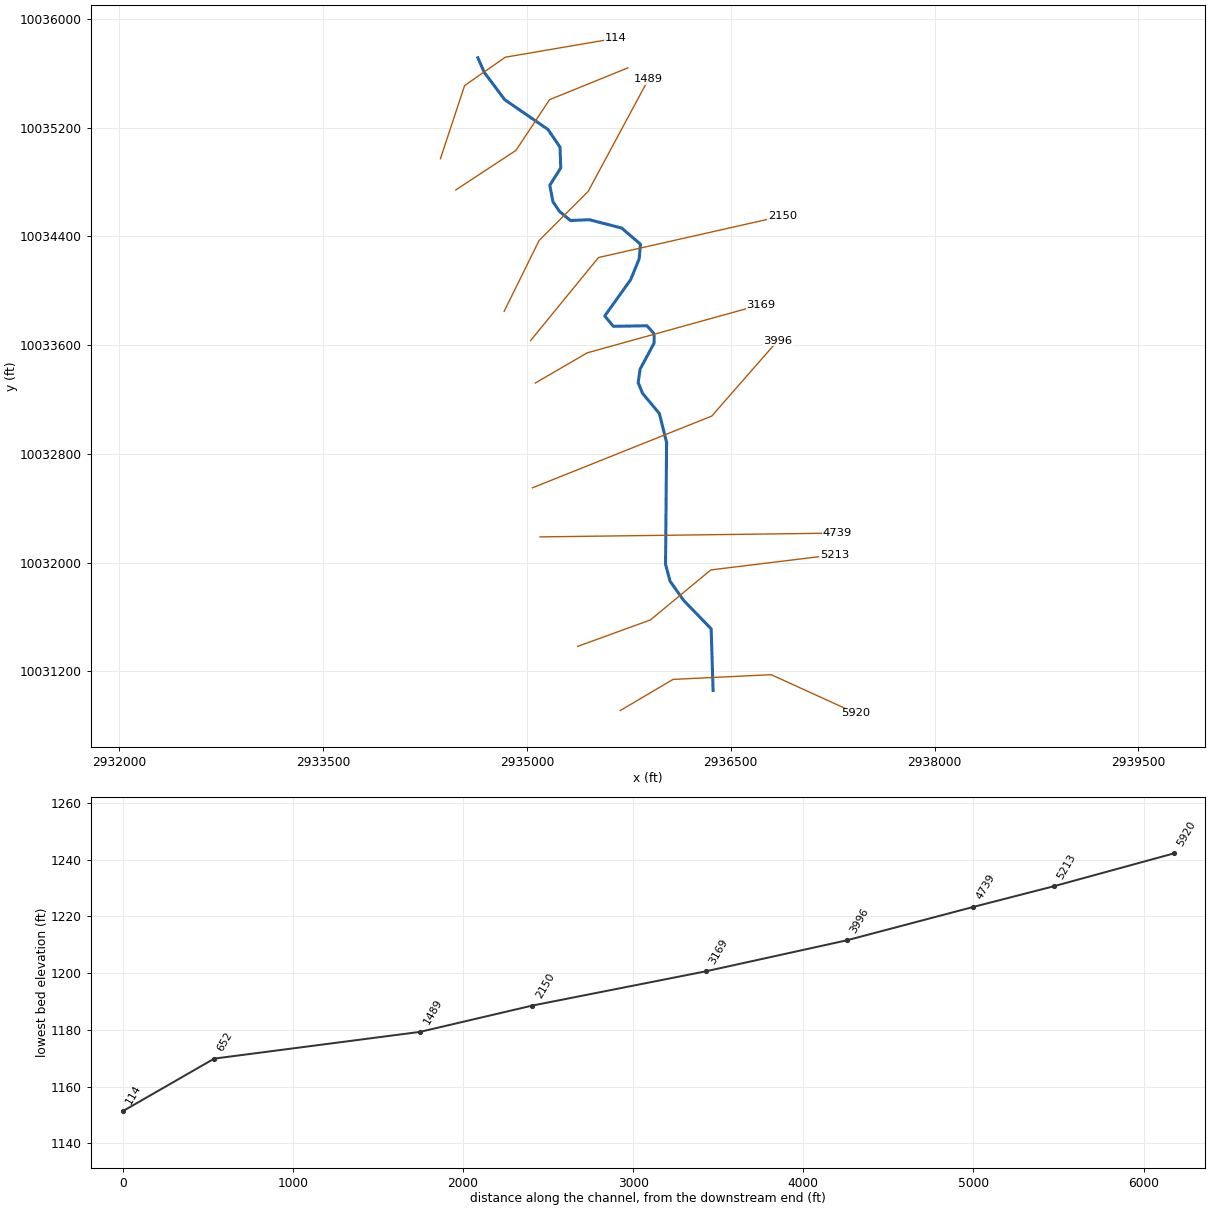
--- BATES CREEK.prj (project) ---

Proj Title=BATES CREEK Base Level Engineering
Current Plan=p01
Default Exp/Contr=0.3,0.1
English Units
Geom File=g01
Flow File=f01
Plan File=p01
Y Axis Title=Elevation
X Axis Title(PF)=Main Channel Distance
X Axis Title(XS)=Station
BEGIN DESCRIPTION:
BATES CREEK
END DESCRIPTION:
DSS Export Rating Curves= 0
DSS Export Rating Curve Sorted= 0
DSS Export Volume Flow Curves= 0
DXF OffsetX= 0
DXF OffsetY= 0
DXF ScaleX= 1
DXF ScaleY= 10

--- BATES CREEK.p01 (plan) ---

Plan Title=Multiple Run
Short Identifier=Multiple
Geom File=g01
Flow File=f01
Subcritical Flow
K Sum by GR= 0
Std Step Tol= 0.01
Critical Tol= 0.01
Num of Std Step Trials= 20
Max Error Tol= 0.3
Flow Tol Ratio= 0.001
Split Flow NTrial= 30
Split Flow Tol= 0.02
Split Flow Ratio= 0.02
Log Output Level= 0
Friction Slope Method= 1
Unsteady Friction Slope Method= 2
Unsteady Bridges Friction Slope Method= 1
Parabolic Critical Depth
Global Vel Dist=  1 , 1 , 1
Global Log Level= 0
CheckData=True
Encroach Param= -1, 0, 0, 0
BEGIN DESCRIPTION:
Multiple Run
END DESCRIPTION:

--- BATES CREEK.f01 (steady flow) ---

Flow Title=Multiple
Number of Profiles=7
Profile Names=10-year,25-year,50-year,1pct_min,100-year,1pct_plu,500-year
River Rch & RM= BATES CREEK,Reach-1,5920
     973    1421    1814    1697    2295    3104    3684
River Rch & RM= BATES CREEK,Reach-1,5213
    1390    2065    2666    2519    3406    4607    5579
Boundary for River Rch & Prof#=BATES CREEK,Reach-1,1
Up Type=0
Dn Type=3
Dn Slope=0.005
Boundary for River Rch & Prof#=BATES CREEK,Reach-1,2
Up Type=0
Dn Type=3
Dn Slope=0.005
Boundary for River Rch & Prof#=BATES CREEK,Reach-1,3
Up Type=0
Dn Type=3
Dn Slope=0.005
Boundary for River Rch & Prof#=BATES CREEK,Reach-1,4
Up Type=0
Dn Type=3
Dn Slope=0.005
Boundary for River Rch & Prof#=BATES CREEK,Reach-1,5
Up Type=0
Dn Type=3
Dn Slope=0.005
Boundary for River Rch & Prof#=BATES CREEK,Reach-1,6
Up Type=0
Dn Type=3
Dn Slope=0.005
Boundary for River Rch & Prof#=BATES CREEK,Reach-1,7
Up Type=0
Dn Type=3
Dn Slope=0.005

--- BATES CREEK.g01 (geometry) ---

Geom Title=Existing Conditions
Program Version=4.10

River Reach=BATES CREEK     ,Reach-1
Reach XY= 30
      2936369.69     10031058.88      2936355.35     10031512.29
      2936153.46      10031720.9      2936052.79     10031863.41
      2936019.76     10031986.97       2936027.4     10032883.29
      2935974.19     10033096.73      2935850.65     10033244.63
      2935818.37     10033323.85      2935832.12      10033422.2
      2935935.65     10033615.07      2935935.89     10033682.71
      2935883.28     10033742.24      2935635.36     10033738.14
      2935572.26     10033814.45      2935762.83     10034081.35
      2935825.74     10034234.98      2935835.13     10034342.21
      2935697.33     10034460.99      2935458.37     10034522.53
      2935319.59     10034516.58      2935239.45     10034583.34
      2935191.02     10034654.79       2935167.9     10034775.88
      2935248.59     10034903.64      2935243.12     10035056.22
      2935154.86     10035186.15      2934836.09     10035405.72
      2934686.38     10035605.49      2934638.47     10035713.73

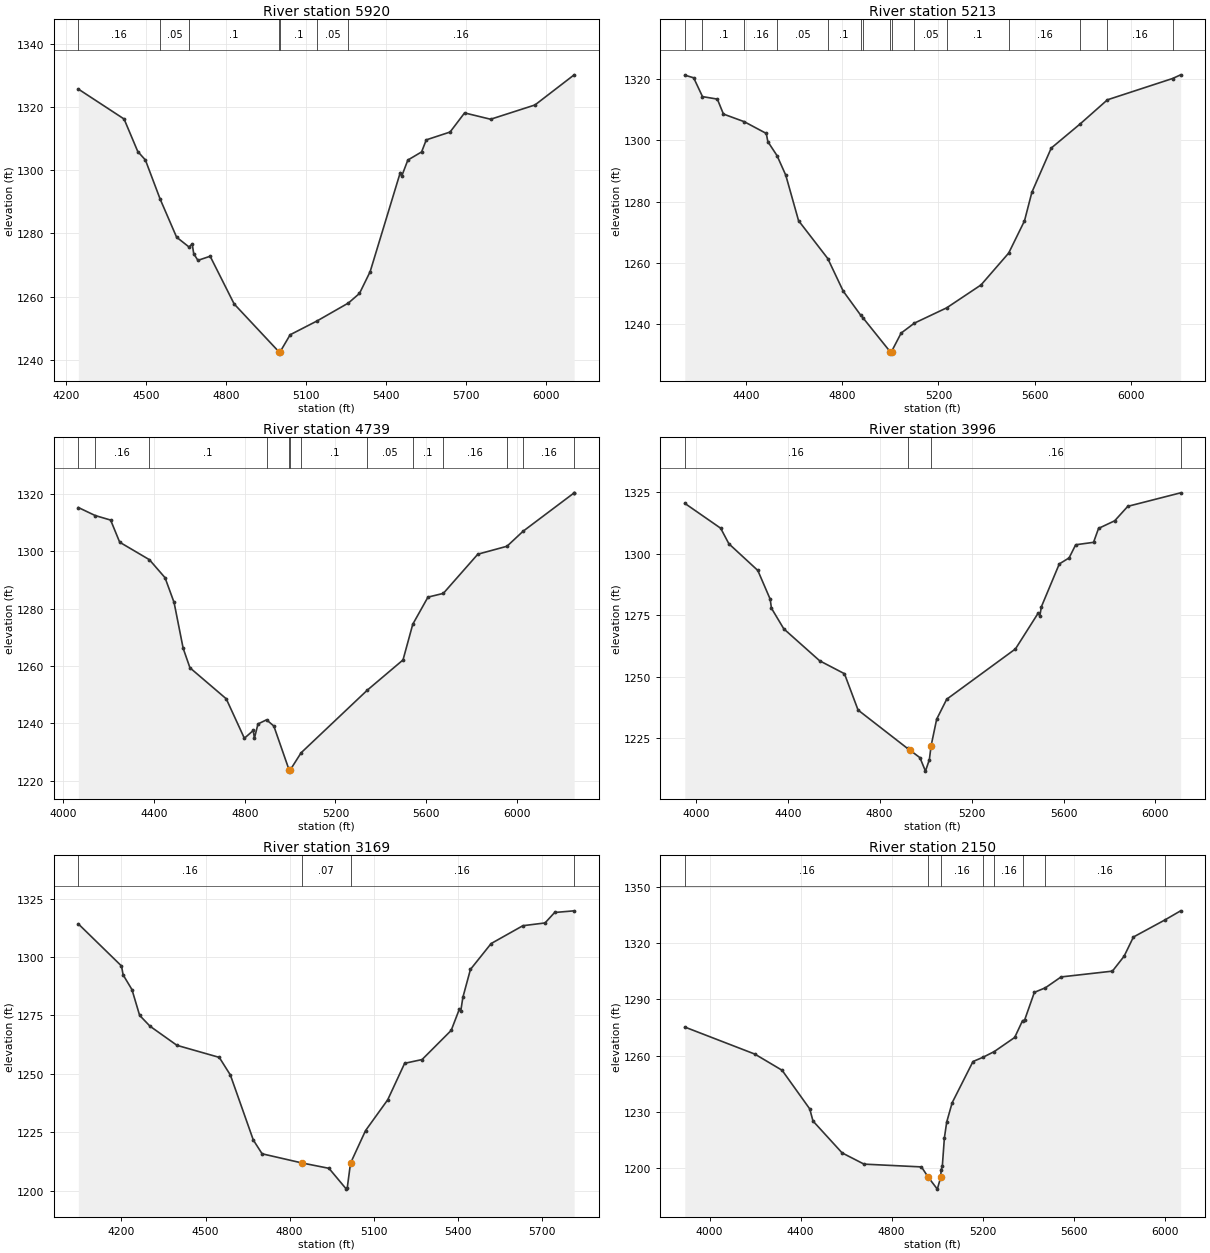
Type RM Length L Ch R = 1 ,5920    ,707,707,707
BEGIN DESCRIPTION:
BATES CREEK 13.0
END DESCRIPTION:
XS GIS Cut Line= 4
      2935686.26      10030911.1      2936075.14     10031140.26
      2936797.37     10031174.99      2937422.33     10030890.28
#Sta/Elev= 30
  4245.3 1325.61    4417 1316.16  4468.4 1305.89  4497.1  1303.2  4552.3 1290.88
  4614.2 1278.83  4660.9 1275.73  4672.7 1276.69  4678.5 1273.59  4694.2 1271.51
  4740.1 1272.81  4830.2 1257.74  4997.4 1242.71  5000.1 1242.21  5003.4 1242.71
  5040.4 1248.01  5141.3 1252.37  5259.3 1258.05  5300.7 1261.07  5340.7 1267.94
  5453.7 1299.23  5459.2 1298.11  5482.2 1303.19  5533.8 1305.76  5551.4 1309.57
  5640.7 1312.04  5695.2 1318.08  5792.9 1316.08  5959.4 1320.59  6106.5 1330.11
#Mann= 7 ,-1 , 0
  4245.3     .16       0  4552.3     .05       0  4660.9      .1       0
  4997.4     .07       0  5003.4      .1       0  5141.3     .05       0
  5259.3     .16       0
Bank Sta=4997.4,5003.4
XS Rating Curve= 0 ,0
Exp/Cntr=0.3,0.1

Type RM Length L Ch R = 1 ,5213    ,474,474,474
BEGIN DESCRIPTION:
BATES CREEK 12.0
END DESCRIPTION:
XS GIS Cut Line= 4
      2935373.79     10031383.33      2935908.48     10031577.76
      2936352.92     10031945.82      2937262.66     10032056.93
#Sta/Elev= 30
  4145.1 1321.31    4182 1320.45  4218.7 1314.31  4280.5  1313.5  4305.8 1308.62
  4392.3 1306.13    4484  1302.3  4490.6 1299.61  4528.8 1295.05  4565.1 1288.68
  4618.3 1273.84  4739.8 1261.48    4804 1250.85  4876.4 1243.03  4886.8 1242.08
    4999 1231.11  5001.7 1230.61    5005 1231.11    5045 1237.15  5100.4 1240.41
  5234.7  1245.4  5377.3 1252.86  5492.4 1263.26  5558.1 1273.76  5588.8 1283.09
  5669.4 1297.52    5790 1305.42  5903.1 1313.27  6174.1 1320.22  6207.6 1321.42
#Mann= 15 ,-1 , 0
  4145.1     .16       0  4218.7      .1       0  4392.3     .16       0
  4528.8     .05       0  4739.8      .1       0  4876.4     .05       0
  4886.8      .1       0    4999     .07       0    5005      .1       0
  5100.4     .05       0  5234.7      .1       0  5492.4     .16       0
    5790      .1       0  5903.1     .16       0  6174.1      .1       0
Bank Sta=4999,5005
XS Rating Curve= 0 ,0
Exp/Cntr=0.3,0.1

Type RM Length L Ch R = 1 ,4739    ,743,743,743
BEGIN DESCRIPTION:
BATES CREEK 10.0
END DESCRIPTION:
XS GIS Cut Line= 2
      2935095.96     10032188.87      2937283.48     10032216.65
#Sta/Elev= 30
  4065.8 1315.22  4140.2 1312.42  4208.3 1310.84  4248.3 1303.12  4379.4 1297.02
  4448.3 1290.75  4488.3  1282.1  4528.3 1266.14  4558.3 1259.33  4718.4 1248.52
  4798.4 1234.76  4837.7 1237.48  4842.7 1234.74  4858.4 1239.74  4896.2 1241.19
  4928.4 1239.02  4995.4  1223.8  4998.1  1223.3  5001.4  1223.8  5048.7 1229.69
  5341.6 1251.59  5498.4 1262.07  5541.4 1274.52  5608.4 1283.97  5676.3 1285.28
  5828.4 1298.94  5957.1 1301.71  6028.1 1306.94    6253  1320.3  6253.5 1320.34
#Mann= 13 ,-1 , 0
  4065.8      .1       0  4140.2     .16       0  4379.4      .1       0
  4896.2     .05       0  4995.4    .035       0  5001.4     .05       0
  5048.7      .1       0  5341.6     .05       0  5541.4      .1       0
  5676.3     .16       0  5957.1      .1       0  6028.1     .16       0
    6253     .05       0
Bank Sta=4995.4,5001.4
XS Rating Curve= 0 ,0
Exp/Cntr=0.3,0.1

Type RM Length L Ch R = 1 ,3996    ,827,827,827
BEGIN DESCRIPTION:
BATES CREEK 9.0
END DESCRIPTION:
XS GIS Cut Line= 3
       2935040.4     10032549.98      2936359.87     10033077.76
      2936844.72     10033631.88
#Sta/Elev= 30
  3952.2 1320.56  4108.3 1310.43    4144  1304.1  4269.9 1293.24  4323.8 1281.52
  4329.1 1277.89    4383 1269.46  4539.2 1256.45  4646.9  1251.2  4706.1 1236.41
  4921.5 1220.76  4930.2  1220.2  4975.4 1217.01  4999.3 1211.54  5016.4 1216.23
  5023.8 1221.82  5048.1 1232.68  5091.8 1240.81  5390.9 1261.29  5489.6 1275.84
  5497.2 1274.88  5503.9 1278.49  5581.7  1295.9  5624.4 1298.35  5652.9 1303.69
  5730.7 1304.69  5752.5 1310.36  5822.8 1313.46  5879.7 1319.34  6109.6 1324.84
#Mann= 4 ,-1 , 0
  3952.2     .16       0  4921.5     .07       0  5023.8     .16       0
  6109.6     .16       0
Bank Sta=4930.2,5023.8
XS Rating Curve= 0 ,0
Exp/Cntr=0.3,0.1

Type RM Length L Ch R = 1 ,3169    ,1019,1019,1019
BEGIN DESCRIPTION:
BATES CREEK 7.0
END DESCRIPTION:
XS GIS Cut Line= 3
      2935061.26     10033320.82       2935443.2     10033543.04
      2936720.94      10033897.2
#Sta/Elev= 30
  4046.6  1314.2  4200.5 1296.18  4206.3 1292.37  4237.8 1286.07  4265.1 1275.05
  4302.3 1270.38  4398.3  1262.2  4549.1 1257.04  4588.6 1249.51  4670.4 1221.68
  4701.8 1215.76  4844.2 1211.83  4940.2 1209.54  5002.2 1200.63  5005.4 1201.13
 5017.05 1211.74  5070.6 1225.69  5149.6 1238.87    5210  1254.5  5272.2 1256.12
    5376  1268.6  5405.1 1277.71  5410.3 1276.99  5417.5 1282.69  5444.6  1294.7
  5518.4 1305.79  5631.6 1313.43  5710.5 1314.61  5744.8 1319.09  5814.4  1319.8
#Mann= 4 ,-1 , 0
  4046.6     .16       0  4844.2     .07       0 5017.05     .16       0
  5814.4     .16       0
Bank Sta=4844.2,5017.05
XS Rating Curve= 0 ,0
Exp/Cntr=0.3,0.1

Type RM Length L Ch R = 1 ,2150    ,661,661,661
BEGIN DESCRIPTION:
BATES CREEK 6.0
END DESCRIPTION:
XS GIS Cut Line= 3
      2935026.55     10033633.33      2935526.53     10034244.43
      2936880.71     10034549.99
#Sta/Elev= 30
  3891.5 1275.23  4199.1 1260.77  4318.9 1252.11  4440.2 1231.47  4454.6 1224.98
  4582.4 1207.94  4678.7 1201.93    4931 1200.44  4959.8  1195.1  5000.6 1188.56
 5015.34 1194.82  5017.4 1198.83  5022.6 1200.76  5031.6 1215.87  5041.9 1224.44
  5065.8 1234.75  5157.3 1256.79  5200.8 1259.05  5250.4 1262.09  5340.5 1269.67
  5375.1 1278.69  5383.7 1278.83  5426.9 1293.79  5475.3 1296.22  5544.2 1302.03
  5769.7 1305.13    5821  1313.1    5862 1323.38    5999 1332.42  6069.3 1337.38
#Mann= 8 ,-1 , 0
  3891.5     .16       0  4959.8     .07       0 5015.34     .16       0
  5200.8      .1       0  5250.4     .16       0  5375.1      .1       0
  5475.3     .16       0    5999      .1       0
Bank Sta=4959.8,5015.34
XS Rating Curve= 0 ,0
Exp/Cntr=0.3,0.1

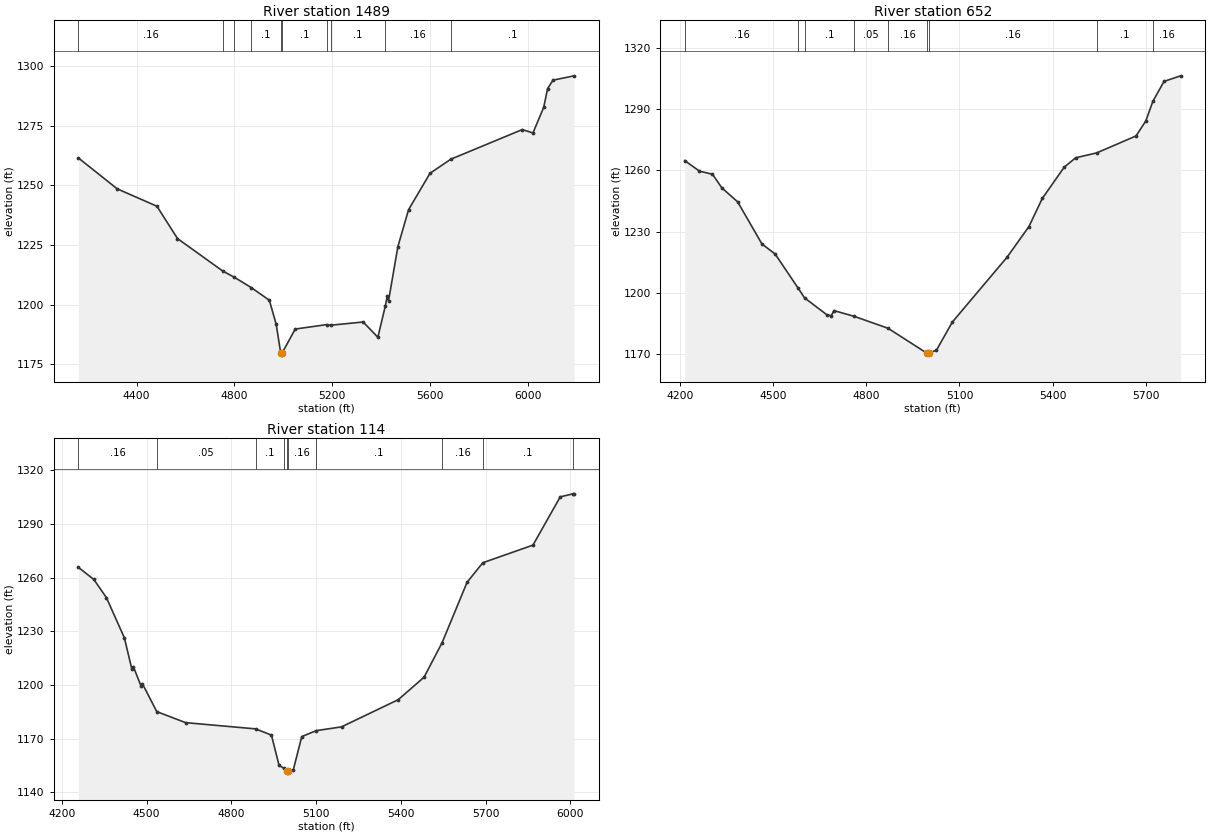
Type RM Length L Ch R = 1 ,1489    ,1209,1209,1209
BEGIN DESCRIPTION:
BATES CREEK 3.0
END DESCRIPTION:
XS GIS Cut Line= 4
      2934832.11     10033848.63      2935089.03     10034369.43
      2935450.14     10034730.54        2935894.     10035555.84
#Sta/Elev= 30
  4161.6 1261.53  4320.4 1248.58  4483.1 1241.27  4567.3 1227.72  4752.7 1214.09
  4800.4 1211.46  4869.6 1207.13    4943 1201.87  4971.2 1191.75  4989.5 1179.77
  4992.2 1179.27  4995.5 1179.77    5049 1189.79    5177 1191.63  5193.9 1191.39
  5326.9 1192.74    5387 1186.34  5417.7 1199.51  5425.1 1203.43  5430.8 1201.68
  5468.9 1224.33  5512.7 1239.83  5600.4 1255.08  5685.4 1260.98  5977.7  1273.4
  6021.6    1272  6065.4  1282.7  6081.6 1290.59  6103.5 1294.12  6190.1 1295.94
#Mann= 10 ,-1 , 0
  4161.6     .16       0  4752.7      .1       0  4800.4     .16       0
  4869.6      .1       0  4989.5     .07       0  4995.5      .1       0
    5177     .16       0  5193.9      .1       0  5417.7     .16       0
  5685.4      .1       0
Bank Sta=4989.5,4995.5
XS Rating Curve= 0 ,0
Exp/Cntr=0.3,0.1

Type RM Length L Ch R = 1 ,652     ,538,538,538
BEGIN DESCRIPTION:
Mapping XS caebffd2
END DESCRIPTION:
XS GIS Cut Line= 4
      2934475.98     10034741.57      2934918.66     10035032.35
      2935166.05     10035405.62      2935741.76     10035639.36
#Sta/Elev= 30
  4214.3 1264.76  4261.5 1259.61  4303.6 1258.08  4333.8  1251.4  4384.8 1244.53
  4463.3 1223.83  4505.5 1218.98  4579.9 1202.19  4600.4 1197.45  4671.9 1189.21
  4686.3 1188.65  4695.4  1191.2  4761.4 1188.34  4869.8 1182.53  4994.5 1170.35
  4997.3 1169.85  5000.5 1170.35  5025.8 1171.78    5077 1185.57  5253.5  1217.4
  5323.9 1232.41    5367  1246.2  5438.2 1261.64    5475 1266.17  5542.2 1268.54
  5669.2 1276.86  5700.7 1284.17  5723.6 1293.83  5759.6 1303.62  5813.1 1306.36
#Mann= 9 ,-1 , 0
  4214.3     .16       0  4579.9     .05       0  4600.4      .1       0
  4761.4     .05       0  4869.8     .16       0  4994.5     .07       0
  5000.5     .16       0  5542.2      .1       0  5723.6     .16       0
Bank Sta=4994.5,5000.5
XS Rating Curve= 0 ,0
Exp/Cntr=0.3,0.1

Type RM Length L Ch R = 1 ,114     ,0,0,0
BEGIN DESCRIPTION:
BATES CREEK 1.0
END DESCRIPTION:
XS GIS Cut Line= 4
       2934363.1     10034971.59      2934541.05     10035509.78
      2934840.53     10035718.12      2935652.17     10035857.01
#Sta/Elev= 30
  4258.3 1265.77  4313.2 1258.98  4357.8 1248.83  4421.3 1226.33  4447.7  1208.9
    4453 1210.32  4479.5 1199.69  4484.7 1200.82    4536 1185.11  4638.1 1178.95
  4885.5 1175.47  4941.8 1171.99  4968.8  1155.1  4985.2 1153.52  4995.5 1151.79
  4998.3 1151.29  5001.5 1151.79  5019.5 1152.74  5049.2 1171.16  5100.5 1174.48
    5190 1176.59  5390.8  1191.8  5482.1 1204.35  5546.3 1223.75  5634.3 1257.39
  5690.1 1268.34  5867.6 1278.19  5964.2 1305.17  6009.3 1306.86  6013.4 1306.86
#Mann= 10 ,-1 , 0
  4258.3     .16       0    4536     .05       0  4885.5      .1       0
  4985.2     .16       0  4995.5     .07       0  5001.5     .16       0
  5100.5      .1       0  5546.3     .16       0  5690.1      .1       0
  6009.3     .16       0
Bank Sta=4995.5,5001.5
XS Rating Curve= 0 ,0
Exp/Cntr=0.3,0.1

Chan Stop Cuts=-1
Use User Specified Reach Order=0
Composite Channel Slope=5