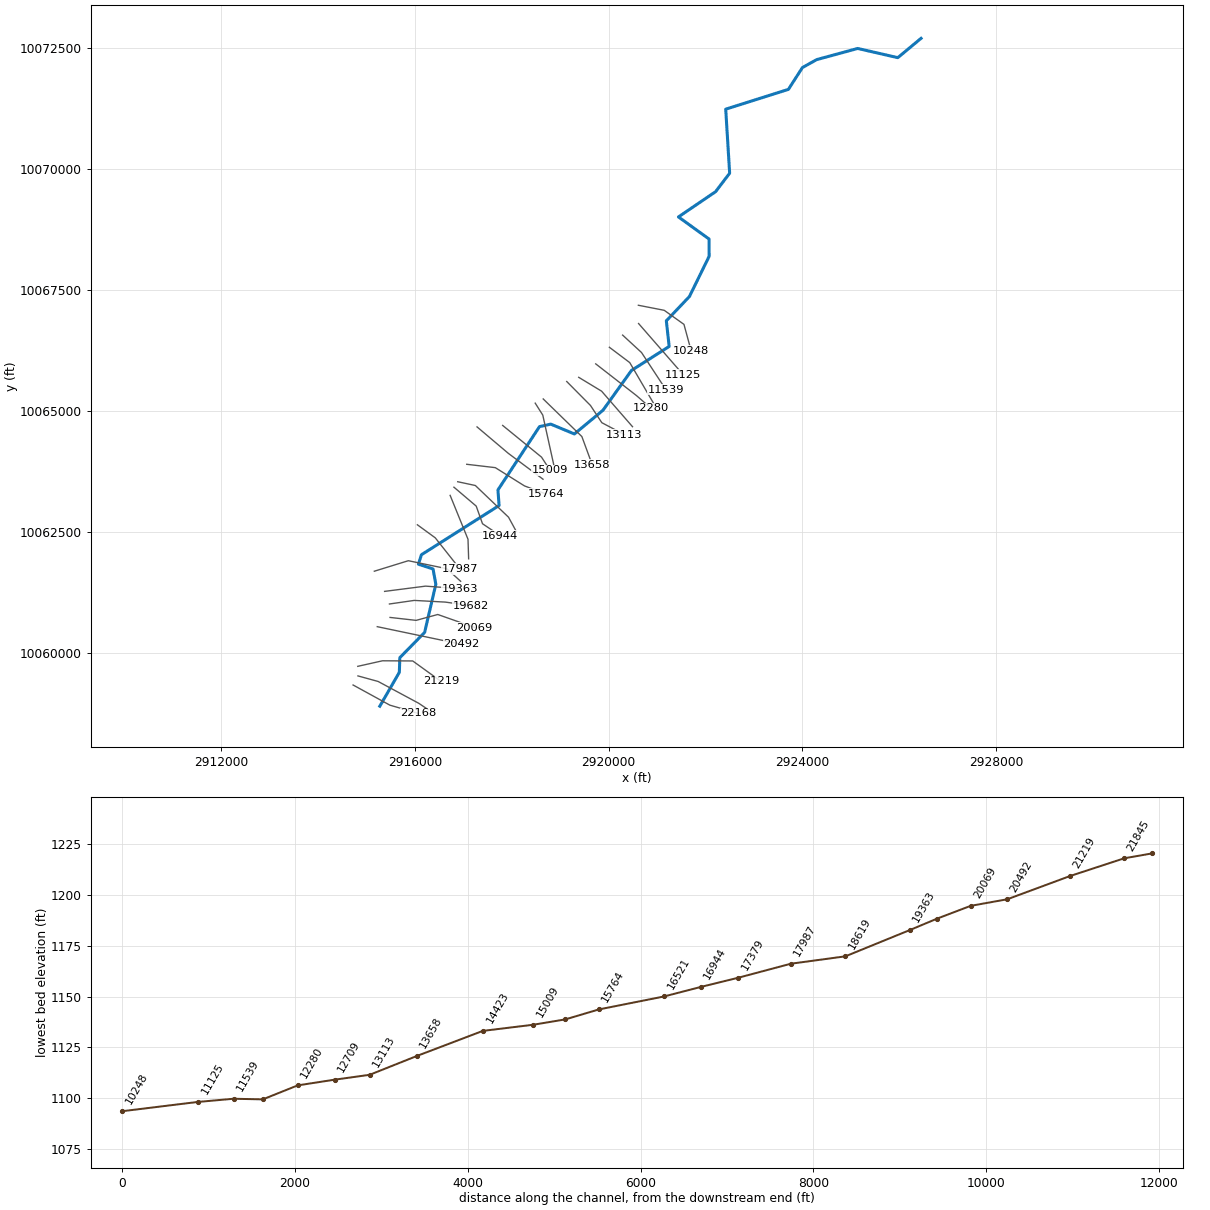
--- BROCK HOLLOW.prj (project) ---

Proj Title=BROCK HOLLOW Base Level Engineering
Current Plan=p01
Default Exp/Contr=0.3,0.1
English Units
Geom File=g01
Flow File=f01
Plan File=p01
Y Axis Title=Elevation
X Axis Title(PF)=Main Channel Distance
X Axis Title(XS)=Station
BEGIN DESCRIPTION:
BROCK HOLLOW
END DESCRIPTION:
DSS Export Rating Curves= 0
DSS Export Rating Curve Sorted= 0
DSS Export Volume Flow Curves= 0
DXF OffsetX= 0
DXF OffsetY= 0
DXF ScaleX= 1
DXF ScaleY= 10

--- BROCK HOLLOW.p01 (plan) ---

Plan Title=Multiple Run
Short Identifier=Multiple
Geom File=g01
Flow File=f01
Subcritical Flow
K Sum by GR= 0
Std Step Tol= 0.01
Critical Tol= 0.01
Num of Std Step Trials= 20
Max Error Tol= 0.3
Flow Tol Ratio= 0.001
Split Flow NTrial= 30
Split Flow Tol= 0.02
Split Flow Ratio= 0.02
Log Output Level= 0
Friction Slope Method= 1
Unsteady Friction Slope Method= 2
Unsteady Bridges Friction Slope Method= 1
Parabolic Critical Depth
Global Vel Dist=  1 , 1 , 1
Global Log Level= 0
CheckData=True
Encroach Param= -1, 0, 0, 0
BEGIN DESCRIPTION:
Multiple Run
END DESCRIPTION:

--- BROCK HOLLOW.f01 (steady flow) ---

Flow Title=Multiple
Program Version=4.10
Number of Profiles= 7
Profile Names=10-year,25-year,50-year,1pct_min,100-year,1pct_plu,500-year
River Rch & RM=BROCK HOLLOW,Reach-1         ,22168
    1062    1569    2019    1906    2577    3486    4210
River Rch & RM=BROCK HOLLOW,Reach-1         ,20492
    1657    2498    3259    3110    4206    5688    7031
River Rch & RM=BROCK HOLLOW,Reach-1         ,15764
    2110    3205    4199    4020    5437    7353    9151
River Rch & RM=BROCK HOLLOW,Reach-1         ,9866
    3513    5418    7171    6918    9356   12653   15997
River Rch & RM=BROCK HOLLOW,Reach-1         ,9432
    3513    5418    7171    6918    9356   12653   15997
Boundary for River Rch & Prof#=BROCK HOLLOW,Reach-1         , 1
Up Type= 0
Dn Type= 3
Dn Slope=0.005
Boundary for River Rch & Prof#=BROCK HOLLOW,Reach-1         , 2
Up Type= 0
Dn Type= 3
Dn Slope=0.005
Boundary for River Rch & Prof#=BROCK HOLLOW,Reach-1         , 3
Up Type= 0
Dn Type= 3
Dn Slope=0.005
Boundary for River Rch & Prof#=BROCK HOLLOW,Reach-1         , 4
Up Type= 0
Dn Type= 3
Dn Slope=0.005
Boundary for River Rch & Prof#=BROCK HOLLOW,Reach-1         , 5
Up Type= 0
Dn Type= 3
Dn Slope=0.005
Boundary for River Rch & Prof#=BROCK HOLLOW,Reach-1         , 6
Up Type= 0
Dn Type= 3
Dn Slope=0.005
Boundary for River Rch & Prof#=BROCK HOLLOW,Reach-1         , 7
Up Type= 0
Dn Type= 3
Dn Slope=0.005
DSS Import GetInterval= 0
DSS Import GetPeak= 0
DSS Import FillOption= 0

--- BROCK HOLLOW.g01 (geometry) ---

Geom Title=Existing Conditions
Program Version=4.10

River Reach=BROCK HOLLOW    ,Reach-1
Reach XY= 30
      2915271.02     10058904.64      2915674.96     10059605.19
      2915683.87      10059906.3      2916197.12     10060429.22
      2916428.23     10061423.65      2916370.98     10061739.95
      2916068.11     10061838.61      2916131.47     10062034.21
      2917735.05     10063050.33      2917711.47     10063372.36
      2918570.13     10064681.17      2918803.09      10064732.1
      2919291.19     10064529.06      2919880.69     10065017.73
      2920469.26     10065840.77      2921249.32     10066337.11
      2921190.59     10066866.35      2921668.17     10067368.85
      2922075.09     10068199.42      2922073.93     10068556.47
      2921440.68     10069012.93      2922208.72     10069534.86
      2922499.03     10069916.54      2922417.57     10071239.57
      2923712.92     10071648.78      2924002.53     10072099.34
      2924296.55     10072263.17      2925143.38     10072493.93
      2925973.27     10072303.93      2926453.84     10072703.12

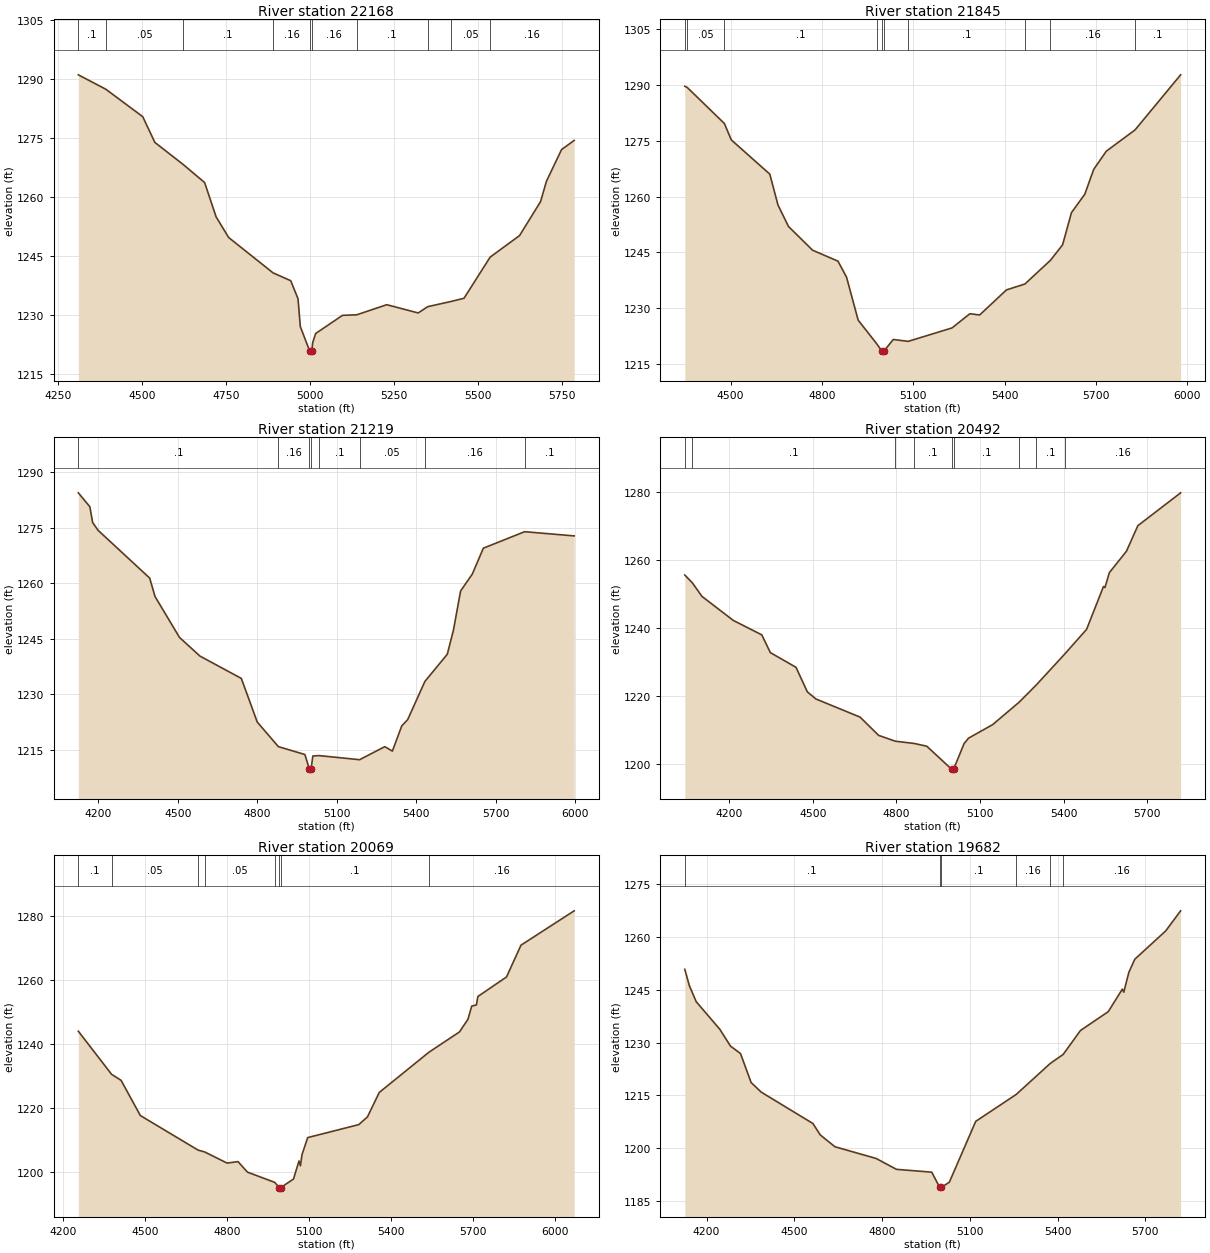
Type RM Length L Ch R = 1 ,22168   ,323,323,323
BEGIN DESCRIPTION:
BROCK HOLLOW 50.0
END DESCRIPTION:
XS GIS Cut Line= 3
      2914718.59     10059342.68      2915478.99     10058926.02
       2916064.6     10058756.23
#Sta/Elev= 30
  4310.4 1291.06  4391.9 1287.42  4502.2 1280.43  4538.3 1273.89  4623.2 1268.24
  4686.6 1263.68  4720.8 1254.96  4758.2 1249.71  4890.4 1240.73    4943 1238.74
  4964.8 1234.13  4971.6 1227.07  4999.7 1220.83  5002.5 1220.33  5005.7 1220.83
  5008.4 1222.99  5017.2 1225.31  5097.1 1229.93  5139.7 1230.07    5229 1232.64
  5322.7 1230.54  5350.8 1232.13    5420 1233.45  5459.1 1234.27    5537 1244.73
  5624.6 1250.21  5687.1 1258.83  5704.6    1264  5749.6 1272.05  5787.2 1274.39
#Mann= 10 ,-1 , 0
  4310.4      .1       0  4391.9     .05       0  4623.2      .1       0
  4890.4     .16       0  4999.7     .07       0  5005.7     .16       0
  5139.7      .1       0  5350.8     .16       0    5420     .05       0
    5537     .16       0
Bank Sta=4999.7,5005.7
XS Rating Curve= 0 ,0
Exp/Cntr=0.3,0.1

Type RM Length L Ch R = 1 ,21845   ,626,626,626
BEGIN DESCRIPTION:
BROCK HOLLOW 49.0
END DESCRIPTION:
XS GIS Cut Line= 4
      2914819.29     10059530.18      2915235.94     10059415.61
      2916076.21     10058964.22      2916277.57     10058828.82
#Sta/Elev= 30
  4349.3 1289.62  4357.3 1289.31  4479.4 1279.61  4502.2  1275.2  4628.5 1266.02
  4655.4 1257.72  4689.9 1251.95  4769.1 1245.57  4852.4 1242.64  4880.6 1238.33
  4918.8 1226.78  4979.5 1220.46    4997 1218.42  4999.7 1217.92    5003 1218.42
    5034 1221.59    5083 1221.08    5227 1224.69  5285.7 1228.51  5317.8 1228.17
  5405.8 1234.91  5466.4 1236.49  5550.3 1242.86  5590.2 1247.02  5619.3 1255.66
  5663.2 1260.62  5692.4  1267.3  5733.7 1272.17  5828.3 1277.91  5977.9  1292.7
#Mann= 10 ,-1 , 0
  4349.3      .1       0  4357.3     .05       0  4479.4      .1       0
  4979.5     .16       0    4997     .07       0    5003     .16       0
    5083      .1       0  5466.4     .05       0  5550.3     .16       0
  5828.3      .1       0
Bank Sta=4997,5003
XS Rating Curve= 0 ,0
Exp/Cntr=0.3,0.1

Type RM Length L Ch R = 1 ,21219   ,727,727,727
BEGIN DESCRIPTION:
BROCK HOLLOW 48.0
END DESCRIPTION:
XS GIS Cut Line= 4
      2914815.75      10059728.1      2915326.21     10059842.69
      2915951.21     10059839.22      2916538.01     10059415.61
#Sta/Elev= 30
  4124.6 1284.48  4168.2 1280.71  4178.6 1276.47  4199.1 1274.35  4393.9 1261.43
  4414.3 1256.42  4506.6 1245.37  4583.8 1240.33    4740 1234.29    4800  1222.5
  4879.8 1215.85    4980 1213.71    4997 1209.72  4999.8 1209.22    5003 1209.72
    5010 1213.31  5033.5 1213.42  5186.5 1212.31  5281.7 1215.84  5310.2 1214.63
  5345.7 1221.46  5368.1 1223.16  5432.9 1233.47  5517.5 1240.82  5540.7 1247.33
  5567.8 1257.94  5611.9  1262.5  5653.7 1269.51  5809.6 1273.97  5996.5 1272.83
#Mann= 8 ,-1 , 0
  4124.6      .1       0  4879.8     .16       0    4997     .07       0
    5003     .16       0  5033.5      .1       0  5186.5     .05       0
  5432.9     .16       0  5809.6      .1       0
Bank Sta=4997,5003
XS Rating Curve= 0 ,0
Exp/Cntr=0.3,0.1

Type RM Length L Ch R = 1 ,20492   ,423,423,423
BEGIN DESCRIPTION:
BROCK HOLLOW 46.0
END DESCRIPTION:
XS GIS Cut Line= 2
      2915218.18     10060547.54       2916958.6     10060182.96
#Sta/Elev= 30
  4041.1 1255.57  4068.7 1253.22  4102.7 1249.28  4215.1  1242.2  4317.3 1237.94
  4347.9 1232.72  4439.9 1228.39  4480.7 1221.15  4511.4 1219.05  4669.6 1213.72
  4736.2 1208.34  4795.8 1206.62  4863.2 1205.96    4909 1205.14  4998.8  1198.3
  5001.5  1197.8  5004.8  1198.3  5042.7 1205.92  5058.8 1207.52  5144.8 1211.48
  5240.2 1218.11  5302.2 1223.24  5403.9 1232.32    5482 1239.56  5542.7  1252.2
  5547.9 1251.89  5563.7 1256.27    5625 1262.58  5665.9 1270.11  5819.3 1279.79
#Mann= 9 ,-1 , 0
  4041.1     .05       0  4068.7      .1       0  4795.8     .05       0
  4863.2      .1       0  4998.8     .07       0  5004.8      .1       0
  5240.2     .05       0  5302.2      .1       0  5403.9     .16       0
Bank Sta=4998.8,5004.8
XS Rating Curve= 0 ,0
Exp/Cntr=0.3,0.1

Type RM Length L Ch R = 1 ,20069   ,387,387,387
BEGIN DESCRIPTION:
BROCK HOLLOW 45.0
END DESCRIPTION:
XS GIS Cut Line= 4
      2915482.94     10060738.52      2916021.09     10060677.76
      2916468.14     10060799.29      2917231.99      10060530.2
#Sta/Elev= 30
  4256.2 1243.89    4378 1230.42  4412.7 1228.55  4483.2 1217.55  4694.7 1206.75
  4718.4 1206.19  4800.9  1202.7  4840.6 1203.17  4875.2 1199.88  4974.7 1196.69
  4991.6 1195.07  4994.4 1194.57  4997.6 1195.07  5043.8 1197.74  5063.8 1203.37
    5069 1201.87  5074.8 1205.32  5095.6 1210.66  5282.6 1214.72  5314.4 1217.13
  5357.6 1224.77  5539.4 1237.33  5651.2 1243.67  5682.1  1247.6  5696.1 1251.74
  5713.1 1252.09  5718.4 1254.73  5823.3 1260.83  5876.3 1270.76  6070.9 1281.49
#Mann= 8 ,-1 , 0
  4256.2      .1       0    4378     .05       0  4694.7      .1       0
  4718.4     .05       0  4974.7      .1       0  4991.6     .07       0
  4997.6      .1       0  5539.4     .16       0
Bank Sta=4991.6,4997.6
XS Rating Curve= 0 ,0
Exp/Cntr=0.3,0.1

Type RM Length L Ch R = 1 ,19682   ,319,319,319
BEGIN DESCRIPTION:
BROCK HOLLOW 44.0
END DESCRIPTION:
XS GIS Cut Line= 4
      2915469.88      10061016.3      2915982.03     10061090.08
      2916624.39     10061055.36      2917153.64     10060981.61
#Sta/Elev= 30
  4125.5 1250.81  4140.9 1246.23  4164.5 1241.61  4245.3 1233.76  4281.7 1228.99
    4316 1226.86  4352.2 1218.63  4386.8  1215.9  4563.4 1206.98  4588.8 1203.72
  4638.6 1200.38  4779.6 1197.04    4849 1193.95  4969.8 1193.14  4996.9 1188.82
  4999.6 1188.32  5002.9 1188.82  5029.9 1190.29  5120.1 1207.59  5258.1 1215.21
  5374.5 1224.02  5419.1 1226.62  5478.2 1233.42  5573.1 1238.77  5621.3 1245.18
  5626.3 1244.32  5643.7 1249.98  5663.9 1253.68  5769.5 1261.72  5820.6 1267.44
#Mann= 6 ,-1 , 0
  4125.5      .1       0  4996.9     .07       0  5002.9      .1       0
  5258.1     .16       0  5374.5      .1       0  5419.1     .16       0
Bank Sta=4996.9,5002.9
XS Rating Curve= 0 ,0
Exp/Cntr=0.3,0.1

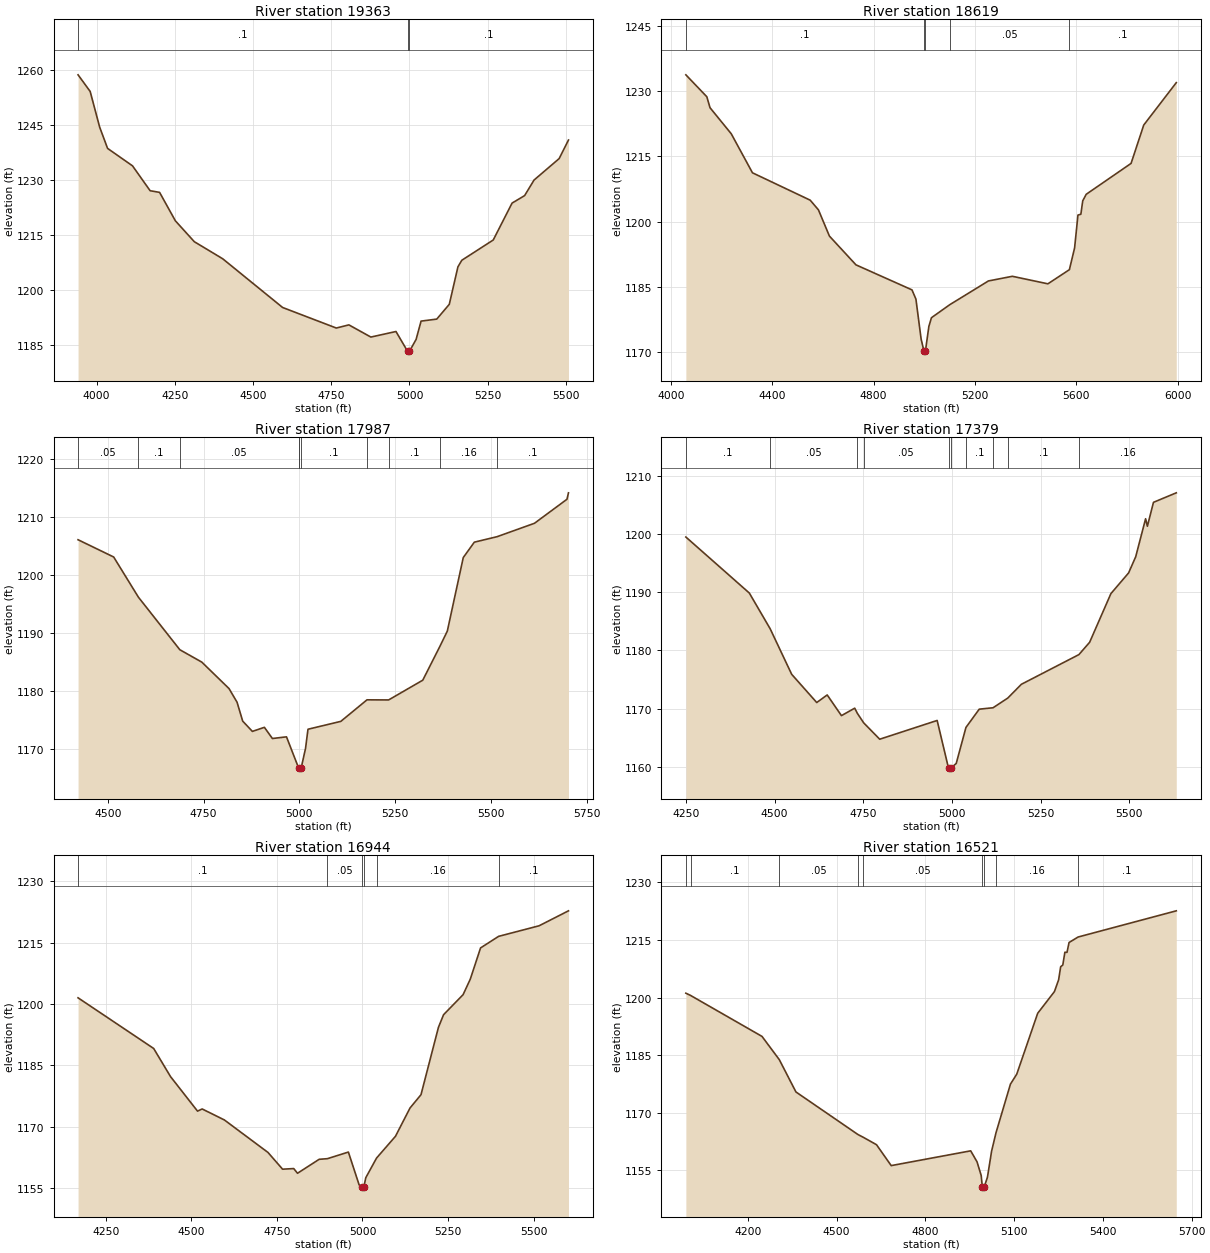
Type RM Length L Ch R = 1 ,19363   ,744,744,744
BEGIN DESCRIPTION:
BROCK HOLLOW 43.0
END DESCRIPTION:
XS GIS Cut Line= 3
      2915370.04     10061276.71       2916216.4     10061385.22
      2916928.21     10061333.14
#Sta/Elev= 30
    3941 1258.72  3979.7 1254.18    4010 1244.43  4035.3 1238.61    4115 1233.84
  4171.3 1227.04  4201.5 1226.59    4252 1218.81  4312.4 1213.11  4403.2 1208.44
  4594.7 1195.12  4766.1 1189.51  4806.4 1190.37  4876.6 1187.04  4956.8 1188.56
  4993.9 1183.15  4996.6 1182.65  4999.9 1183.15  5021.1 1186.39    5037  1191.4
  5087.1 1191.95  5127.2 1195.99  5154.8 1206.24  5167.3 1208.04  5267.6 1213.57
  5327.8 1223.66  5367.9 1225.71    5398 1229.96  5478.2 1235.82    5508  1240.9
#Mann= 3 ,-1 , 0
    3941      .1       0  4993.9     .07       0  4999.9      .1       0
Bank Sta=4993.9,4999.9
XS Rating Curve= 0 ,0
Exp/Cntr=0.3,0.1

Type RM Length L Ch R = 1 ,18619   ,632,632,632
BEGIN DESCRIPTION:
BROCK HOLLOW 42.0
END DESCRIPTION:
XS GIS Cut Line= 4
      2915157.42      10061693.4       2915860.5      10061910.4
      2916654.77     10061745.47      2916941.26     10061485.02
#Sta/Elev= 30
  4059.6 1233.74  4142.3  1228.7  4154.9 1226.18  4238.6 1220.19  4322.3 1211.22
  4549.9 1204.93  4582.5  1202.7  4625.8 1196.67  4730.5 1190.06  4951.4 1184.31
    4967 1182.18  4987.4 1173.03  4998.5 1170.27  5001.3 1169.77  5004.5 1170.27
    5018 1175.91  5028.2 1177.91  5100.1 1180.89  5252.9 1186.36  5347.3 1187.43
  5487.5  1185.7  5572.2 1188.95  5592.8 1193.96    5606  1201.5  5617.5  1201.7
  5624.9 1204.78  5638.6 1206.28  5815.5 1213.38  5865.5  1222.2  5993.8 1231.94
#Mann= 5 ,-1 , 0
  4059.6      .1       0  4998.5     .07       0  5004.5      .1       0
  5100.1     .05       0  5572.2      .1       0
Bank Sta=4998.5,5004.5
XS Rating Curve= 0 ,0
Exp/Cntr=0.3,0.1

Type RM Length L Ch R = 1 ,17987   ,608,608,608
BEGIN DESCRIPTION:
BROCK HOLLOW 41.0
END DESCRIPTION:
XS GIS Cut Line= 3
      2916047.11      10062652.6      2916416.06     10062383.49
      2916927.46     10061737.73
#Sta/Elev= 30
  4422.5 1206.08  4515.5  1203.1  4580.1 1196.16  4688.2 1187.09  4745.6 1184.95
  4816.7 1180.38  4837.6 1178.03  4852.3 1174.77  4877.6 1172.99    4909 1173.69
  4929.9 1171.76  4966.7 1172.05  4998.3 1166.68  4998.9 1166.63  5001.7 1166.13
  5004.9 1166.63  5016.4 1170.05  5022.8 1173.36  5108.5 1174.72  5176.9 1178.44
  5233.3 1178.42  5322.5 1181.83  5367.8 1187.75  5386.6 1190.31  5428.2    1203
  5457.1 1205.66  5516.6 1206.61  5614.1 1208.92    5699 1213.07  5702.9 1214.18
#Mann= 10 ,-1 , 0
  4422.5     .05       0  4580.1      .1       0  4688.2     .05       0
  4998.3      .1       0  4998.9     .07       0  5004.9      .1       0
  5176.9     .05       0  5233.3      .1       0  5367.8     .16       0
  5516.6      .1       0
Bank Sta=4998.9,5004.9
XS Rating Curve= 0 ,0
Exp/Cntr=0.3,0.1

Type RM Length L Ch R = 1 ,17379   ,435,435,435
BEGIN DESCRIPTION:
BROCK HOLLOW 39.0
END DESCRIPTION:
XS GIS Cut Line= 3
      2916724.23     10063260.18      2917093.14     10062353.11
      2917106.16     10061949.44
#Sta/Elev= 30
  4249.7 1199.45  4428.7 1189.83  4487.5 1183.69  4548.1 1175.88  4618.8 1171.03
  4648.3 1172.33  4688.5 1168.78  4725.9 1170.06  4733.5 1169.16  4751.2 1167.54
  4796.4 1164.73  4958.4 1167.95  4990.5 1159.75  4993.3 1159.25  4996.5 1159.75
  5012.2 1160.57  5039.6 1166.75  5077.1 1169.89    5116 1170.13  5157.5 1171.79
  5195.9 1174.16  5358.2 1179.26  5388.4 1181.37  5448.4 1189.73  5498.4 1193.29
  5518.4 1196.07  5546.3 1202.59  5551.3  1201.3  5568.5 1205.41  5632.8 1207.04
#Mann= 10 ,-1 , 0
  4249.7      .1       0  4487.5     .05       0  4733.5      .1       0
  4751.2     .05       0  4990.5    .035       0  4996.5     .05       0
  5039.6      .1       0    5116     .05       0  5157.5      .1       0
  5358.2     .16       0
Bank Sta=4990.5,4996.5
XS Rating Curve= 0 ,0
Exp/Cntr=0.3,0.1

Type RM Length L Ch R = 1 ,16944   ,423,423,423
BEGIN DESCRIPTION:
BROCK HOLLOW 38.0
END DESCRIPTION:
XS GIS Cut Line= 4
      2916802.32     10063429.52      2917262.41     10063038.87
      2917392.62     10062674.29      2917760.13     10062427.84
#Sta/Elev= 30
  4168.8 1201.53  4389.8 1189.13  4439.2 1182.23  4517.9  1173.8  4531.5 1174.33
  4596.4 1171.64  4723.8 1163.69  4766.5 1159.59  4799.1 1159.74  4810.1 1158.59
  4873.4 1162.01  4897.4 1162.16  4958.8 1163.78  4990.2 1155.75  4997.8 1155.21
  5000.6 1154.71  5003.8 1155.21  5009.7 1157.51  5041.2 1162.32  5096.4 1167.64
  5138.9 1174.56    5171 1177.82    5222 1194.31    5237  1197.4  5294.1 1202.31
  5315.1 1206.11  5345.1 1213.74  5397.8 1216.57  5516.2 1219.16    5602 1222.82
#Mann= 6 ,-1 , 0
  4168.8      .1       0  4897.4     .05       0  4997.8    .035       0
  5003.8     .05       0  5041.2     .16       0  5397.8      .1       0
Bank Sta=4997.8,5003.8
XS Rating Curve= 0 ,0
Exp/Cntr=0.3,0.1

Type RM Length L Ch R = 1 ,16521   ,757,757,757
BEGIN DESCRIPTION:
BROCK HOLLOW 37.0
END DESCRIPTION:
XS GIS Cut Line= 4
      2916880.49     10063542.34      2917245.05     10063464.22
      2917930.81     10062808.83       2918091.4     10062513.71
#Sta/Elev= 30
  3990.7 1201.13  4006.5 1200.55    4248 1189.87  4306.4 1183.82  4362.7 1175.39
  4572.3 1164.29  4590.3 1163.57    4635 1161.64  4684.7 1156.19  4953.3 1160.04
  4974.7 1157.18  4988.8 1153.62  4992.7 1150.56  4995.5 1150.06  4998.7 1150.56
  5009.9 1153.16    5024 1159.97  5038.8 1164.74  5087.6 1177.42    5109 1180.03
  5179.7 1195.89  5236.3 1201.55  5250.5 1204.63  5257.4 1208.03  5264.6 1208.47
  5271.6  1211.8  5278.8 1211.77  5285.7 1214.34  5316.2 1215.77  5648.1  1222.6
#Mann= 9 ,-1 , 0
  3990.7     .05       0  4006.5      .1       0  4306.4     .05       0
  4572.3      .1       0  4590.3     .05       0  4992.7    .035       0
  4998.7     .05       0  5038.8     .16       0  5316.2      .1       0
Bank Sta=4992.7,4998.7
XS Rating Curve= 0 ,0
Exp/Cntr=0.3,0.1

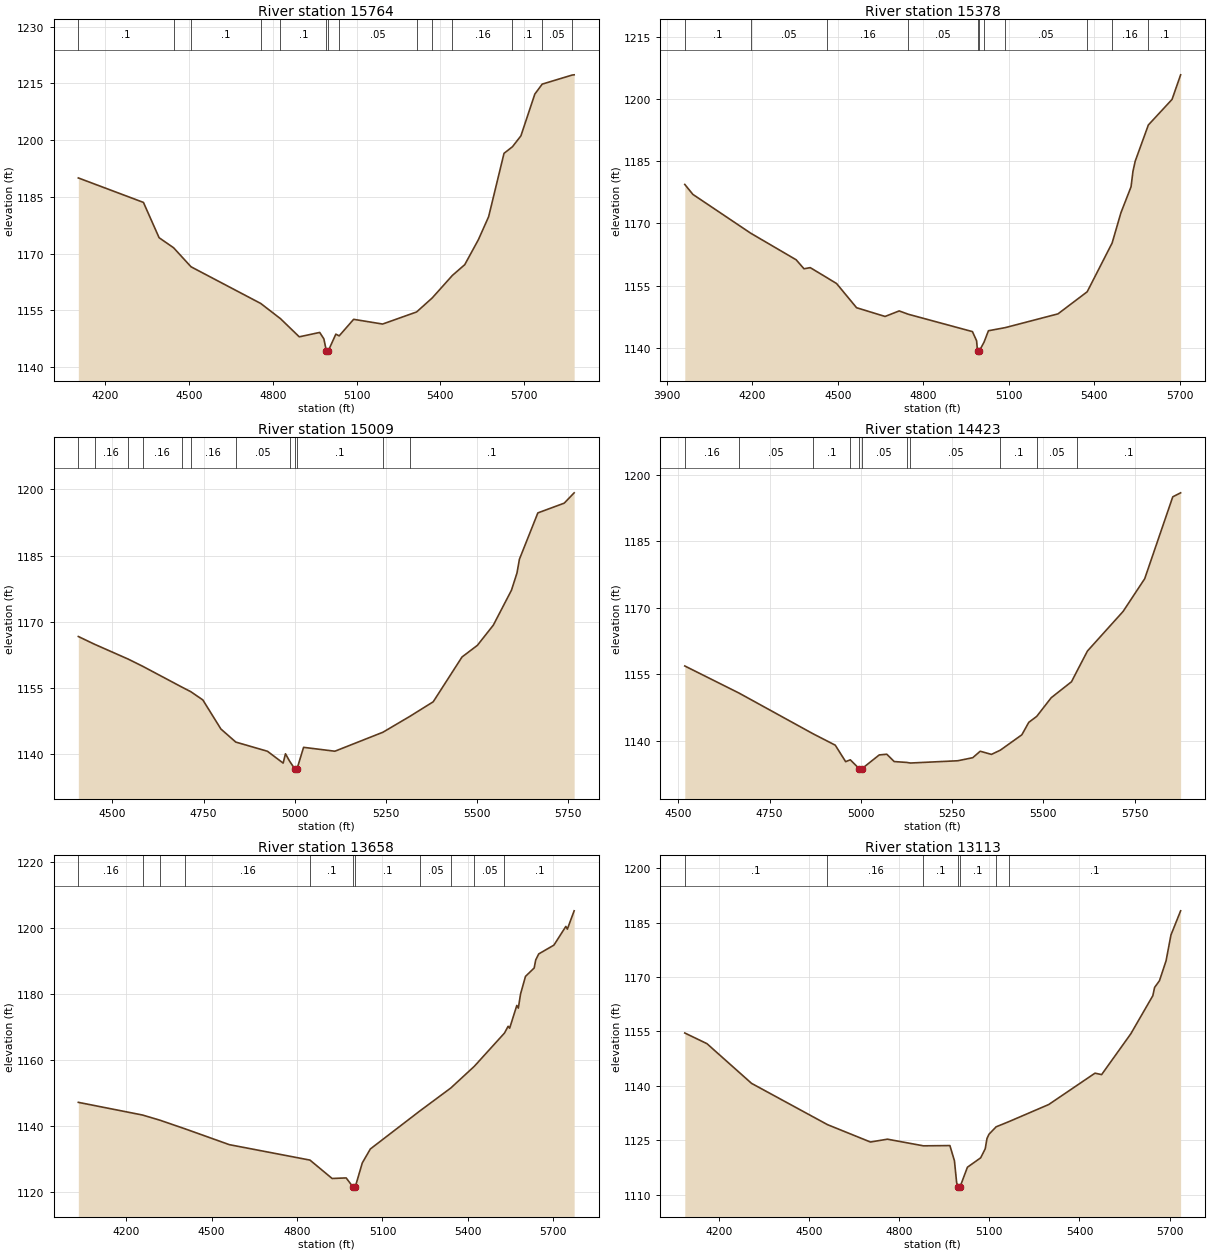
Type RM Length L Ch R = 1 ,15764   ,386,386,386
BEGIN DESCRIPTION:
BROCK HOLLOW 35.0
END DESCRIPTION:
XS GIS Cut Line= 4
      2917067.08     10063902.59      2917657.38     10063833.14
      2918260.68     10063455.54      2918699.08     10063290.59
#Sta/Elev= 30
  4104.4 1189.99  4337.4 1183.52  4393.5 1174.18  4445.4 1171.52  4507.8 1166.49
  4757.1  1156.8  4827.9 1152.77  4895.1 1147.97  4968.2 1149.13  4983.2 1147.43
  4992.3 1144.16  4995.1 1143.66  4998.3 1144.16    5026 1148.68  5037.9 1148.22
  5089.7  1152.6  5193.4 1151.35  5315.1 1154.55    5371 1158.26  5443.1 1164.21
  5487.4 1167.06  5536.3 1173.68  5572.8 1179.74  5627.9  1196.5  5658.2 1198.25
  5688.3 1201.12  5738.1 1212.16  5764.5  1214.8  5871.7  1217.2  5878.9 1217.26
#Mann= 14 ,-1 , 0
  4104.4      .1       0  4445.4     .05       0  4507.8      .1       0
  4757.1     .05       0  4827.9      .1       0  4992.3     .07       0
  4998.3      .1       0  5037.9     .05       0  5315.1     .16       0
    5371     .05       0  5443.1     .16       0  5658.2      .1       0
  5764.5     .05       0  5871.7      .1       0
Bank Sta=4992.3,4998.3
XS Rating Curve= 0 ,0
Exp/Cntr=0.3,0.1

Type RM Length L Ch R = 1 ,15378   ,369,369,369
BEGIN DESCRIPTION:
BROCK HOLLOW 34.0
END DESCRIPTION:
XS GIS Cut Line= 3
      2917279.74     10064675.18      2917926.47     10064128.28
      2918642.61     10063594.43
#Sta/Elev= 30
  3962.7  1179.4    3991 1177.01  4193.6 1167.68  4353.6 1161.26    4381  1159.1
    4403 1159.37  4461.2 1156.97  4495.3 1155.55  4565.6 1149.72  4665.6 1147.62
  4715.1 1148.95  4747.6 1148.14  4972.2 1143.97  4986.8 1141.78    4990 1139.29
  4992.7 1138.79    4996 1139.29  5012.7 1141.39  5028.4 1144.18  5087.5 1144.93
  5272.4 1148.24    5375 1153.56  5462.5  1165.3  5493.4 1172.59  5528.9 1178.83
  5535.6 1182.55  5543.5    1185  5589.6 1193.71  5672.8 1199.87  5702.9 1205.79
#Mann= 11 ,-1 , 0
  3962.7      .1       0  4193.6     .05       0  4461.2     .16       0
  4747.6     .05       0    4990    .035       0    4996     .05       0
  5012.7      .1       0  5087.5     .05       0    5375      .1       0
  5462.5     .16       0  5589.6      .1       0
Bank Sta=4990,4996
XS Rating Curve= 0 ,0
Exp/Cntr=0.3,0.1

Type RM Length L Ch R = 1 ,15009   ,586,586,586
BEGIN DESCRIPTION:
BROCK HOLLOW 33.0
END DESCRIPTION:
XS GIS Cut Line= 3
      2917809.28     10064705.54      2918612.24     10064050.15
      2918789.53     10063777.73
#Sta/Elev= 30
  4406.2 1166.67  4450.8 1164.91  4542.9 1161.56  4582.8 1159.93  4690.7  1155.2
  4714.8 1154.18  4748.1  1152.3  4797.7 1145.71  4838.6 1142.75  4925.5 1140.67
  4968.6 1137.99    4975  1140.1  4986.4 1138.42  5000.7 1136.67  5003.5 1136.17
  5006.7 1136.67  5024.7 1141.56  5110.7 1140.68  5242.6 1144.98  5317.2 1148.61
  5380.7 1151.88  5459.8 1162.03    5502 1164.67  5545.8 1169.25  5595.5 1177.15
  5610.7 1181.05  5617.4 1184.17    5668 1194.67  5740.4 1196.88  5767.7 1199.22
#Mann= 12 ,-1 , 0
  4406.2     .05       0  4450.8     .16       0  4542.9      .1       0
  4582.8     .16       0  4690.7      .1       0  4714.8     .16       0
  4838.6     .05       0  4986.4      .1       0  5000.7     .07       0
  5006.7      .1       0  5242.6     .05       0  5317.2      .1       0
Bank Sta=5000.7,5006.7
XS Rating Curve= 0 ,0
Exp/Cntr=0.3,0.1

Type RM Length L Ch R = 1 ,14423   ,765,765,765
BEGIN DESCRIPTION:
BROCK HOLLOW 32.0
END DESCRIPTION:
XS GIS Cut Line= 3
      2918482.02     10065165.62      2918638.28     10064918.21
      2918868.08      10063877.6
#Sta/Elev= 30
  4517.8 1156.88  4666.4 1150.76  4869.9 1141.54    4930    1139  4958.4 1135.28
  4971.2 1135.69  4996.3 1133.64  4999.1 1133.14  5002.3 1133.64  5050.5  1136.8
  5071.2 1136.95  5091.5  1135.3    5126  1135.1  5135.9 1134.97  5265.6 1135.48
  5306.6 1136.17  5327.1 1137.63  5357.8 1136.92    5382 1137.86  5441.1 1141.34
  5460.2 1144.16  5481.8 1145.49  5521.6 1149.71  5577.2 1153.32    5593 1155.85
  5620.9 1160.26  5718.5 1169.19  5777.7 1176.58  5854.6 1195.07  5876.1 1195.97
#Mann= 11 ,-1 , 0
  4517.8     .16       0  4666.4     .05       0  4869.9      .1       0
  4971.2     .05       0  4996.3    .035       0  5002.3     .05       0
    5126      .1       0  5135.9     .05       0    5382      .1       0
  5481.8     .05       0    5593      .1       0
Bank Sta=4996.3,5002.3
XS Rating Curve= 0 ,0
Exp/Cntr=0.3,0.1

Type RM Length L Ch R = 1 ,13658   ,545,545,545
BEGIN DESCRIPTION:
BROCK HOLLOW 30.0
END DESCRIPTION:
XS GIS Cut Line= 3
      2918646.96     10065252.41      2919445.57      10064475.5
      2919661.94     10063886.98
#Sta/Elev= 30
  4031.9 1147.13  4257.4 1143.28  4318.8  1141.7    4407 1139.08  4562.5 1134.28
  4845.4  1129.6  4923.1 1124.02  4972.5 1124.19  4997.8 1121.29  5000.6 1120.79
  5003.8 1121.29  5029.1 1128.75  5057.4 1132.98  5231.5 1144.53  5339.9 1151.48
  5422.4 1158.06  5528.4 1168.16  5541.3 1170.22  5546.6 1169.64  5571.7 1176.54
  5577.1 1175.73  5584.8    1180  5602.2 1185.36  5632.7 1187.91  5638.1 1190.34
  5648.7 1192.18    5702 1194.85  5743.9 1200.52  5749.2 1199.71  5773.1 1205.26
#Mann= 11 ,-1 , 0
  4031.9     .16       0  4257.4      .1       0  4318.8     .05       0
    4407     .16       0  4845.4      .1       0  4997.8     .07       0
  5003.8      .1       0  5231.5     .05       0  5339.9      .1       0
  5422.4     .05       0  5528.4      .1       0
Bank Sta=4997.8,5003.8
XS Rating Curve= 0 ,0
Exp/Cntr=0.3,0.1

Type RM Length L Ch R = 1 ,13113   ,404,404,404
BEGIN DESCRIPTION:
BROCK HOLLOW 29.0
END DESCRIPTION:
XS GIS Cut Line= 4
      2919133.05     10065612.67      2919623.52     10065117.86
       2919857.9     10064761.96      2920325.07     10064515.39
#Sta/Elev= 30
  4085.7 1154.58  4159.5 1151.64    4308  1140.7  4560.8 1129.33  4703.9 1124.54
  4760.5 1125.32  4880.2 1123.49  4968.5 1123.56  4983.6 1119.39  4990.9  1113.4
  4995.7 1112.06  4998.4 1111.56  5001.7 1112.06  5026.8 1117.59    5071 1120.19
  5086.1 1122.67    5092 1125.52  5098.7 1126.69  5122.5 1128.73  5164.2 1130.13
  5297.6 1134.87  5451.7 1143.51  5473.7 1143.11    5571 1154.37  5644.2 1164.85
  5650.2 1167.14  5666.3 1168.98  5688.3 1174.46  5704.6 1181.58  5736.8 1188.24
#Mann= 7 ,-1 , 0
  4085.7      .1       0  4560.8     .16       0  4880.2      .1       0
  4995.7     .07       0  5001.7      .1       0  5122.5     .16       0
  5164.2      .1       0
Bank Sta=4995.7,5001.7
XS Rating Curve= 0 ,0
Exp/Cntr=0.3,0.1

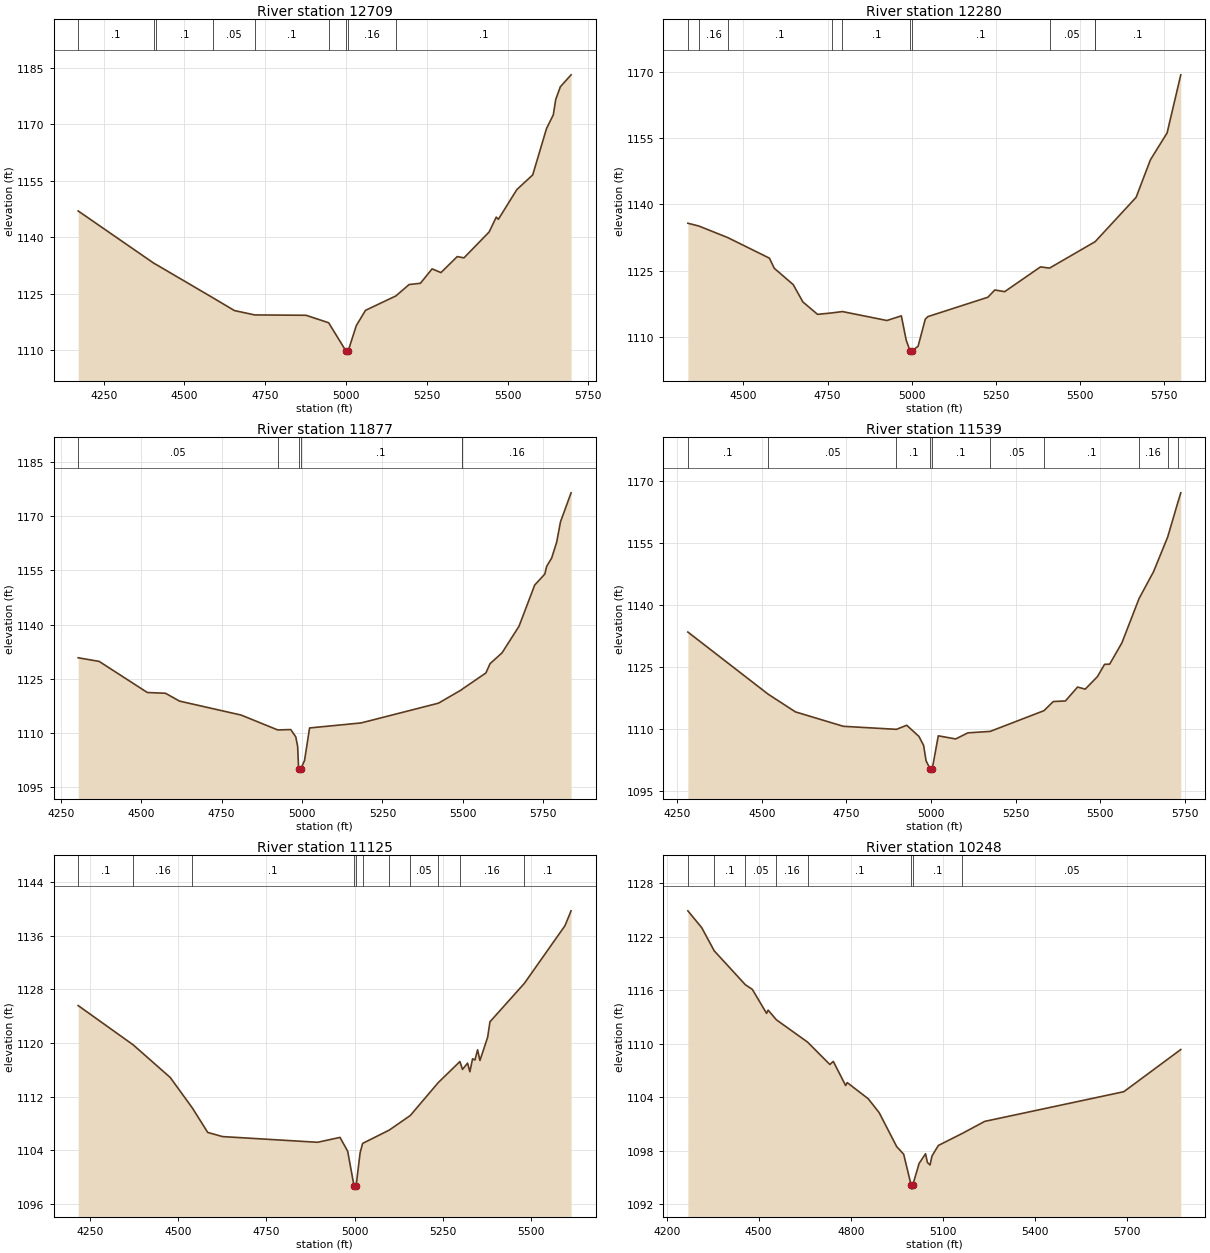
Type RM Length L Ch R = 1 ,12709   ,429,429,429
BEGIN DESCRIPTION:
BROCK HOLLOW 28.0
END DESCRIPTION:
XS GIS Cut Line= 3
      2919380.51     10065699.44      2919853.56       10065413.
      2920491.59     10064679.48
#Sta/Elev= 30
  4171.2 1146.99  4406.2 1133.04  4410.9 1132.83  4588.3 1123.89  4654.6  1120.5
  4717.7 1119.34  4876.1 1119.25  4946.2 1117.26  5000.3 1109.68    5003 1109.18
  5006.3 1109.68  5031.8  1116.5  5060.3 1120.56  5154.4  1124.4  5195.1 1127.42
  5230.2 1127.76  5266.3 1131.59  5293.8  1130.6  5344.2 1134.86    5365 1134.52
  5442.9 1141.41  5464.8 1145.35  5471.4 1144.78  5528.4 1152.66  5577.7 1156.59
  5620.5 1168.94  5641.3 1172.54    5649 1176.68  5663.2 1180.03  5696.4  1183.2
#Mann= 9 ,-1 , 0
  4171.2      .1       0  4406.2     .16       0  4410.9      .1       0
  4588.3     .05       0  4717.7      .1       0  4946.2     .16       0
  5000.3     .07       0  5006.3     .16       0  5154.4      .1       0
Bank Sta=5000.3,5006.3
XS Rating Curve= 0 ,0
Exp/Cntr=0.3,0.1

Type RM Length L Ch R = 1 ,12280   ,403,403,403
BEGIN DESCRIPTION:
BROCK HOLLOW 27.0
END DESCRIPTION:
XS GIS Cut Line= 3
      2919732.04     10065977.23      2920574.04     10065321.86
      2920873.47     10065061.48
#Sta/Elev= 30
  4334.9 1135.74  4367.6 1135.11  4453.7 1132.48  4577.1 1127.84  4591.5 1125.55
  4647.7 1121.86  4676.6 1117.93    4720 1115.13  4761.9 1115.45    4794 1115.76
    4926 1113.74  4968.9 1114.79  4983.3  1109.3  4994.8 1106.86  4997.6 1106.36
  5000.8 1106.86  5018.6 1107.92    5040 1114.04  5047.6 1114.62  5225.8    1119
  5246.6 1120.65  5275.6 1120.26  5382.2 1125.87  5408.9 1125.59  5544.2 1131.56
  5544.7 1131.59    5666 1141.59  5708.7 1150.11  5758.1 1156.16  5798.7 1169.31
#Mann= 10 ,-1 , 0
  4334.9      .1       0  4367.6     .16       0  4453.7      .1       0
  4761.9     .05       0    4794      .1       0  4994.8     .07       0
  5000.8      .1       0  5408.9     .05       0  5544.2     .16       0
  5544.7      .1       0
Bank Sta=4994.8,5000.8
XS Rating Curve= 0 ,0
Exp/Cntr=0.3,0.1

Type RM Length L Ch R = 1 ,11877   ,338,338,338
BEGIN DESCRIPTION:
BROCK HOLLOW 26.0
END DESCRIPTION:
XS GIS Cut Line= 3
      2920014.18      10066320.1      2920435.15     10066003.28
      2920942.99     10065135.19
#Sta/Elev= 30
  4303.9 1130.82  4369.1 1129.82  4519.1 1121.22  4575.3 1121.02    4619 1118.85
  4810.6 1114.99  4924.4 1110.88  4964.8 1110.99  4980.5 1108.96  4986.3 1106.34
  4989.4    1100  4992.2  1099.5  4995.4    1100  5007.7 1102.43  5023.4 1111.43
  5183.8 1112.82  5424.2 1118.28  5496.1 1121.99  5497.8 1122.14  5571.7 1126.63
  5584.5 1129.19  5621.7 1132.17  5674.6 1139.53  5723.4 1150.92  5754.8 1153.95
  5760.6 1156.09  5776.2  1158.4  5791.8 1162.79  5803.5 1168.37  5836.5  1176.4
#Mann= 6 ,-1 , 0
  4303.9     .05       0  4924.4      .1       0  4989.4     .07       0
  4995.4      .1       0  5496.1     .05       0  5497.8     .16       0
Bank Sta=4989.4,4995.4
XS Rating Curve= 0 ,0
Exp/Cntr=0.3,0.1

Type RM Length L Ch R = 1 ,11539   ,414,414,414
BEGIN DESCRIPTION:
BROCK HOLLOW 25.0
END DESCRIPTION:
XS GIS Cut Line= 3
      2920287.58     10066571.86      2920678.21     10066211.61
      2921186.02     10065439.05
#Sta/Elev= 30
  4281.9 1133.48  4519.1 1118.43  4599.5 1114.15  4741.3 1110.65  4898.1 1109.92
  4928.3 1110.91  4964.4 1108.21  4978.3 1106.02  4985.5 1102.32  4997.6  1100.3
  5000.3  1099.8  5003.6  1100.3  5021.6 1108.35  5072.9 1107.59    5109 1109.07
  5174.9 1109.42  5333.7 1114.44  5361.2 1116.65  5397.1 1116.79    5433 1120.16
  5455.5 1119.65  5491.7 1122.69  5512.7 1125.66  5527.8 1125.71    5564 1130.88
  5614.5 1141.57  5657.4  1148.1  5699.1 1156.48    5729 1164.82  5737.8 1167.19
#Mann= 10 ,-1 , 0
  4281.9      .1       0  4519.1     .05       0  4898.1      .1       0
  4997.6     .07       0  5003.6      .1       0  5174.9     .05       0
  5333.7      .1       0  5614.5     .16       0  5699.1      .1       0
    5729     .16       0
Bank Sta=4997.6,5003.6
XS Rating Curve= 0 ,0
Exp/Cntr=0.3,0.1

Type RM Length L Ch R = 1 ,11125   ,877,877,877
BEGIN DESCRIPTION:
BROCK HOLLOW 24.0
END DESCRIPTION:
XS GIS Cut Line= 2
      2920617.42      10066810.6      2921536.34     10065757.31
#Sta/Elev= 30
  4216.4 1125.59  4372.4 1119.74  4477.6 1114.87  4540.2 1110.33  4583.8 1106.69
  4625.7 1106.07  4895.3 1105.22  4958.9 1105.95  4980.7 1103.88  4998.6 1098.74
  5001.4 1098.24  5004.6 1098.74  5015.9 1103.65    5023 1105.05  5098.3 1107.03
  5158.2 1109.21  5237.6 1114.12  5298.9 1117.25  5306.3 1116.08  5320.6 1117.02
  5327.2 1115.73  5334.8 1117.66  5341.5 1117.48  5349.1    1119  5355.7 1117.41
  5377.5 1120.86  5384.2 1123.18  5481.7  1128.9  5596.8 1137.49  5614.2 1139.71
#Mann= 11 ,-1 , 0
  4216.4      .1       0  4372.4     .16       0  4540.2      .1       0
  4998.6     .07       0  5004.6      .1       0    5023     .05       0
  5098.3      .1       0  5158.2     .05       0  5237.6      .1       0
  5298.9     .16       0  5481.7      .1       0
Bank Sta=4998.6,5004.6
XS Rating Curve= 0 ,0
Exp/Cntr=0.3,0.1

Type RM Length L Ch R = 1 ,10248   ,382,382,382
BEGIN DESCRIPTION:
BROCK HOLLOW 23.0
END DESCRIPTION:
XS GIS Cut Line= 4
      2920613.09     10067188.18      2921146.96     10067084.01
      2921554.95     10066793.21      2921702.52     10066250.68
#Sta/Elev= 30
  4269.1 1124.89  4314.3    1123  4355.1  1120.4  4456.5  1116.6  4479.3 1116.08
  4525.7 1113.39  4530.8 1113.75  4557.9 1112.66  4659.2 1110.17  4732.1 1107.65
  4743.3    1108  4783.6 1105.29  4788.7 1105.62  4857.2 1103.81  4892.9 1102.25
    4950 1098.44  4972.8 1097.58  4996.8 1094.17  4999.6 1093.67  5002.8 1094.17
  5023.2 1096.56  5044.1 1097.64  5050.2 1096.66  5058.8 1096.38    5065 1097.38
  5085.9 1098.57    5164 1099.92  5237.1 1101.27  5690.6  1104.6  5876.3 1109.33
#Mann= 8 ,-1 , 0
  4269.1     .16       0  4355.1      .1       0  4456.5     .05       0
  4557.9     .16       0  4659.2      .1       0  4996.8     .07       0
  5002.8      .1       0    5164     .05       0
Bank Sta=4996.8,5002.8
XS Rating Curve= 0 ,0
Exp/Cntr=0.3,0.1