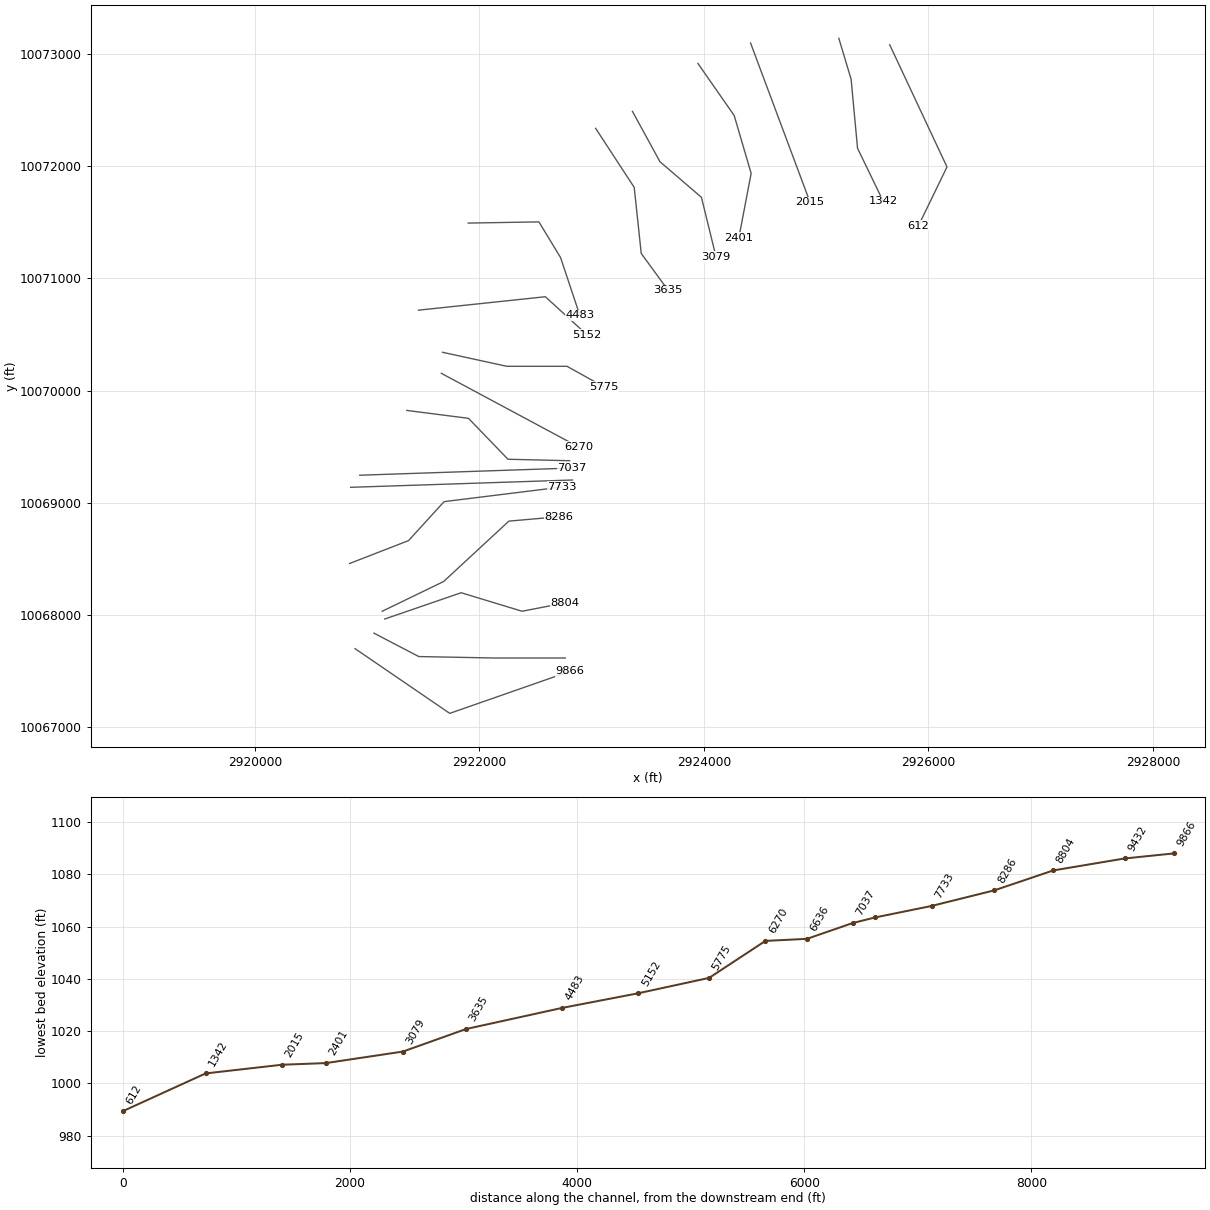
HEC-RAS study BROCK HOLLOW.prj: BROCK HOLLOW Base Level Engineering

--- BROCK HOLLOW.g01 (geometry) --- (continued)

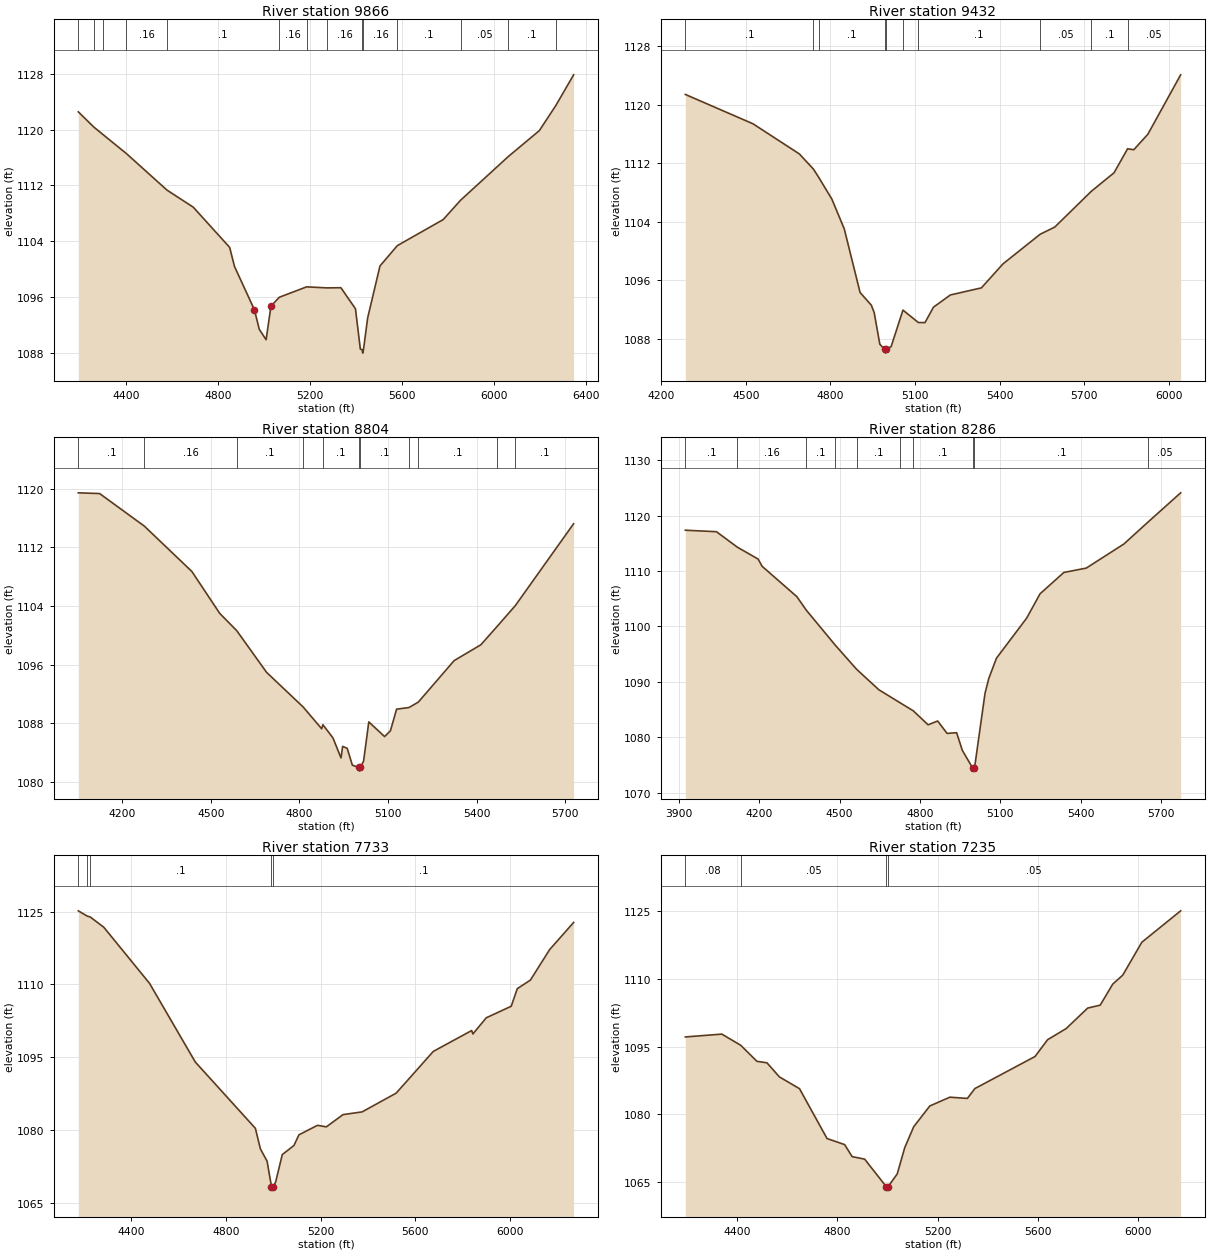
Type RM Length L Ch R = 1 ,9866    ,434,434,434
BEGIN DESCRIPTION:
BROCK HOLLOW 22.0
END DESCRIPTION:
XS GIS Cut Line= 3
      2920891.62     10067701.38      2921735.23     10067124.61
      2922804.06     10067497.98
#Sta/Elev= 30
  4193.2 1122.54  4260.7 1120.36  4300.5 1119.29  4401.8 1116.58    4579 1111.33
  4693.1 1108.89  4851.5 1103.13  4872.5  1100.4  4959.2 1094.19  4980.2  1091.4
    5010 1089.91    5031 1094.71  5067.3 1095.99  5186.2 1097.48    5275 1097.33
  5335.1 1097.36  5398.6 1094.34  5419.8 1088.57  5427.4 1088.49  5430.2 1087.99
  5433.4 1088.49  5451.6 1093.03  5505.2 1100.47  5580.5 1103.38    5780 1107.11
  5855.9 1109.89  6063.6 1116.15  6198.2 1119.85  6269.7 1123.43  6347.3 1127.84
#Mann= 14 ,-1 , 0
  4193.2      .1       0  4260.7     .16       0  4300.5      .1       0
  4401.8     .16       0    4579      .1       0  5067.3     .16       0
  5186.2     .05       0    5275     .16       0  5427.4     .07       0
  5433.4     .16       0  5580.5      .1       0  5855.9     .05       0
  6063.6      .1       0  6269.7     .05       0
#XS Ineff= 1 ,-1
 5216.84 5553.57 1097.28
Permanent Ineff=
       T
Bank Sta=4959.2,5031
XS Rating Curve= 0 ,0
Exp/Cntr=0.3,0.1

Type RM Length L Ch R = 1 ,9432    ,628,628,628
BEGIN DESCRIPTION:
BROCK HOLLOW 21.0
END DESCRIPTION:
XS GIS Cut Line= 4
      2921060.16     10067839.21      2921459.46     10067630.88
      2922136.54     10067617.86      2922764.66     10067617.86
#Sta/Elev= 30
  4285.6 1121.41  4525.3  1117.4  4689.7 1113.28  4739.5 1111.21  4758.7 1110.06
    4805  1107.1  4848.9 1103.04    4905 1094.34    4945  1092.6    4955 1091.59
    4975 1087.27    4992 1086.55  4994.8 1086.05    4998 1086.55    5015 1086.94
    5057 1091.93  5111.4 1090.24  5135.1 1090.22  5165.1 1092.33  5225.1    1094
  5335.1 1094.97  5411.6 1098.25  5543.3  1102.3  5595.1 1103.28  5724.4 1108.16
  5805.1  1110.7  5853.3 1113.98  5875.1 1113.85  5925.1 1115.97  6041.3 1124.09
#Mann= 10 ,-1 , 0
  4285.6      .1       0  4739.5     .16       0  4758.7      .1       0
    4992     .07       0    4998      .1       0    5057     .05       0
  5111.4      .1       0  5543.3     .05       0  5724.4      .1       0
  5853.3     .05       0
Bank Sta=4992,4998
XS Rating Curve= 0 ,0
Exp/Cntr=0.3,0.1

Type RM Length L Ch R = 1 ,8804    ,518,518,518
BEGIN DESCRIPTION:
BROCK HOLLOW 20.0
END DESCRIPTION:
XS GIS Cut Line= 4
      2921155.68      10067965.1      2921837.06     10068199.46
       2922379.6     10068034.53      2922761.53     10068108.31
#Sta/Elev= 30
  4051.9 1119.46  4124.1 1119.36  4275.6 1114.91  4436.4 1108.72  4530.7    1103
  4588.3 1100.64  4689.3 1094.95  4813.2 1090.22  4875.7 1087.25  4879.8 1087.81
  4913.8 1086.01  4941.2 1083.27  4946.6 1084.85  4962.1 1084.58  4979.5 1082.29
  5000.9 1081.97  5003.6 1081.47  5006.9 1081.97  5017.6 1082.85  5035.2 1088.19
  5088.6 1086.19  5108.4 1086.97  5129.3 1089.93    5171 1090.15  5202.8 1090.89
  5323.9 1096.55  5414.6 1098.72  5469.3 1101.21  5531.3 1104.07  5728.5 1115.24
#Mann= 11 ,-1 , 0
  4051.9      .1       0  4275.6     .16       0  4588.3      .1       0
  4813.2     .05       0  4879.8      .1       0  5000.9     .07       0
  5006.9      .1       0    5171     .05       0  5202.8      .1       0
  5469.3     .05       0  5531.3      .1       0
Bank Sta=5000.9,5006.9
XS Rating Curve= 0 ,0
Exp/Cntr=0.3,0.1

Type RM Length L Ch R = 1 ,8286    ,553,553,553
BEGIN DESCRIPTION:
BROCK HOLLOW 19.0
END DESCRIPTION:
XS GIS Cut Line= 4
      2921133.91     10068034.51      2921680.81     10068299.29
      2922262.41     10068837.48      2922709.48     10068876.54
#Sta/Elev= 30
  3924.3 1117.36  4040.5 1117.09  4118.1 1114.31    4196 1112.15    4211 1110.84
  4340.4 1105.37  4375.9 1102.92  4483.3 1096.64  4563.6 1092.25  4646.7 1088.55
  4727.3 1086.16  4775.1 1084.75  4830.4 1082.23  4866.1 1082.91  4901.3 1080.67
    4937  1080.8    4958 1077.63  4997.5 1074.36  5000.3 1073.86  5003.5 1074.36
    5043 1087.94  5057.2 1090.62  5085.6 1094.25  5198.4 1101.49  5248.3 1105.88
  5337.1 1109.73  5420.8 1110.52  5561.3 1114.87    5652 1118.86  5773.1 1124.11
#Mann= 10 ,-1 , 0
  3924.3      .1       0  4118.1     .16       0  4375.9      .1       0
  4483.3     .05       0  4563.6      .1       0  4727.3     .05       0
  4775.1      .1       0  4997.5     .07       0  5003.5      .1       0
    5652     .05       0
Bank Sta=4997.5,5003.5
XS Rating Curve= 0 ,0
Exp/Cntr=0.3,0.1

Type RM Length L Ch R = 1 ,7733    ,498,498,498
BEGIN DESCRIPTION:
BROCK HOLLOW 18.0
END DESCRIPTION:
XS GIS Cut Line= 4
      2920843.13     10068459.87      2921368.31     10068663.87
      2921685.15     10069011.09      2922734.46     10069141.17
#Sta/Elev= 30
  4177.1 1125.14  4215.5 1124.04  4227.3 1123.88  4284.6 1121.77  4477.8 1110.22
    4671 1094.03  4924.6 1080.39  4945.6 1076.18    4974 1073.63  4992.6 1068.38
  4995.3 1067.88  4998.6 1068.38  5009.8 1069.29  5038.1 1074.98  5087.5 1076.87
  5108.4 1079.05  5186.8 1081.01    5224 1080.69  5294.5 1083.21  5375.1 1083.77
  5518.9 1087.63  5675.7 1096.22  5837.6 1100.51  5842.7  1099.8  5899.1 1103.13
  6004.6 1105.51  6030.1 1109.12  6085.5 1110.89  6166.5 1117.15  6267.9 1122.75
#Mann= 5 ,-1 , 0
  4177.1      .1       0  4215.5     .16       0  4227.3      .1       0
  4992.6     .07       0  4998.6      .1       0
Bank Sta=4992.6,4998.6
XS Rating Curve= 0 ,0
Exp/Cntr=0.3,0.1

Type RM Length L Ch R = 1 ,7235    ,198,198,198
BEGIN DESCRIPTION:
BROCK HOLLOW 17.0
END DESCRIPTION:
XS GIS Cut Line= 2
      2920852.86     10069138.69      2922829.49      10069203.8
#Sta/Elev= 30
  4192.8 1097.12  4338.5 1097.75    4414 1095.28  4478.6 1091.73  4518.6 1091.41
  4568.6 1088.28  4648.7 1085.68  4758.7 1074.65  4828.8 1073.32  4858.8 1070.66
  4908.8  1070.1  4995.8 1063.97  4998.6 1063.47  5001.8 1063.97  5038.9 1066.84
  5068.9 1072.65  5104.6 1077.26  5168.9 1081.86    5249  1083.8    5319 1083.53
    5349 1085.71  5589.2  1092.8  5639.2 1096.51  5713.5 1098.98  5799.3 1103.51
  5849.3 1104.15  5899.3  1108.8  5939.4 1110.79  6015.5 1118.06  6170.5 1125.01
#Mann= 4 ,-1 , 0
  4192.8     .08       0    4414     .05       0  4995.8     .04       0
  5001.8     .05       0
Bank Sta=4995.8,5001.8
XS Rating Curve= 0 ,0
Exp/Cntr=0.3,0.1

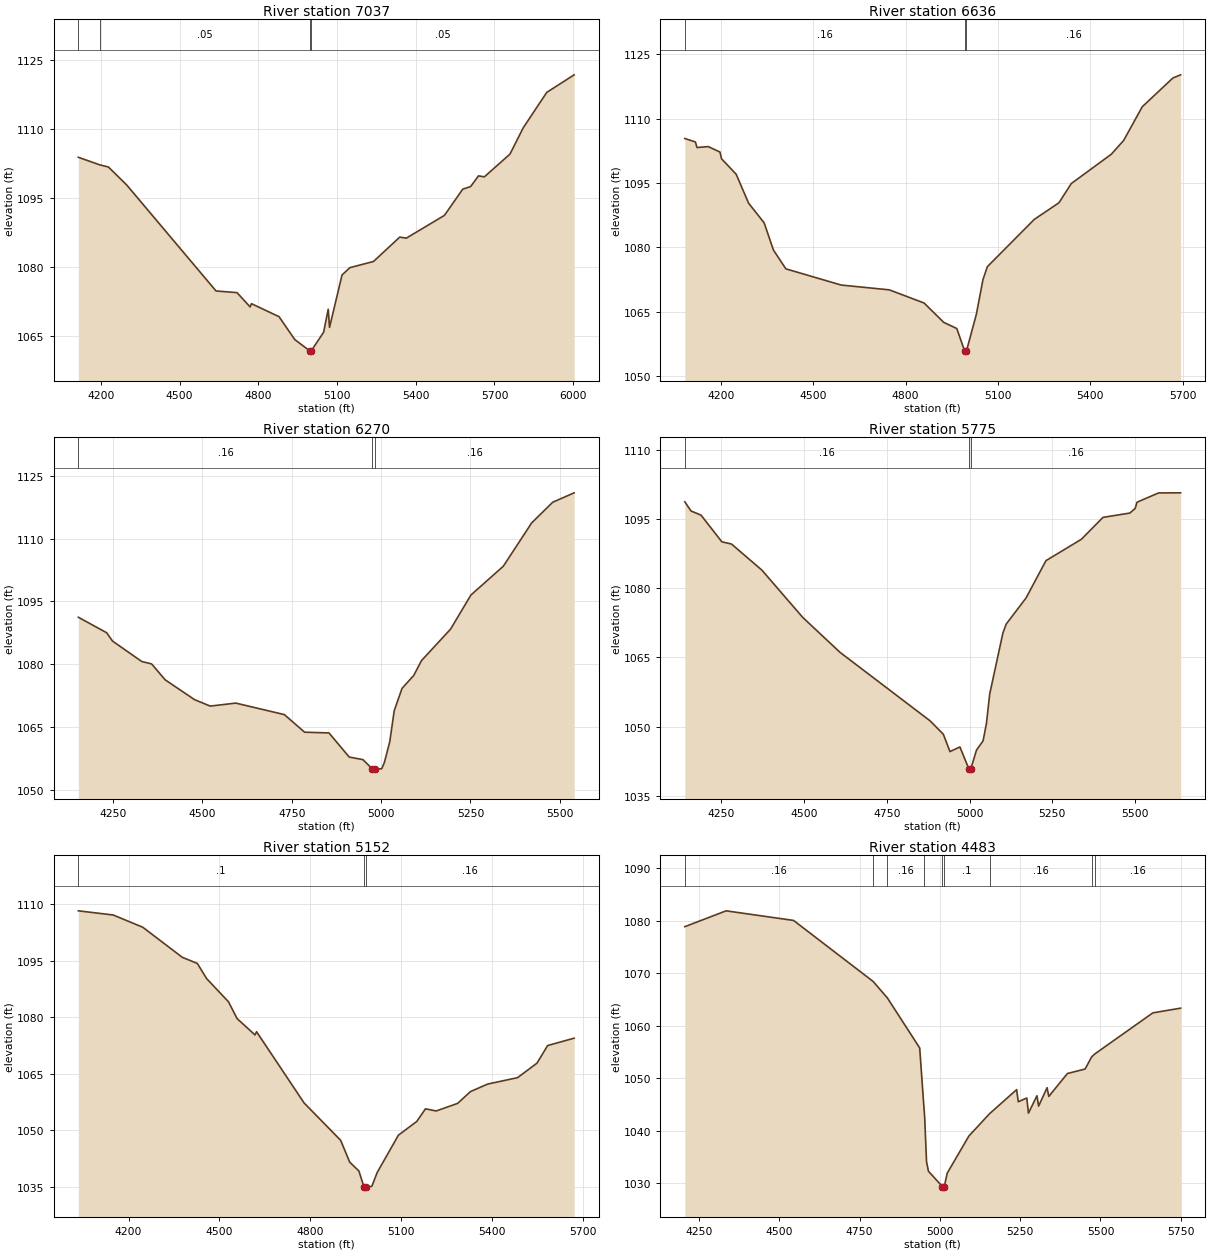
Type RM Length L Ch R = 1 ,7037    ,401,401,401
BEGIN DESCRIPTION:
BROCK HOLLOW 16.0
END DESCRIPTION:
XS GIS Cut Line= 2
      2920933.86     10069246.38      2922822.88     10069310.41
#Sta/Elev= 30
  4113.7 1103.89  4196.4 1102.22  4228.4 1101.78  4298.4 1097.85  4638.6 1074.83
  4718.7 1074.47  4768.6 1071.36  4773.6 1072.07  4878.7 1069.25  4938.8 1064.27
  4995.8 1061.82  4998.6 1061.32  5001.8 1061.82  5048.8 1065.87  5066.3 1070.87
  5071.3 1066.91  5118.9  1078.3  5148.9  1079.9  5238.9 1081.24    5339 1086.54
  5363.9 1086.31  5509.1 1091.25  5579.1 1096.96  5609.2 1097.53  5639.2 1099.85
  5661.6 1099.64  5759.2 1104.58  5809.3 1110.26  5899.3 1117.99  6003.8 1121.81
#Mann= 4 ,-1 , 0
  4113.7     .08       0  4196.4     .05       0  4995.8     .04       0
  5001.8     .05       0
Bank Sta=4995.8,5001.8
XS Rating Curve= 0 ,0
Exp/Cntr=0.3,0.1

Type RM Length L Ch R = 1 ,6636    ,366,366,366
BEGIN DESCRIPTION:
BROCK HOLLOW 15.0
END DESCRIPTION:
XS GIS Cut Line= 4
      2921352.94     10069823.59      2921902.39     10069753.28
      2922253.95      10069388.7      2922803.39     10069375.68
#Sta/Elev= 30
    4083 1105.36  4117.5 1104.55  4122.6 1103.25  4159.1 1103.47  4197.2  1102.2
  4202.3 1100.63  4249.9 1097.01  4290.2 1090.27  4340.6 1085.69  4370.9 1079.33
  4411.2 1074.95  4590.8 1071.17  4747.1 1070.05    4860 1066.98  4923.8 1062.46
  4966.3 1061.03  4991.6 1055.79  4994.3 1055.29  4997.6 1055.79  5029.8 1064.37
  5051.2 1072.44  5065.3 1075.44  5217.9 1086.49    5298 1090.37    5338 1094.85
    5468 1101.69    5508  1104.9  5568.5 1112.77  5668.1 1119.48    5693 1120.21
#Mann= 3 ,-1 , 0
    4083     .16       0  4991.6     .07       0  4997.6     .16       0
Bank Sta=4991.6,4997.6
XS Rating Curve= 0 ,0
Exp/Cntr=0.3,0.1

Type RM Length L Ch R = 1 ,6270    ,495,495,495
BEGIN DESCRIPTION:
BROCK HOLLOW 14.0
END DESCRIPTION:
XS GIS Cut Line= 2
      2921660.22     10070154.31      2922883.22     10069498.58
#Sta/Elev= 30
  4152.5 1091.23  4231.7 1087.54    4248 1085.56    4330 1080.67  4357.6 1080.09
  4395.8 1076.28  4477.8 1071.56  4521.7 1070.02  4593.1 1070.74  4729.2 1067.99
  4785.9 1063.79    4854 1063.62  4910.7 1057.86  4948.9 1057.25  4975.8    1055
  4978.6  1054.5  4981.8    1055  5001.5 1055.06    5009 1056.54  5024.2 1061.55
  5036.6 1068.93  5058.5 1074.26    5091 1077.31    5113 1080.89  5194.4  1088.4
  5251.1 1096.52  5341.9 1103.41  5421.3 1113.75  5480.1 1118.68  5540.2 1120.93
#Mann= 3 ,-1 , 0
  4152.5     .16       0  4975.8     .07       0  4981.8     .16       0
Bank Sta=4975.8,4981.8
XS Rating Curve= 0 ,0
Exp/Cntr=0.3,0.1

Type RM Length L Ch R = 1 ,5775    ,623,623,623
BEGIN DESCRIPTION:
BROCK HOLLOW 13.0
END DESCRIPTION:
XS GIS Cut Line= 4
      2921670.63     10070341.82      2922243.53     10070216.82
      2922779.99     10070216.82      2923108.11     10070034.53
#Sta/Elev= 30
  4139.6  1098.7  4158.5  1096.7  4188.6 1095.81  4251.5 1090.03  4280.7 1089.55
  4372.8 1083.88  4495.6 1073.68  4608.2 1066.11  4880.9 1051.24  4920.9 1048.33
  4940.9 1044.58  4970.9 1045.59  4997.9 1040.85  5000.7 1040.35  5003.9 1040.85
  5020.9 1044.89  5040.9 1046.92  5050.9  1050.6  5060.9 1057.04  5100.9  1070.3
  5110.9 1072.22  5170.9 1077.88  5230.9 1085.95    5338 1090.58  5403.2 1095.32
  5484.4 1096.26  5500.4 1097.25  5506.1 1098.61  5571.3 1100.62  5637.8 1100.64
#Mann= 3 ,-1 , 0
  4139.6     .16       0  4997.9     .07       0  5003.9     .16       0
Bank Sta=4997.9,5003.9
XS Rating Curve= 0 ,0
Exp/Cntr=0.3,0.1

Type RM Length L Ch R = 1 ,5152    ,669,669,669
BEGIN DESCRIPTION:
BROCK HOLLOW 12.0
END DESCRIPTION:
XS GIS Cut Line= 3
      2921457.11     10070716.82      2922587.28     10070836.61
      2922956.74     10070498.38
#Sta/Elev= 30
  4034.1 1108.18  4149.1 1107.08  4246.8 1103.84  4377.4 1095.87  4427.2 1094.24
  4457.8 1090.23  4529.9  1084.1  4558.4 1079.64  4617.6 1075.31  4622.6 1076.17
  4779.6  1057.3  4900.3 1047.41  4930.4 1041.61  4960.6 1039.28  4977.7 1034.97
  4980.5 1034.47  4983.7 1034.97  5003.4 1035.23    5021 1038.87  5091.1 1048.76
  5151.7 1052.39  5180.6 1055.74  5215.8 1055.17  5286.7 1057.18  5329.2 1060.31
    5386  1062.3  5484.6 1063.99  5548.8 1067.84  5583.9  1072.5  5671.5 1074.45
#Mann= 3 ,-1 , 0
  4034.1      .1       0  4977.7     .07       0  4983.7     .16       0
Bank Sta=4977.7,4983.7
XS Rating Curve= 0 ,0
Exp/Cntr=0.3,0.1

Type RM Length L Ch R = 1 ,4483    ,848,848,848
BEGIN DESCRIPTION:
BROCK HOLLOW 10.0
END DESCRIPTION:
XS GIS Cut Line= 4
       2921899.8     10071492.86      2922529.99     10071503.28
       2922722.7     10071185.57      2922894.01     10070671.63
#Sta/Elev= 30
  4205.9 1078.85  4334.6 1081.87  4544.6 1080.04  4792.3 1068.42  4836.4  1065.3
  4937.2 1055.76  4949.9 1044.86  4952.6 1042.69  4958.5 1034.11  4964.4 1032.29
  5007.8 1029.38  5010.6 1028.88  5013.8 1029.38  5022.8 1031.91  5090.3 1038.99
  5154.5 1043.23  5238.9 1047.82  5244.2 1045.52  5270.6 1046.23  5275.8 1043.35
  5302.2 1046.66  5307.4 1044.69  5333.8  1048.2  5339.1 1046.53    5397 1050.89
  5452.1 1051.75  5472.5 1054.05  5482.6 1054.63    5663 1062.44  5749.5 1063.34
#Mann= 9 ,-1 , 0
  4205.9     .16       0  4792.3      .1       0  4836.4     .16       0
  4949.9      .1       0  5007.8     .07       0  5013.8      .1       0
  5154.5     .16       0  5472.5      .1       0  5482.6     .16       0
Bank Sta=5007.8,5013.8
XS Rating Curve= 0 ,0
Exp/Cntr=0.3,0.1

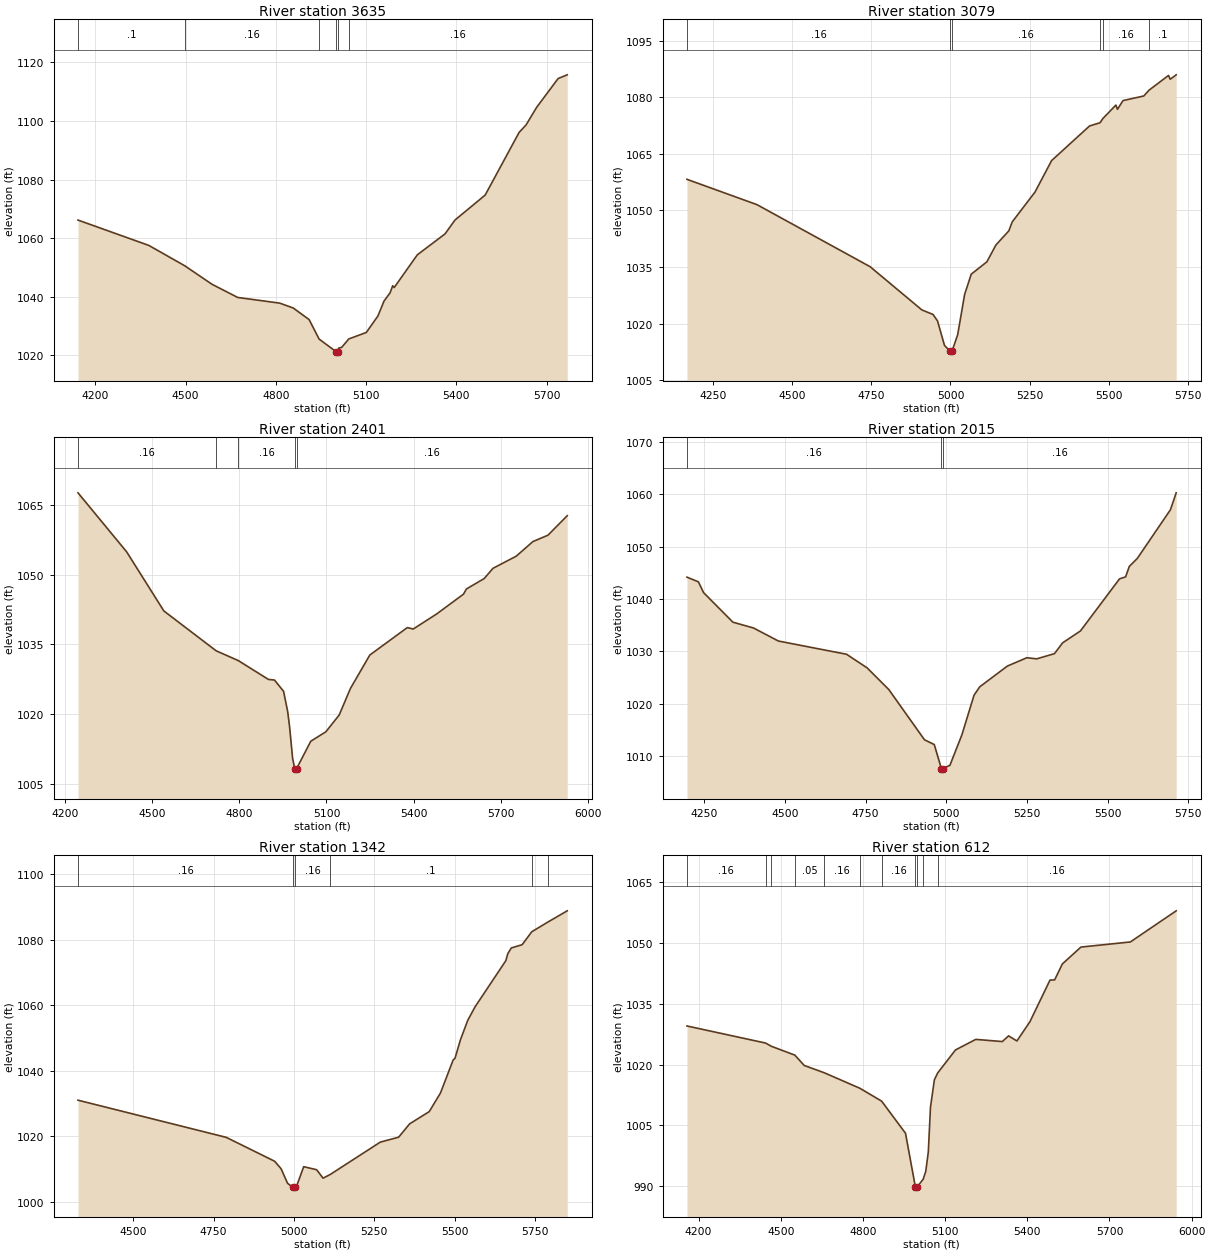
Type RM Length L Ch R = 1 ,3635    ,556,556,556
BEGIN DESCRIPTION:
BROCK HOLLOW 8.0
END DESCRIPTION:
XS GIS Cut Line= 4
      2923035.17     10072336.65      2923378.95     10071810.57
      2923441.45     10071222.03      2923681.04     10070893.89
#Sta/Elev= 30
  4142.3 1066.19  4377.8 1057.54  4497.1  1050.6  4587.8 1044.28  4673.3 1039.78
  4813.2 1037.84  4858.1 1036.17  4910.8 1032.22    4944 1025.57  5000.4 1021.28
  5003.2 1020.78  5006.4 1021.28  5008.9  1022.5    5019 1022.74  5042.5 1025.61
    5101 1027.84  5139.6 1033.48  5159.8 1038.55  5179.9 1041.35  5188.6 1043.78
  5193.6 1043.16  5270.4 1054.32  5362.6 1061.47  5395.7  1066.2  5496.1 1074.72
  5608.9  1096.1    5632 1098.66  5667.6 1104.72  5738.6 1114.49  5768.9 1115.76
#Mann= 6 ,-1 , 0
  4142.3      .1       0  4497.1     .16       0    4944      .1       0
  5000.4     .07       0  5006.4      .1       0  5042.5     .16       0
Bank Sta=5000.4,5006.4
XS Rating Curve= 0 ,0
Exp/Cntr=0.3,0.1

Type RM Length L Ch R = 1 ,3079    ,678,678,678
BEGIN DESCRIPTION:
BROCK HOLLOW 7.0
END DESCRIPTION:
XS GIS Cut Line= 4
      2923363.35     10072487.61      2923608.11     10072039.74
      2923977.91     10071722.03      2924108.12     10071190.78
#Sta/Elev= 30
  4167.9 1058.25  4388.8 1051.54  4746.2 1035.08  4909.7 1023.61  4944.9 1022.41
  4959.1  1020.7  4981.1  1014.2  4998.9 1012.65  5001.7 1012.15  5004.9 1012.65
  5022.8 1017.04  5044.7 1027.71  5065.6 1033.09    5115 1036.37  5143.5 1040.83
  5184.3 1044.58    5195 1046.96    5267 1054.88  5319.4 1063.22  5439.1  1072.4
  5472.5 1073.27  5481.3 1074.38  5522.3 1077.94  5527.4 1076.83    5545 1079.14
  5610.6 1080.36  5626.9 1081.89  5688.6 1085.81  5693.8 1084.79  5712.8 1085.97
#Mann= 6 ,-1 , 0
  4167.9     .16       0  4998.9     .07       0  5004.9     .16       0
  5472.5      .1       0  5481.3     .16       0  5626.9      .1       0
Bank Sta=4998.9,5004.9
XS Rating Curve= 0 ,0
Exp/Cntr=0.3,0.1

Type RM Length L Ch R = 1 ,2401    ,386,386,386
BEGIN DESCRIPTION:
BROCK HOLLOW 5.0
END DESCRIPTION:
XS GIS Cut Line= 4
      2923946.66     10072914.73      2924269.57      10072451.2
      2924420.61     10071935.57      2924311.24     10071362.63
#Sta/Elev= 30
    4244 1067.59  4411.6  1054.9  4539.8 1042.19  4719.9 1033.62    4796 1031.52
  4900.1 1027.46  4920.9 1027.33  4952.2 1024.91  4966.4 1020.56    4973 1017.28
  4983.4  1010.5  4990.8 1008.24  4993.6 1007.74  4996.8 1008.24  5045.9 1014.16
    5098  1016.2  5143.9 1019.81  5182.6 1025.52  5249.4 1032.71  5378.6 1038.61
    5399  1038.3  5480.4 1041.57  5572.1  1045.8  5582.2 1046.91  5643.3 1049.15
  5673.9 1051.36  5753.9 1053.97  5811.1  1057.1  5863.2 1058.48  5929.5 1062.67
#Mann= 5 ,-1 , 0
    4244     .16       0  4719.9      .1       0    4796     .16       0
  4990.8     .07       0  4996.8     .16       0
Bank Sta=4990.8,4996.8
XS Rating Curve= 0 ,0
Exp/Cntr=0.3,0.1

Type RM Length L Ch R = 1 ,2015    ,673,673,673
BEGIN DESCRIPTION:
BROCK HOLLOW 4.0
END DESCRIPTION:
XS GIS Cut Line= 2
      2924415.42       10073097.      2924945.97     10071676.98
#Sta/Elev= 30
  4196.5 1044.19    4232 1043.29    4248 1041.23  4338.9 1035.58  4402.8 1034.47
  4479.8 1031.98    4691 1029.45  4755.1 1026.83    4822  1022.7  4932.5  1013.1
  4962.8 1012.19  4984.8 1007.61  4987.5 1007.11  4990.8 1007.61  5011.3 1008.23
  5048.4 1014.05    5086 1021.62  5103.6 1023.22  5189.2 1027.19  5249.8 1028.79
  5280.1 1028.57  5335.3 1029.57  5360.3 1031.62  5415.6  1033.9  5536.8 1043.86
  5555.7 1044.25  5567.1 1046.24    5592 1047.78  5694.5 1057.07  5712.4 1060.31
#Mann= 3 ,-1 , 0
  4196.5     .16       0  4984.8     .07       0  4990.8     .16       0
Bank Sta=4984.8,4990.8
XS Rating Curve= 0 ,0
Exp/Cntr=0.3,0.1

Type RM Length L Ch R = 1 ,1342    ,730,730,730
BEGIN DESCRIPTION:
BROCK HOLLOW 3.0
END DESCRIPTION:
XS GIS Cut Line= 4
      2925201.85     10073138.73      2925311.24     10072774.11
      2925368.53     10072159.53      2925596.93     10071687.17
#Sta/Elev= 30
  4327.8 1030.94  4789.2 1019.59  4939.9 1012.29  4959.9    1010    4980 1005.56
  4997.1 1004.28  4999.9 1003.78  5003.1 1004.28  5010.2 1005.23  5030.2 1010.63
  5070.4 1009.71  5090.5 1007.13  5113.3 1008.28  5268.7 1018.14  5325.7 1019.64
    5360 1023.72    5421 1027.46  5455.9 1033.13  5495.5 1043.25  5501.1 1043.72
  5518.1 1049.39  5540.7 1055.29  5563.3 1059.41  5659.3 1073.54  5665.4 1075.66
  5676.3 1077.43    5710 1078.42  5740.1 1082.38  5790.9 1085.38  5850.4 1088.77
#Mann= 6 ,-1 , 0
  4327.8     .16       0  4997.1     .07       0  5003.1     .16       0
  5113.3      .1       0  5740.1     .16       0  5790.9      .1       0
Bank Sta=4997.1,5003.1
XS Rating Curve= 0 ,0
Exp/Cntr=0.3,0.1

Type RM Length L Ch R = 1 ,612     ,0,0,0
BEGIN DESCRIPTION:
BROCK HOLLOW 1.0
END DESCRIPTION:
XS GIS Cut Line= 3
      2925654.97     10073081.44      2926165.41     10071992.86
      2925910.67      10071467.8
#Sta/Elev= 30
  4157.7 1029.49  4445.1 1025.28  4465.4  1024.5  4551.6 1022.31  4585.9 1019.76
  4658.1 1017.99  4788.3 1014.17  4868.2 1010.99  4955.5 1003.07  4991.6  989.81
  4994.3  989.31  4997.6  989.81    5020  991.76  5029.4   993.7  5038.7  998.44
  5046.7 1009.53  5060.8 1016.21  5072.9 1017.92    5138 1023.59    5212 1026.19
  5308.8 1025.65  5331.7 1027.05  5362.2  1025.8  5409.7 1030.55  5482.9 1040.79
  5499.9 1040.84  5528.1 1044.77  5595.8 1048.92  5776.3 1050.18  5943.6 1057.85
#Mann= 11 ,-1 , 0
  4157.7     .16       0  4445.1     .05       0  4465.4     .16       0
  4551.6     .05       0  4658.1     .16       0  4788.3     .05       0
  4868.2     .16       0  4991.6     .07       0  4997.6     .16       0
    5020      .1       0  5072.9     .16       0
Bank Sta=4991.6,4997.6
XS Rating Curve= 0 ,0
Exp/Cntr=0.3,0.1

Chan Stop Cuts=-1
Use User Specified Reach Order=0
Composite Channel Slope=5