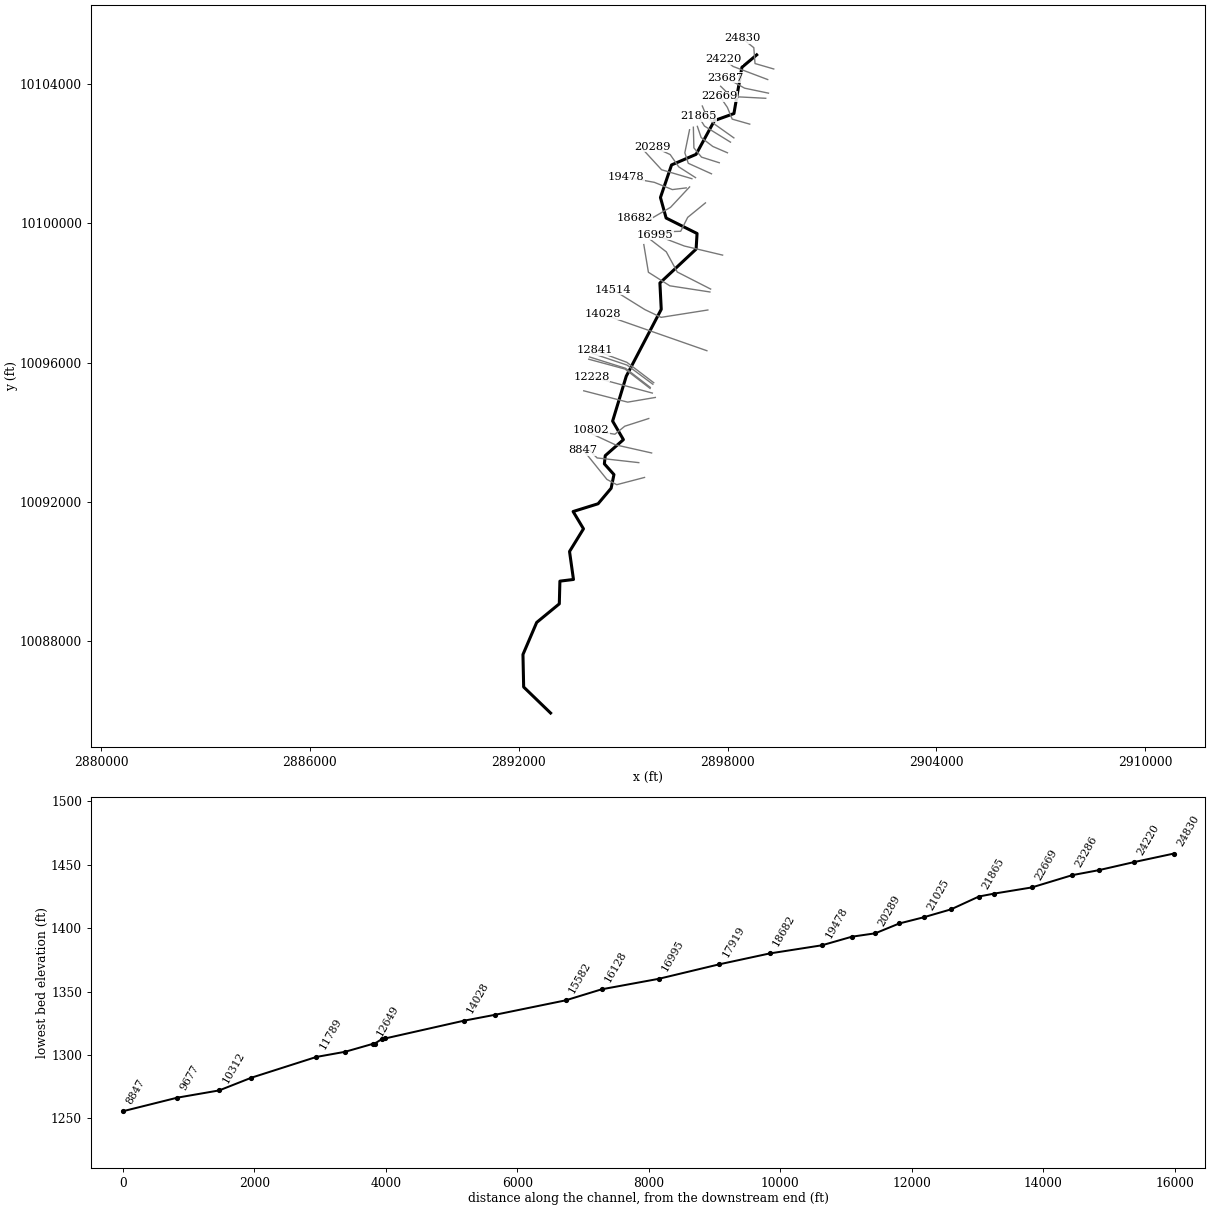
--- BUFFALO CREEK.prj (project) ---

Proj Title=BUFFALO CREEK Base Level Engineering
Current Plan=p01
Default Exp/Contr=0.3,0.1
English Units
Geom File=g01
Flow File=f01
Plan File=p01
BEGIN DESCRIPTION:
BUFFALO CREEK
END DESCRIPTION:

--- BUFFALO CREEK.p01 (plan) ---

Plan Title=Multiple Run
Short Identifier=Multiple
Geom File=g01
Flow File=f01
Subcritical Flow
K Sum by GR= 0
Std Step Tol= 0.01
Critical Tol= 0.01
Num of Std Step Trials= 20
Max Error Tol= 0.3
Flow Tol Ratio= 0.001
Split Flow NTrial= 30
Split Flow Tol= 0.02
Split Flow Ratio= 0.02
Log Output Level= 0
Friction Slope Method= 1
Unsteady Friction Slope Method= 2
Unsteady Bridges Friction Slope Method= 1
Parabolic Critical Depth
Global Vel Dist=  1 , 1 , 1
Global Log Level= 0
CheckData=True
Encroach Param= -1, 0, 0, 0
BEGIN DESCRIPTION:
Multiple Run
END DESCRIPTION:

--- BUFFALO CREEK.f01 (steady flow) ---

Flow Title=Multiple
Number of Profiles=7
Profile Names=10-year,25-year,50-year,1pct_min,100-year,1pct_plu,500-year
River Rch & RM= BUFFALO CREEK,Reach-1,24830
     749    1082    1371    1272    1720    2327    2720
River Rch & RM= BUFFALO CREEK,Reach-1,20289
    1818    2749    3588    3421    4627    6257    7732
River Rch & RM= BUFFALO CREEK,Reach-1,14028
    2184    3325    4361    4174    5644    7633    9505
River Rch & RM= BUFFALO CREEK,Reach-1,8181
    2540    3886    5113    4906    6635    8973   11232
Boundary for River Rch & Prof#=BUFFALO CREEK,Reach-1,1
Up Type=0
Dn Type=3
Dn Slope=0.005
Boundary for River Rch & Prof#=BUFFALO CREEK,Reach-1,2
Up Type=0
Dn Type=3
Dn Slope=0.005
Boundary for River Rch & Prof#=BUFFALO CREEK,Reach-1,3
Up Type=0
Dn Type=3
Dn Slope=0.005
Boundary for River Rch & Prof#=BUFFALO CREEK,Reach-1,4
Up Type=0
Dn Type=3
Dn Slope=0.005
Boundary for River Rch & Prof#=BUFFALO CREEK,Reach-1,5
Up Type=0
Dn Type=3
Dn Slope=0.005
Boundary for River Rch & Prof#=BUFFALO CREEK,Reach-1,6
Up Type=0
Dn Type=3
Dn Slope=0.005
Boundary for River Rch & Prof#=BUFFALO CREEK,Reach-1,7
Up Type=0
Dn Type=3
Dn Slope=0.005

--- BUFFALO CREEK.g01 (geometry) ---

Geom Title=Existing Conditions

River Reach=BUFFALO CREEK,Reach-1
Reach XY= 30
      2898838.47     10104843.73      2898413.21     10104486.56
      2898184.10     10103157.50      2897623.67     10102955.59
      2897096.90     10101986.24      2896391.98     10101682.30
      2896072.79     10100746.50      2896235.87     10100157.12
      2897124.81     10099712.27      2897097.50     10099264.06
      2896057.24     10098290.51      2896095.76     10097534.97
      2895090.39     10095613.05      2894698.47     10094323.73
      2895008.55     10093790.90      2894486.11     10093331.14
      2894461.95     10093095.07      2894736.67     10092787.99
      2894656.05     10092394.84      2894280.86     10091949.33
      2893563.47     10091726.32      2893861.09     10091229.50
      2893460.49     10090577.87      2893573.60     10089774.74
      2893183.74     10089726.45      2893166.61     10089074.50
      2892516.49     10088539.88      2892122.27     10087618.86
      2892142.30     10086685.25      2892916.04     10085938.05

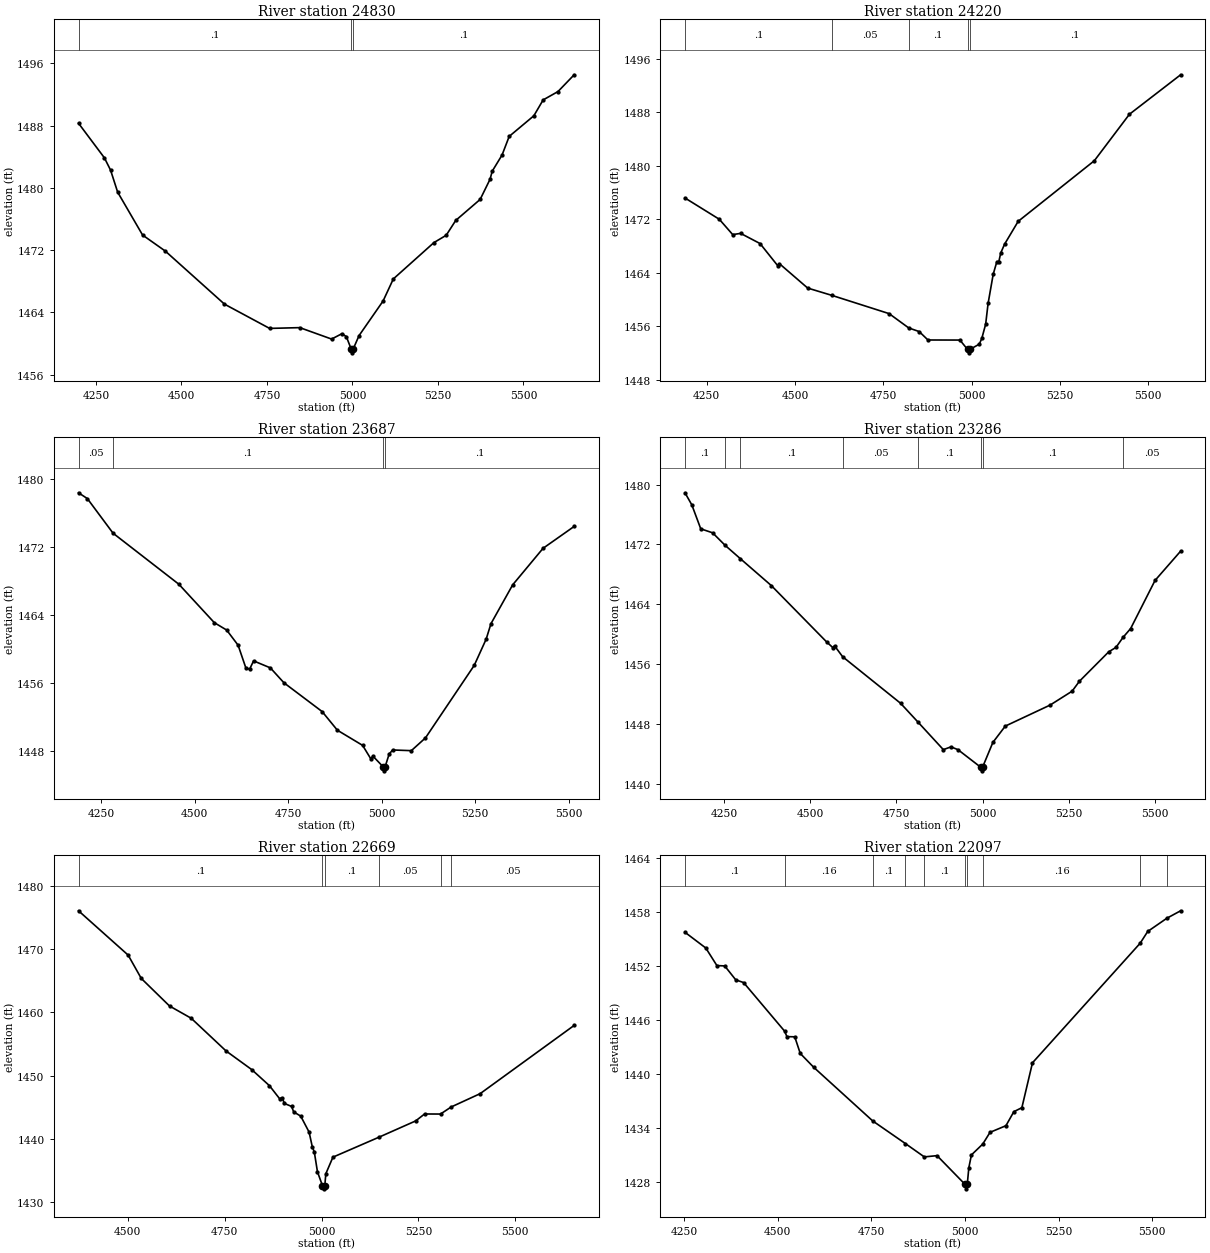
Type RM Length L Ch R = 1,24830,610,610,610
BEGIN DESCRIPTION:
BUFFALO CREEK 53.0
END DESCRIPTION:
XS GIS Cut Line= 4
      2899328.45     10104438.32      2898790.22     10104594.58
      2898755.50     10105050.31      2898417.40     10105319.05
#Sta/Elev= 30
  4199.0 1488.31  4274.6 1483.87  4292.7 1482.29  4313.5 1479.45  4386.4 1473.94
  4452.8 1471.88  4625.8 1465.06  4757.8 1461.94  4846.1 1462.04  4939.1 1460.57
  4969.2 1461.26  4982.1 1460.89  4996.3 1459.30  4999.0 1458.80  5002.3 1459.30
  5019.4 1461.02  5089.6 1465.46  5119.6 1468.30  5238.3 1472.97  5274.2 1473.91
  5302.1 1475.82  5373.5 1478.52  5402.4 1481.11  5408.8 1482.15  5437.6 1484.23
  5458.4 1486.62  5530.5 1489.27  5557.7 1491.31  5601.0 1492.38  5648.4 1494.54
#Mann=3,-1,0
  4199.0     0.1       0  4996.3    0.07       0  5002.3     0.1       0
Bank Sta=4996.3,5002.3
Exp/Cntr=0.3,0.1

Type RM Length L Ch R = 1,24220,533,533,533
BEGIN DESCRIPTION:
BUFFALO CREEK 52.0
END DESCRIPTION:
XS GIS Cut Line= 3
      2899154.83     10104134.50      2898156.54     10104512.11
      2897896.16     10104724.76
#Sta/Elev= 30
  4188.2 1475.16  4285.4 1471.98  4323.3 1469.69  4345.8 1469.87  4400.8 1468.35
  4450.4 1465.07  4455.7 1465.34  4535.6 1461.70  4604.0 1460.61  4766.2 1457.88
  4821.8 1455.74  4851.4 1455.20  4876.2 1453.94  4966.7 1453.93  4988.5 1452.52
  4991.3 1452.02  4994.5 1452.52  5021.7 1453.32  5028.9 1454.21  5039.6 1456.30
  5046.5 1459.40  5061.0 1463.77  5071.4 1465.66  5076.7 1465.61  5082.4 1466.95
  5093.1 1468.25  5131.7 1471.67  5347.4 1480.73  5446.7 1487.67  5591.7 1493.57
#Mann=5,-1,0
  4188.2     0.1       0  4604.0    0.05       0  4821.8     0.1       0
  4988.5    0.07       0  4994.5     0.1       0
Bank Sta=4988.5,4994.5
Exp/Cntr=0.3,0.1

Type RM Length L Ch R = 1,23687,401,401,401
BEGIN DESCRIPTION:
BUFFALO CREEK 51.0
END DESCRIPTION:
XS GIS Cut Line= 3
      2899176.47     10103743.89      2898490.74     10103887.11
      2897943.89     10104190.92
#Sta/Elev= 30
  4188.8 1478.34  4212.4 1477.66  4281.3 1473.59  4457.3 1467.60  4552.1 1463.09
  4585.2 1462.22  4615.8 1460.44  4636.3 1457.80  4646.5 1457.62  4657.2 1458.60
  4702.1 1457.78  4738.4 1456.03  4840.6 1452.65  4881.4 1450.46  4948.9 1448.68
  4970.7 1447.11  4976.4 1447.42  5003.3 1446.19  5006.1 1445.69  5009.3 1446.19
  5019.8 1447.65  5029.2 1448.14  5079.3 1448.06  5117.1 1449.56  5247.5 1458.07
  5279.5 1461.16  5292.3 1462.97  5350.4 1467.53  5431.7 1471.82  5514.9 1474.39
#Mann=4,-1,0
  4188.8    0.05       0  4281.3     0.1       0  5003.3    0.07       0
  5009.3     0.1       0
Bank Sta=5003.3,5009.3
Exp/Cntr=0.3,0.1

Type RM Length L Ch R = 1,23286,617,617,617
BEGIN DESCRIPTION:
BUFFALO CREEK 50.0
END DESCRIPTION:
XS GIS Cut Line= 4
      2899098.37     10103596.32      2898347.51     10103635.38
      2898147.86     10103605.00      2897802.05     10103942.16
#Sta/Elev= 30
  4137.4 1478.90  4157.3 1477.28  4183.1 1474.09  4217.4 1473.56  4253.9 1471.88
  4297.8 1470.11  4387.6 1466.52  4547.9 1459.00  4565.9 1458.24  4570.9 1458.48
  4594.4 1457.02  4762.3 1450.81  4813.8 1448.25  4886.3 1444.62  4908.5 1444.99
  4928.6 1444.62  4994.2 1442.29  4997.0 1441.79  5000.2 1442.29  5029.9 1445.58
  5065.9 1447.76  5196.0 1450.57  5259.6 1452.42  5280.9 1453.75  5365.7 1457.67
  5386.9 1458.27  5407.2 1459.60  5429.3 1460.78  5500.0 1467.20  5574.2 1471.11
#Mann=8,-1,0
  4137.4     0.1       0  4253.9    0.05       0  4297.8     0.1       0
  4594.4    0.05       0  4813.8     0.1       0  4994.2    0.07       0
  5000.2     0.1       0  5407.2    0.05       0
Bank Sta=4994.2,5000.2
Exp/Cntr=0.3,0.1

Type RM Length L Ch R = 1,22669,572,572,572
BEGIN DESCRIPTION:
BUFFALO CREEK 49.0
END DESCRIPTION:
XS GIS Cut Line= 4
      2898638.29     10102854.13      2898134.84     10102997.36
      2897995.95     10103335.90      2897774.61     10103657.06
#Sta/Elev= 30
  4372.7 1476.06  4500.8 1469.05  4534.7 1465.36  4607.6 1461.00  4663.6 1459.06
  4753.5 1453.89  4819.6 1450.95  4865.5 1448.40  4891.6 1446.35  4898.7 1446.43
  4904.1 1445.59  4922.7 1445.11  4928.1 1444.25  4946.3 1443.58  4967.9 1441.05
  4976.0 1438.77  4981.4 1437.89  4989.5 1434.77  5002.4 1432.58  5005.2 1432.08
  5008.4 1432.58  5011.1 1434.47  5029.4 1437.09  5148.7 1440.26  5242.9 1442.82
  5266.0 1443.92  5307.1 1443.91  5334.7 1445.03  5409.3 1447.13  5652.1 1457.93
#Mann=6,-1,0
  4372.7     0.1       0  5002.4    0.07       0  5008.4     0.1       0
  5148.7    0.05       0  5307.1     0.1       0  5334.7    0.05       0
Bank Sta=5002.4,5008.4
Exp/Cntr=0.3,0.1

Type RM Length L Ch R = 1,22097,232,232,232
BEGIN DESCRIPTION:
BUFFALO CREEK 47.0
END DESCRIPTION:
XS GIS Cut Line= 4
      2898182.54     10102459.19      2897644.38     10102841.11
      2897401.33     10103071.14      2897275.47     10103374.95
#Sta/Elev= 30
  4252.4 1455.73  4308.0 1453.98  4337.6 1452.03  4358.5 1451.99  4388.0 1450.44
  4408.9 1450.14  4518.4 1444.74  4524.6 1444.13  4545.5 1444.11  4560.2 1442.26
  4595.9 1440.73  4753.6 1434.76  4841.0 1432.24  4891.4 1430.76  4925.4 1430.90
  5000.1 1427.71  5002.8 1427.21  5006.1 1427.71  5010.3 1429.56  5017.2 1430.98
  5047.5 1432.19  5066.9 1433.49  5109.4 1434.23  5130.5 1435.79  5151.9 1436.23
  5180.2 1441.22  5467.7 1454.51  5487.9 1455.82  5539.0 1457.29  5575.8 1458.12
#Mann=10,-1,0
  4252.4     0.1       0  4518.4    0.16       0  4753.6     0.1       0
  4841.0    0.16       0  4891.4     0.1       0  5000.1    0.07       0
  5006.1     0.1       0  5047.5    0.16       0  5467.7     0.1       0
  5539.0    0.05       0
Bank Sta=5000.1,5006.1
Exp/Cntr=0.3,0.1

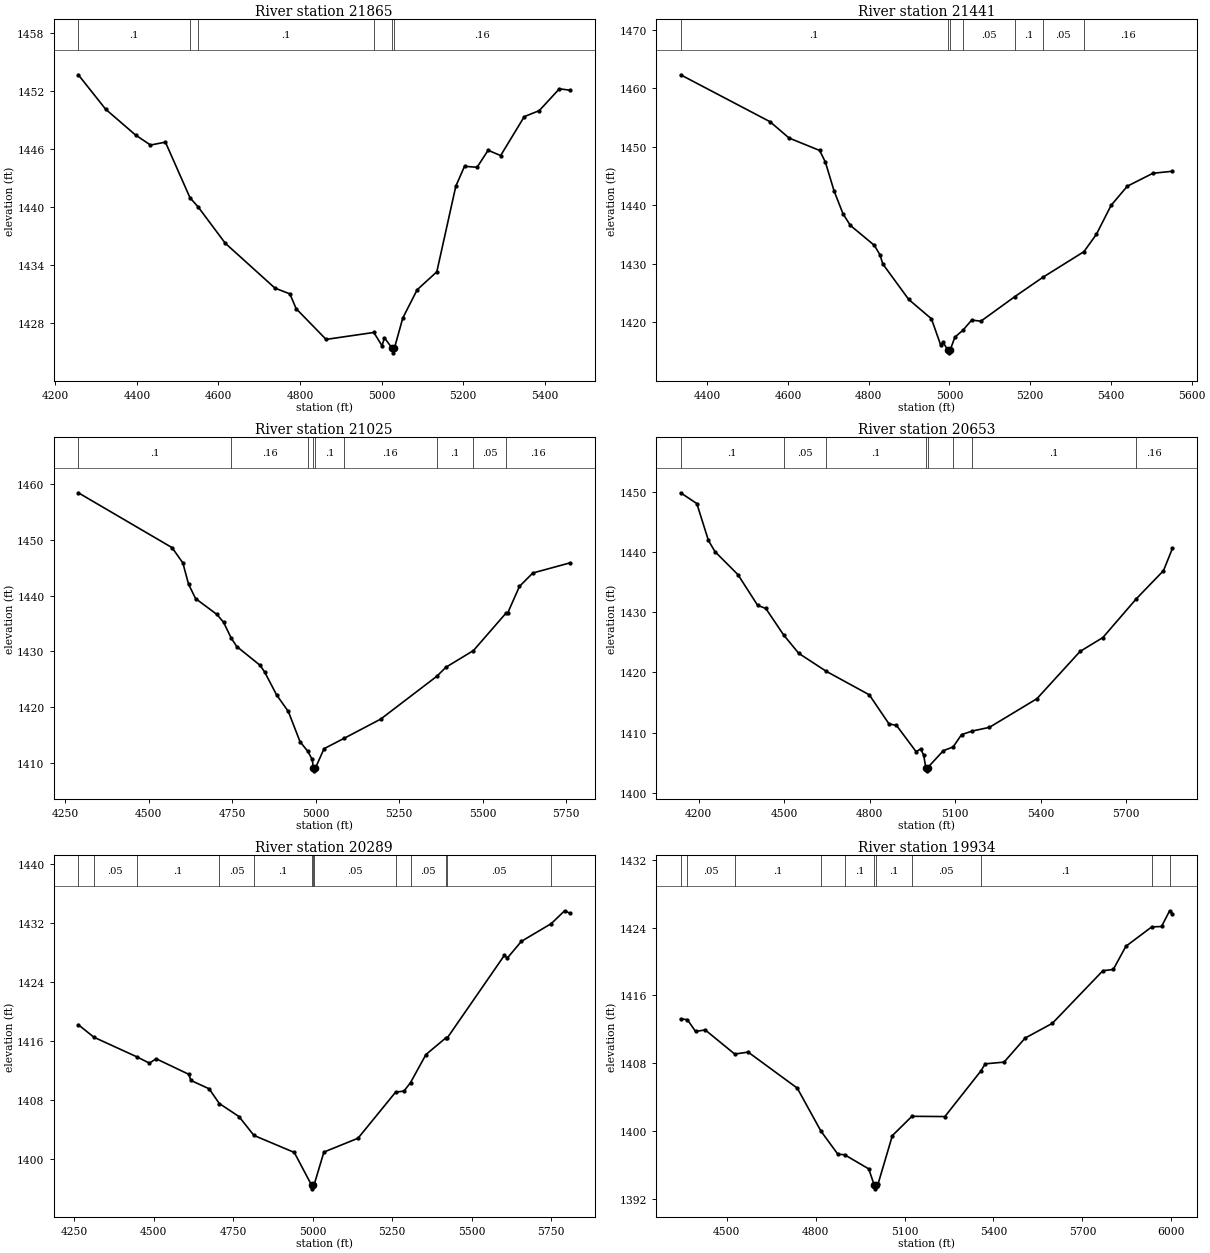
Type RM Length L Ch R = 1,21865,424,424,424
BEGIN DESCRIPTION:
Mapping XS f016a375
END DESCRIPTION:
XS GIS Cut Line= 3
      2898085.11     10102336.49      2897337.57     10102798.33
      2897165.37     10103076.19
#Sta/Elev= 30
  4256.5 1453.69  4323.4 1450.13  4396.7 1447.46  4433.4 1446.42  4470.0 1446.72
  4530.2 1440.97  4550.7 1439.99  4616.7 1436.26  4738.4 1431.62  4775.1 1431.02
  4790.4 1429.49  4863.8 1426.31  4980.9 1427.03  5000.9 1425.65  5006.8 1426.48
  5025.4 1425.42  5028.1 1424.92  5031.4 1425.42  5051.9 1428.53  5087.1 1431.45
  5135.2 1433.30  5181.8 1442.16  5203.1 1444.22  5233.9 1444.12  5261.0 1445.88
  5291.7 1445.33  5349.6 1449.36  5386.3 1449.98  5435.7 1452.24  5462.1 1452.09
#Mann=6,-1,0
  4256.5     0.1       0  4530.2    0.16       0  4550.7     0.1       0
  4980.9    0.16       0  5025.4    0.07       0  5031.4    0.16       0
Bank Sta=5025.4,5031.4
Exp/Cntr=0.3,0.1

Type RM Length L Ch R = 1,21441,416,416,416
BEGIN DESCRIPTION:
BUFFALO CREEK 46.0
END DESCRIPTION:
XS GIS Cut Line= 4
      2897997.70     10102031.20      2897575.81     10102213.50
      2897242.47     10102468.71      2897133.79     10102789.60
#Sta/Elev= 30
  4334.2 1462.29  4555.8 1454.27  4602.8 1451.49  4678.7 1449.36  4692.9 1447.35
  4714.6 1442.40  4736.6 1438.53  4754.7 1436.56  4814.1 1433.16  4828.2 1431.51
  4834.9 1429.99  4899.3 1423.91  4955.5 1420.61  4978.2 1416.17  4984.5 1416.57
  4996.0 1415.30  4998.8 1414.80  5002.0 1415.30  5013.5 1417.48  5033.5 1418.66
  5055.2 1420.40  5077.9 1420.20  5162.0 1424.40  5230.8 1427.67  5333.2 1432.08
  5363.9 1435.03  5400.6 1440.00  5440.6 1443.26  5504.0 1445.47  5552.4 1445.81
#Mann=7,-1,0
  4334.2     0.1       0  4996.0    0.07       0  5002.0     0.1       0
  5033.5    0.05       0  5162.0     0.1       0  5230.8    0.05       0
  5333.2    0.16       0
Bank Sta=4996,5002
Exp/Cntr=0.3,0.1

Type RM Length L Ch R = 1,21025,372,372,372
BEGIN DESCRIPTION:
BUFFALO CREEK 45.0
END DESCRIPTION:
XS GIS Cut Line= 4
      2897763.33     10101744.75      2897252.89     10101906.21
      2897034.14     10102171.84      2897018.52     10102765.56
#Sta/Elev= 30
  4289.0 1458.48  4569.8 1448.63  4602.1 1445.89  4619.2 1442.07  4640.2 1439.48
  4704.2 1436.63  4724.1 1435.22  4747.1 1432.37  4763.6 1430.87  4833.4 1427.50
  4847.1 1426.30  4882.9 1422.18  4918.1 1419.20  4953.2 1413.77  4976.2 1412.06
  4989.6 1410.60  4993.3 1409.04  4996.0 1408.54  4999.3 1409.04  5025.0 1412.51
  5085.5 1414.39  5194.8 1417.83  5362.4 1425.50  5390.4 1427.15  5472.8 1430.15
  5571.0 1436.92  5574.9 1436.84  5610.5 1441.67  5650.5 1444.07  5762.4 1445.90
#Mann=9,-1,0
  4289.0     0.1       0  4747.1    0.16       0  4976.2     0.1       0
  4993.3    0.07       0  4999.3     0.1       0  5085.5    0.16       0
  5362.4     0.1       0  5472.8    0.05       0  5571.0    0.16       0
Bank Sta=4993.3,4999.3
Exp/Cntr=0.3,0.1

Type RM Length L Ch R = 1,20653,364,364,364
BEGIN DESCRIPTION:
BUFFALO CREEK 44.0
END DESCRIPTION:
XS GIS Cut Line= 4
      2897539.33     10101427.05      2896872.68     10101729.13
      2896773.72     10102031.21      2896909.15     10102692.72
#Sta/Elev= 30
  4137.2 1449.82  4194.1 1448.03  4234.8 1441.90  4257.9 1440.04  4338.2 1436.23
  4407.5 1431.12  4436.0 1430.61  4498.7 1426.20  4551.5 1423.16  4647.7 1420.18
  4798.9 1416.27  4868.2 1411.43  4894.2 1411.20  4963.2 1406.82  4979.2 1407.28
  4989.7 1406.25  4997.3 1404.14  5000.0 1403.64  5003.3 1404.14  5058.7 1406.99
  5093.1 1407.61  5122.4 1409.65  5160.0 1410.25  5220.2 1410.86  5386.9 1415.62
  5538.2 1423.47  5618.3 1425.78  5735.2 1432.20  5830.7 1436.88  5862.2 1440.58
#Mann=8,-1,0
  4137.2     0.1       0  4498.7    0.05       0  4647.7     0.1       0
  4997.3    0.07       0  5003.3     0.1       0  5093.1    0.05       0
  5160.0     0.1       0  5735.2    0.16       0
Bank Sta=4997.3,5003.3
Exp/Cntr=0.3,0.1

Type RM Length L Ch R = 1,20289,355,355,355
BEGIN DESCRIPTION:
BUFFALO CREEK 43.0
END DESCRIPTION:
XS GIS Cut Line= 4
      2897081.04     10101317.65      2896598.38     10101626.70
      2896351.85     10101980.86      2895858.79     10102206.56
#Sta/Elev= 30
  4262.7 1418.21  4311.8 1416.51  4446.5 1413.85  4486.3 1412.99  4507.5 1413.58
  4610.1 1411.47  4616.6 1410.64  4674.1 1409.50  4706.1 1407.50  4767.9 1405.73
  4815.1 1403.16  4941.9 1400.85  4996.3 1396.40  4999.1 1395.90  5002.3 1396.40
  5004.8 1396.53  5035.1 1400.90  5142.4 1402.78  5260.7 1409.05  5286.9 1409.19
  5307.5 1410.34  5355.9 1414.15  5418.2 1416.41  5423.2 1416.42  5602.5 1427.63
  5612.0 1427.27  5656.0 1429.54  5750.3 1431.96  5792.1 1433.70  5809.6 1433.35
#Mann=13,-1,0
  4262.7     0.1       0  4311.8    0.05       0  4446.5     0.1       0
  4706.1    0.05       0  4815.1     0.1       0  4996.3    0.07       0
  5002.3     0.1       0  5004.8    0.05       0  5260.7     0.1       0
  5307.5    0.05       0  5418.2     0.1       0  5423.2    0.05       0
  5750.3     0.1       0
Bank Sta=4996.3,5002.3
Exp/Cntr=0.3,0.1

Type RM Length L Ch R = 1,19934,456,456,456
BEGIN DESCRIPTION:
BUFFALO CREEK 42.0
END DESCRIPTION:
XS GIS Cut Line= 3
      2896976.89     10101286.41      2896105.32     10101543.36
      2895598.36     10102095.46
#Sta/Elev= 30
  4345.1 1413.26  4368.1 1413.14  4395.6 1411.76  4428.1 1411.94  4527.6 1409.10
  4572.8 1409.33  4738.4 1405.09  4818.2 1400.03  4875.2 1397.31  4898.2 1397.24
  4979.4 1395.58  4997.3 1393.73  5000.0 1393.23  5003.3 1393.73  5010.7 1393.79
  5059.1 1399.50  5125.0 1401.77  5236.1 1401.74  5357.0 1407.09  5372.2 1407.95
  5435.7 1408.15  5506.6 1410.98  5598.5 1412.72  5768.7 1418.91  5803.8 1419.06
  5846.4 1421.79  5933.5 1424.07  5966.6 1424.12  5993.8 1425.97  6003.3 1425.63
#Mann=11,-1,0
  4345.1     0.1       0  4368.1    0.05       0  4527.6     0.1       0
  4818.2    0.05       0  4898.2     0.1       0  4997.3    0.07       0
  5003.3     0.1       0  5125.0    0.05       0  5357.0     0.1       0
  5933.5    0.05       0  5993.8     0.1       0
Bank Sta=4997.3,5003.3
Exp/Cntr=0.3,0.1

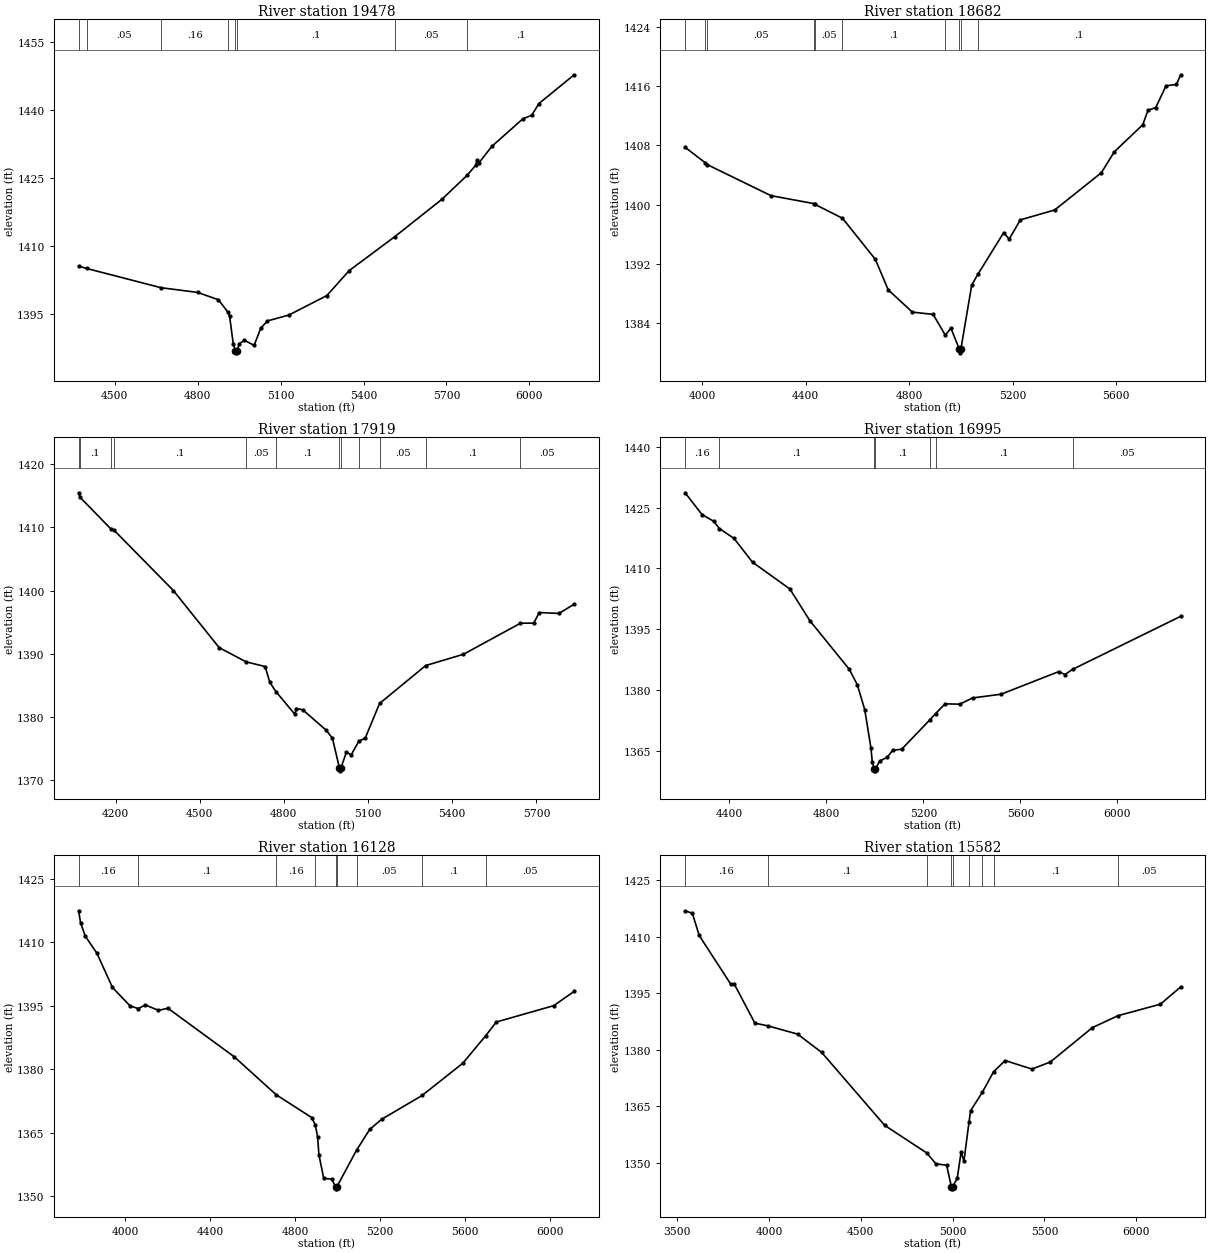
Type RM Length L Ch R = 1,19478,796,796,796
BEGIN DESCRIPTION:
BUFFALO CREEK 41.0
END DESCRIPTION:
XS GIS Cut Line= 4
      2896813.69     10101022.53      2896414.35     10100973.92
      2895896.99     10101182.25      2895077.50     10101331.57
#Sta/Elev= 30
  4369.0 1405.56  4398.4 1405.04  4667.3 1400.80  4799.2 1399.77  4874.7 1398.15
  4909.0 1395.44  4915.2 1394.53  4928.6 1388.39  4936.3 1386.95  4939.1 1386.45
  4942.3 1386.95  4950.2 1388.44  4968.9 1389.22  5004.0 1388.09  5028.0 1391.88
  5052.2 1393.48  5130.1 1394.79  5267.1 1399.07  5347.9 1404.57  5512.9 1412.05
  5683.3 1420.28  5774.6 1425.57  5805.3 1427.76  5810.9 1429.00  5816.0 1428.21
  5864.2 1431.96  5975.9 1438.00  6008.6 1438.82  6034.3 1441.38  6162.0 1447.73
#Mann=8,-1,0
  4369.0     0.1       0  4398.4    0.05       0  4667.3    0.16       0
  4909.0     0.1       0  4936.3    0.07       0  4942.3     0.1       0
  5512.9    0.05       0  5774.6     0.1       0
Bank Sta=4936.3,4942.3
Exp/Cntr=0.3,0.1

Type RM Length L Ch R = 1,18682,763,763,763
BEGIN DESCRIPTION:
BUFFALO CREEK 40.0
END DESCRIPTION:
XS GIS Cut Line= 4
      2896910.85     10101050.27      2896362.27     10100463.50
      2895848.38     10100164.89      2895332.28     10100151.04
#Sta/Elev= 30
  3934.4 1407.75  4012.7 1405.65  4019.4 1405.42  4266.2 1401.22  4433.1 1400.14
  4436.2 1400.04  4542.3 1398.17  4669.2 1392.62  4719.0 1388.50  4812.1 1385.50
  4892.4 1385.19  4939.2 1382.39  4961.1 1383.33  4993.5 1380.50  4996.3 1380.00
  4999.5 1380.50  5041.4 1389.14  5065.3 1390.61  5164.7 1396.22  5186.2 1395.36
  5229.2 1397.95  5361.9 1399.29  5542.0 1404.31  5592.0 1407.14  5702.1 1410.80
  5722.1 1412.74  5752.1 1413.12  5792.1 1416.06  5832.1 1416.23  5848.3 1417.54
#Mann=10,-1,0
  3934.4    0.05       0  4012.7     0.1       0  4019.4    0.05       0
  4433.1     0.1       0  4436.2    0.05       0  4542.3     0.1       0
  4939.2    0.16       0  4993.5    0.07       0  4999.5    0.16       0
  5065.3     0.1       0
Bank Sta=4993.5,4999.5
Exp/Cntr=0.3,0.1

Type RM Length L Ch R = 1,17919,924,924,924
BEGIN DESCRIPTION:
BUFFALO CREEK 39.0
END DESCRIPTION:
XS GIS Cut Line= 4
      2897365.76     10100591.99      2896855.32     10100175.31
      2896653.93     10099776.00      2895994.20     10099755.17
#Sta/Elev= 30
  4068.5 1415.48  4072.7 1414.81  4182.1 1409.82  4195.8 1409.51  4406.4 1400.00
  4569.4 1390.97  4665.3 1388.72  4733.2 1387.98  4749.9 1385.47  4772.3 1383.98
  4839.1 1380.43  4844.7 1381.33  4867.0 1381.14  4950.6 1377.91  4972.9 1376.65
  4997.8 1371.97  5000.5 1371.47  5003.8 1371.97  5023.1 1374.45  5039.8 1373.98
  5067.0 1376.15  5090.0 1376.66  5141.2 1382.13  5305.3 1388.13  5440.2 1389.92
  5643.1 1394.83  5690.4 1394.85  5710.4 1396.53  5780.4 1396.38  5834.7 1397.85
#Mann=12,-1,0
  4068.5    0.05       0  4072.7     0.1       0  4182.1    0.05       0
  4195.8     0.1       0  4665.3    0.05       0  4772.3     0.1       0
  4997.8    0.07       0  5003.8     0.1       0  5067.0    0.16       0
  5141.2    0.05       0  5305.3     0.1       0  5643.1    0.05       0
Bank Sta=4997.8,5003.8
Exp/Cntr=0.3,0.1

Type RM Length L Ch R = 1,16995,867,867,867
BEGIN DESCRIPTION:
BUFFALO CREEK 37.0
END DESCRIPTION:
XS GIS Cut Line= 3
      2897858.83     10099091.97      2896761.57     10099352.39
      2895907.44     10099678.77
#Sta/Elev= 30
  4218.1 1428.65  4288.0 1423.26  4335.3 1421.64  4359.5 1419.82  4419.7 1417.37
  4496.0 1411.51  4650.1 1404.88  4732.4 1397.05  4894.3 1385.09  4927.6 1381.28
  4958.5 1375.08  4983.9 1365.66  4989.3 1362.28  4996.6 1360.49  4999.3 1359.99
  5002.6 1360.49  5020.1 1362.43  5051.0 1363.33  5073.4 1365.06  5110.5 1365.32
  5225.7 1372.52  5250.5 1374.14  5289.6 1376.53  5350.2 1376.45  5402.7 1377.99
  5520.4 1378.91  5758.6 1384.51  5783.3 1383.77  5815.6 1385.07  6260.2 1398.14
#Mann=7,-1,0
  4218.1    0.16       0  4359.5     0.1       0  4996.6    0.07       0
  5002.6     0.1       0  5225.7    0.05       0  5250.5     0.1       0
  5815.6    0.05       0
Bank Sta=4996.6,5002.6
Exp/Cntr=0.3,0.1

Type RM Length L Ch R = 1,16128,546,546,546
BEGIN DESCRIPTION:
BUFFALO CREEK 36.0
END DESCRIPTION:
XS GIS Cut Line= 4
      2897515.03     10098116.29      2896556.71     10098605.86
      2896240.74     10099185.72      2895769.53     10099549.53
#Sta/Elev= 30
  3782.2 1417.44  3791.4 1414.58  3813.6 1411.43  3868.2 1407.41  3941.3 1399.32
  4024.6 1394.95  4062.4 1394.34  4096.8 1395.17  4157.9 1393.91  4202.3 1394.41
  4513.4 1382.98  4711.7 1373.97  4878.7 1368.58  4896.1 1366.84  4907.0 1363.89
  4912.8 1359.80  4935.6 1354.20  4972.5 1354.03  4991.4 1352.23  4994.1 1351.73
  4997.4 1352.23  5089.8 1360.84  5152.0 1365.79  5208.9 1368.19  5398.3 1373.79
  5590.1 1381.42  5697.9 1387.93  5747.7 1391.15  6017.6 1395.02  6114.0 1398.39
#Mann=9,-1,0
  3782.2    0.16       0  4062.4     0.1       0  4711.7    0.16       0
  4896.1     0.1       0  4991.4    0.07       0  4997.4     0.1       0
  5089.8    0.05       0  5398.3     0.1       0  5697.9    0.05       0
Bank Sta=4991.4,4997.4
Exp/Cntr=0.3,0.1

Type RM Length L Ch R = 1,15582,1068,1068,1068
BEGIN DESCRIPTION:
BUFFALO CREEK 34.0
END DESCRIPTION:
XS GIS Cut Line= 4
      2897494.17     10098032.95      2896341.43     10098210.03
      2895726.85     10098598.92      2895594.90     10099394.10
#Sta/Elev= 30
  3542.5 1416.83  3582.1 1416.17  3619.1 1410.29  3791.1 1397.36  3811.3 1397.31
  3922.6 1387.00  3991.5 1386.32  4155.3 1384.10  4286.8 1379.23  4630.1 1359.87
  4858.4 1352.58  4909.8 1349.66  4967.4 1349.31  4993.3 1343.54  4996.0 1343.04
  4999.3 1343.54  5025.1 1345.85  5046.2 1352.82  5061.5 1350.40  5089.4 1360.83
  5098.0 1363.78  5161.7 1368.66  5223.1 1374.11  5286.1 1377.09  5432.0 1374.82
  5532.2 1376.70  5761.2 1385.82  5900.5 1388.98  6132.0 1392.05  6242.1 1396.62
#Mann=9,-1,0
  3542.5    0.16       0  3991.5     0.1       0  4858.4    0.16       0
  4993.3    0.07       0  4999.3    0.16       0  5089.4     0.1       0
  5161.7    0.16       0  5223.1     0.1       0  5900.5    0.05       0
Bank Sta=4993.3,4999.3
Exp/Cntr=0.3,0.1

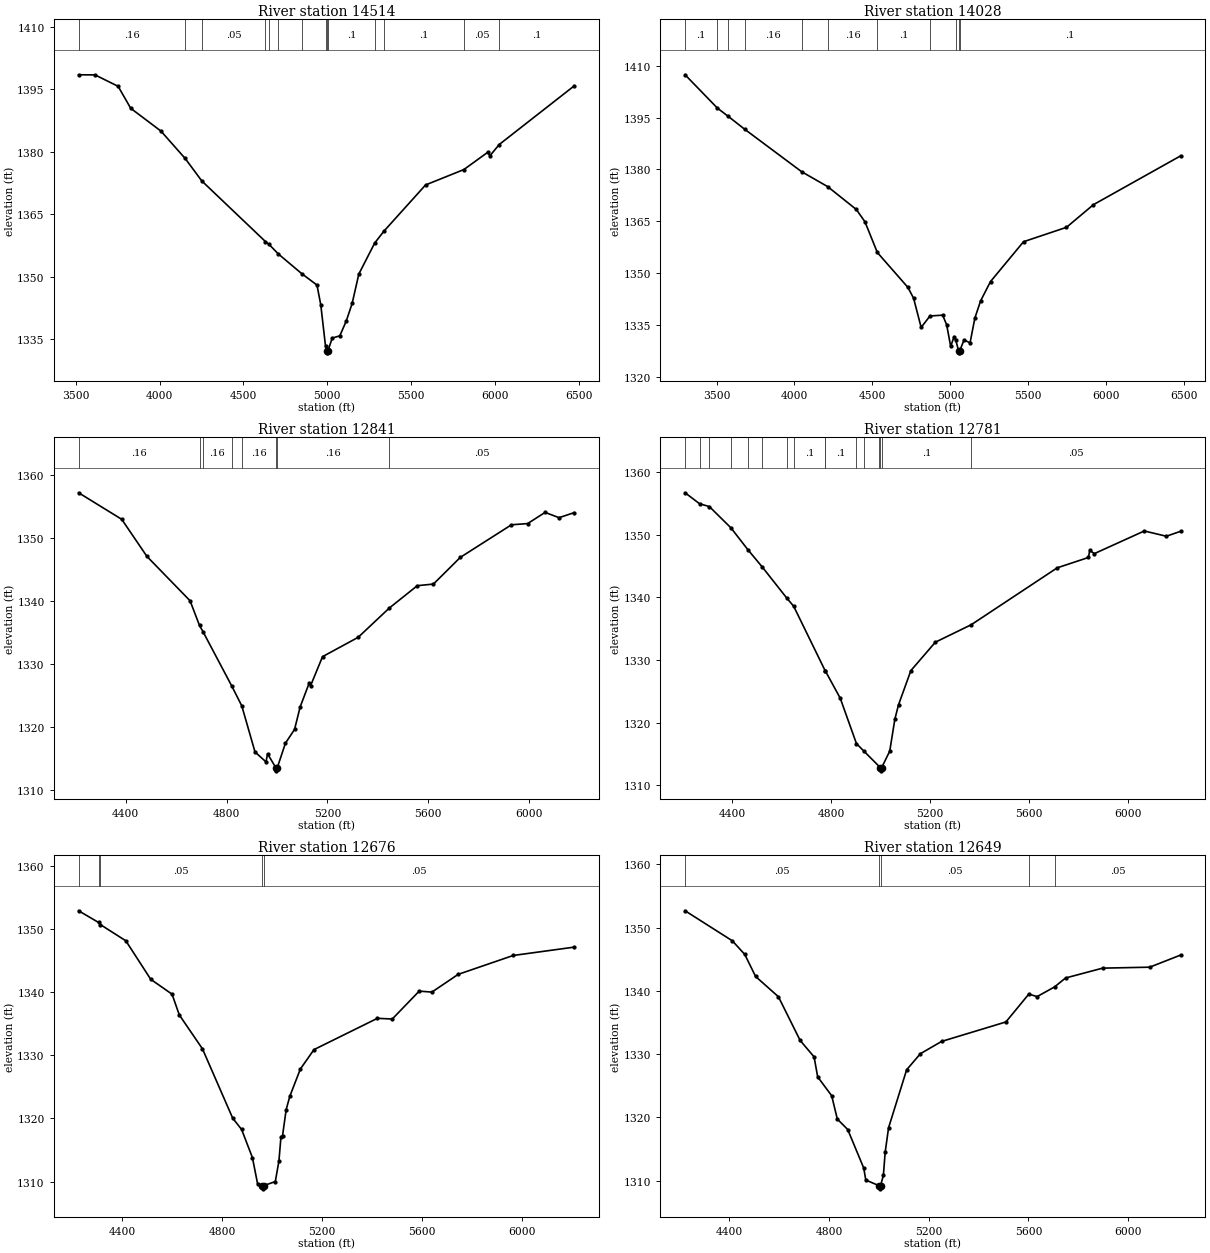
Type RM Length L Ch R = 1,14514,486,486,486
BEGIN DESCRIPTION:
BUFFALO CREEK 33.0
END DESCRIPTION:
XS GIS Cut Line= 4
      2897435.15     10097515.58      2896091.43     10097303.78
      2895626.16     10097526.00      2894709.47     10098095.46
#Sta/Elev= 30
  3517.7 1398.43  3615.6 1398.40  3753.3 1395.66  3828.2 1390.39  4008.3 1384.93
  4153.1 1378.34  4252.3 1372.95  4631.6 1358.41  4652.5 1357.75  4708.9 1355.42
  4847.8 1350.72  4939.1 1347.96  4961.8 1343.20  4990.1 1333.26  4998.6 1332.20
  5001.3 1331.70  5004.6 1332.20  5029.8 1335.24  5075.2 1335.78  5114.0 1339.37
  5148.8 1343.56  5188.6 1350.61  5283.3 1358.05  5337.9 1360.88  5586.7 1371.99
  5814.9 1375.68  5956.0 1379.79  5970.5 1378.99  6025.7 1381.69  6472.8 1395.76
#Mann=14,-1,0
  3517.7    0.16       0  4153.1     0.1       0  4252.3    0.05       0
  4631.6     0.1       0  4652.5    0.16       0  4708.9     0.1       0
  4847.8    0.16       0  4990.1     0.1       0  4998.6    0.07       0
  5004.6     0.1       0  5283.3    0.05       0  5337.9     0.1       0
  5814.9    0.05       0  6025.7     0.1       0
Bank Sta=4998.6,5004.6
Exp/Cntr=0.3,0.1

Type RM Length L Ch R = 1,14028,1187,1187,1187
BEGIN DESCRIPTION:
BUFFALO CREEK 32.0
END DESCRIPTION:
XS GIS Cut Line= 2
      2897407.44     10096345.43      2894407.43     10097394.05
#Sta/Elev= 30
  3298.5 1407.41  3505.5 1397.77  3576.0 1395.34  3682.1 1391.59  4045.6 1379.36
  4212.8 1375.03  4396.7 1368.41  4452.1 1364.84  4531.2 1355.97  4727.5 1345.85
  4763.9 1342.71  4812.3 1334.27  4869.1 1337.58  4950.2 1337.82  4975.9 1335.03
  5001.7 1328.79  5024.1 1331.64  5034.7 1330.56  5052.9 1327.41  5055.7 1326.91
  5058.9 1327.41  5087.7 1330.68  5125.8 1329.77  5156.9 1336.98  5193.6 1341.95
  5257.2 1347.55  5469.0 1359.08  5744.5 1363.25  5917.1 1369.80  6476.5 1383.94
#Mann=11,-1,0
  3298.5     0.1       0  3505.5    0.16       0  3576.0     0.1       0
  3682.1    0.16       0  4045.6     0.1       0  4212.8    0.16       0
  4531.2     0.1       0  4869.1    0.16       0  5034.7     0.1       0
  5052.9    0.07       0  5058.9     0.1       0
Bank Sta=5052.9,5058.9
Exp/Cntr=0.3,0.1

Type RM Length L Ch R = 1,12841,60,60,60
BEGIN DESCRIPTION:
BUFFALO CREEK 31.0
END DESCRIPTION:
XS GIS Cut Line= 3
      2895880.48     10095426.19      2895107.93     10096012.11
      2894175.59     10096359.03
#Sta/Elev= 30
  4213.7 1357.25  4384.5 1353.03  4484.4 1347.13  4655.5 1340.07  4692.9 1336.14
  4706.4 1335.18  4820.9 1326.50  4860.5 1323.35  4912.9 1316.02  4956.5 1314.44
  4962.8 1315.73  4995.2 1313.52  4997.9 1313.02  5001.2 1313.52  5033.5 1317.42
  5069.7 1319.61  5091.7 1323.17  5127.1 1326.92  5133.4 1326.58  5180.5 1331.18
  5321.9 1334.26  5445.1 1338.91  5556.2 1342.47  5620.2 1342.73  5726.9 1346.98
  5929.6 1352.16  5993.6 1352.35  6062.8 1354.13  6118.1 1353.29  6178.1 1354.09
#Mann=8,-1,0
  4213.7    0.16       0  4692.9     0.1       0  4706.4    0.16       0
  4820.9     0.1       0  4860.5    0.16       0  4995.2    0.07       0
  5001.2    0.16       0  5445.1    0.05       0
Bank Sta=4995.2,5001.2
Exp/Cntr=0.3,0.1

Type RM Length L Ch R = 1,12781,105,105,105
BEGIN DESCRIPTION:
BUFFALO CREEK 30.0
END DESCRIPTION:
XS GIS Cut Line= 3
      2895854.46     10095382.77      2895114.44     10095931.82
      2894087.95     10096276.88
#Sta/Elev= 30
  4208.8 1356.71  4267.3 1354.96  4306.9 1354.51  4394.2 1351.11  4463.0 1347.61
  4521.1 1344.85  4619.0 1339.95  4648.0 1338.59  4774.9 1328.33  4775.1 1328.33
  4836.2 1323.92  4901.8 1316.67  4931.2 1315.49  4994.4 1312.99  4997.7 1312.81
  5000.5 1312.31  5003.7 1312.81  5036.5 1315.45  5057.4 1320.59  5072.0 1322.85
  5122.1 1328.32  5221.0 1332.85  5366.2 1335.64  5714.2 1344.73  5840.3 1346.38
  5845.5 1347.50  5864.5 1347.00  6066.2 1350.61  6155.4 1349.77  6213.2 1350.56
#Mann=16,-1,0
  4208.8    0.16       0  4267.3     0.1       0  4306.9    0.16       0
  4394.2     0.1       0  4463.0    0.16       0  4521.1     0.1       0
  4619.0    0.16       0  4648.0     0.1       0  4774.9    0.05       0
  4775.1     0.1       0  4901.8    0.05       0  4931.2    0.16       0
  4994.4     0.1       0  4997.7    0.07       0  5003.7     0.1       0
  5366.2    0.05       0
Bank Sta=4997.7,5003.7
Exp/Cntr=0.3,0.1

Type RM Length L Ch R = 1,12676,27,27,27
BEGIN DESCRIPTION:
BUFFALO CREEK 29.0
END DESCRIPTION:
XS GIS Cut Line= 3
      2895780.65     10095291.65      2895068.86     10095840.67
      2894035.86     10096166.20
#Sta/Elev= 30
  4225.8 1352.84  4305.6 1350.99  4312.6 1350.66  4414.6 1348.09  4514.2 1342.00
  4599.4 1339.65  4628.4 1336.37  4721.1 1331.00  4842.1 1320.03  4877.5 1318.26
  4921.0 1313.79  4941.8 1309.61  4959.6 1309.36  4962.3 1308.86  4965.6 1309.36
  5012.4 1310.01  5026.9 1313.26  5035.1 1317.11  5041.4 1317.28  5055.9 1321.39
  5070.4 1323.49  5112.6 1327.81  5167.1 1330.88  5420.8 1335.83  5480.3 1335.72
  5587.9 1340.13  5638.9 1339.98  5743.7 1342.78  5963.9 1345.77  6207.8 1347.09
#Mann=5,-1,0
  4225.8    0.05       0  4305.6     0.1       0  4312.6    0.05       0
  4959.6    0.04       0  4965.6    0.05       0
Bank Sta=4959.6,4965.6
Exp/Cntr=0.3,0.1

Type RM Length L Ch R = 1,12649,421,421,421
BEGIN DESCRIPTION:
BUFFALO CREEK 28.0
END DESCRIPTION:
XS GIS Cut Line= 3
      2895774.17     10095263.41      2895053.67     10095818.97
      2894012.69     10096100.90
#Sta/Elev= 30
  4222.5 1352.68  4412.1 1347.93  4461.9 1345.78  4505.4 1342.29  4596.9 1339.09
  4683.9 1332.19  4740.0 1329.58  4754.5 1326.41  4810.6 1323.44  4833.3 1319.74
  4875.0 1318.09  4939.3 1311.99  4947.5 1310.10  5000.6 1309.21  5003.4 1308.71
  5006.6 1309.21  5018.1 1310.83  5025.2 1314.47  5038.9 1318.37  5111.4 1327.53
  5166.6 1330.08  5251.7 1332.02  5509.7 1335.10  5601.5 1339.50  5635.0 1339.11
  5704.9 1340.64  5749.0 1342.05  5897.8 1343.61  6086.7 1343.76  6210.8 1345.68
#Mann=5,-1,0
  4222.5    0.05       0  5000.6    0.04       0  5006.6    0.05       0
  5601.5     0.1       0  5704.9    0.05       0
Bank Sta=5000.6,5006.6
Exp/Cntr=0.3,0.1

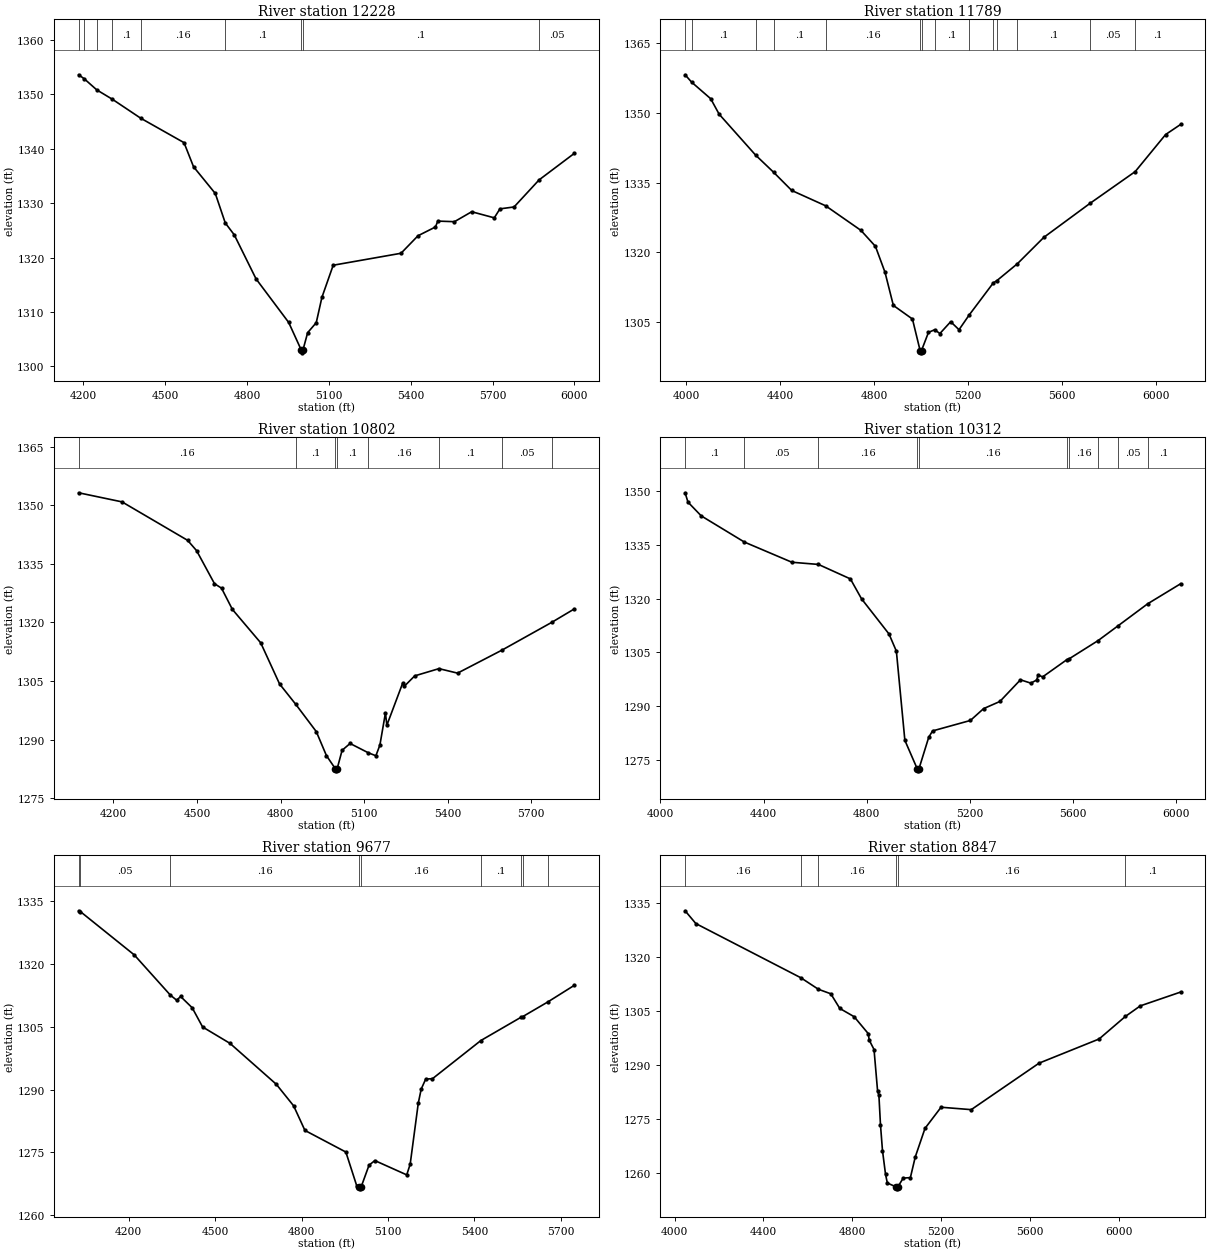
Type RM Length L Ch R = 1,12228,439,439,439
BEGIN DESCRIPTION:
BUFFALO CREEK 27.0
END DESCRIPTION:
XS GIS Cut Line= 2
      2895839.29     10095128.86      2894085.80     10095601.96
#Sta/Elev= 30
  4182.7 1353.62  4203.1 1352.89  4249.2 1350.84  4306.5 1349.11  4409.9 1345.64
  4569.0 1341.13  4603.8 1336.70  4683.6 1331.78  4720.1 1326.36  4753.1 1324.17
  4832.9 1316.07  4952.6 1308.05  4998.8 1302.96  5001.6 1302.46  5004.8 1302.96
  5022.1 1306.17  5053.6 1308.01  5074.3 1312.66  5115.7 1318.58  5364.3 1320.78
  5426.5 1324.00  5490.6 1325.62  5499.0 1326.70  5560.1 1326.59  5623.3 1328.42
  5706.1 1327.30  5726.8 1328.95  5778.6 1329.30  5870.3 1334.28  5998.9 1339.14
#Mann=9,-1,0
  4182.7    0.05       0  4203.1    0.16       0  4249.2    0.05       0
  4306.5     0.1       0  4409.9    0.16       0  4720.1     0.1       0
  4998.8    0.07       0  5004.8     0.1       0  5870.3    0.05       0
Bank Sta=4998.8,5004.8
Exp/Cntr=0.3,0.1

Type RM Length L Ch R = 1,11789,987,987,987
BEGIN DESCRIPTION:
BUFFALO CREEK 26.0
END DESCRIPTION:
XS GIS Cut Line= 3
      2895926.06     10095003.00      2895131.80     10094868.45
      2893868.75     10095193.98
#Sta/Elev= 30
  3995.5 1358.24  4023.5 1356.64  4104.6 1353.08  4140.5 1349.75  4295.8 1340.94
  4371.9 1337.27  4449.5 1333.33  4593.9 1330.03  4744.1 1324.74  4805.9 1321.30
  4846.6 1315.73  4882.2 1308.58  4963.5 1305.65  4996.1 1298.87  4998.8 1298.37
  5002.1 1298.87  5031.7 1302.77  5057.9 1303.34  5080.4 1302.53  5126.3 1305.07
  5161.8 1303.35  5204.5 1306.48  5307.5 1313.41  5323.6 1313.94  5410.6 1317.57
  5522.8 1323.23  5719.7 1330.56  5911.9 1337.39  6041.4 1345.37  6105.4 1347.55
#Mann=14,-1,0
  3995.5    0.05       0  4023.5     0.1       0  4295.8    0.16       0
  4371.9     0.1       0  4593.9    0.16       0  4996.1    0.07       0
  5002.1    0.16       0  5057.9     0.1       0  5204.5    0.05       0
  5307.5    0.16       0  5323.6    0.05       0  5410.6     0.1       0
  5719.7    0.05       0  5911.9     0.1       0
Bank Sta=4996.1,5002.1
Exp/Cntr=0.3,0.1

Type RM Length L Ch R = 1,10802,490,490,490
BEGIN DESCRIPTION:
BUFFALO CREEK 24.0
END DESCRIPTION:
XS GIS Cut Line= 4
      2895736.81     10094397.96      2895046.73     10094176.61
      2894764.61     10093946.58      2894083.32     10094055.06
#Sta/Elev= 30
  4075.1 1353.16  4230.9 1350.83  4466.3 1340.99  4498.4 1338.36  4562.7 1329.90
  4588.0 1328.75  4626.9 1323.32  4728.6 1314.77  4796.3 1304.24  4854.3 1299.04
  4928.1 1292.05  4964.7 1285.88  4996.9 1282.51  4999.6 1282.01  5002.9 1282.51
  5020.7 1287.26  5049.4 1289.01  5115.1 1286.62  5142.0 1285.87  5156.4 1288.60
  5176.3 1296.83  5181.4 1293.68  5238.5 1304.51  5243.6 1303.62  5281.4 1306.31
  5368.4 1308.16  5435.2 1307.01  5594.6 1312.90  5773.6 1320.02  5853.7 1323.42
#Mann=8,-1,0
  4075.1    0.16       0  4854.3     0.1       0  4996.9    0.07       0
  5002.9     0.1       0  5115.1    0.16       0  5368.4     0.1       0
  5594.6    0.05       0  5773.6     0.1       0
Bank Sta=4996.9,5002.9
Exp/Cntr=0.3,0.1

Type RM Length L Ch R = 1,10312,635,635,635
BEGIN DESCRIPTION:
BUFFALO CREEK 23.0
END DESCRIPTION:
XS GIS Cut Line= 3
      2895819.34     10093408.37      2894777.63     10093642.76
      2894005.04     10094003.01
#Sta/Elev= 30
  4096.0 1349.47  4107.1 1346.87  4158.4 1343.04  4325.6 1335.74  4509.8 1330.11
  4612.7 1329.50  4736.5 1325.47  4779.7 1319.92  4886.1 1310.12  4914.7 1305.33
  4947.6 1280.48  4995.9 1272.48  4998.6 1271.98  5001.9 1272.48  5039.9 1281.30
  5054.8 1283.10  5201.5 1286.02  5252.7 1289.32  5315.8 1291.31  5395.5 1297.35
  5435.7 1296.42  5458.5 1297.30  5464.0 1298.70  5481.4 1298.16  5574.2 1302.90
  5585.3 1303.25  5696.4 1308.28  5772.8 1312.35  5888.6 1318.54  6016.2 1324.12
#Mann=10,-1,0
  4096.0     0.1       0  4325.6    0.05       0  4612.7    0.16       0
  4995.9    0.07       0  5001.9    0.16       0  5574.2     0.1       0
  5585.3    0.16       0  5696.4     0.1       0  5772.8    0.05       0
  5888.6     0.1       0
Bank Sta=4995.9,5001.9
Exp/Cntr=0.3,0.1

Type RM Length L Ch R = 1,9677,830,830,830
BEGIN DESCRIPTION:
BUFFALO CREEK 21.0
END DESCRIPTION:
XS GIS Cut Line= 3
      2895450.34     10093130.61      2894252.46     10093265.15
      2893888.38     10093629.23
#Sta/Elev= 30
  4025.8 1332.78  4031.6 1332.60  4218.9 1322.23  4344.1 1312.62  4366.1 1311.39
  4379.9 1312.28  4420.1 1309.58  4456.2 1304.99  4551.3 1301.07  4712.0 1291.29
  4772.3 1286.12  4811.4 1280.25  4953.5 1275.08  4991.6 1266.93  5000.8 1266.78
  5003.5 1266.28  5006.8 1266.78  5034.0 1271.94  5054.1 1273.04  5164.8 1269.62
  5176.8 1272.18  5205.0 1286.81  5215.1 1290.15  5230.7 1292.53  5254.2 1292.62
  5422.0 1301.74  5560.5 1307.27  5567.8 1307.48  5654.5 1310.97  5746.1 1314.93
#Mann=9,-1,0
  4025.8     0.1       0  4031.6    0.05       0  4344.1    0.16       0
  5000.8    0.07       0  5006.8    0.16       0  5422.0     0.1       0
  5560.5    0.05       0  5567.8     0.1       0  5654.5    0.05       0
Bank Sta=5000.8,5006.8
Exp/Cntr=0.3,0.1

Type RM Length L Ch R = 1,8847,666,666,666
BEGIN DESCRIPTION:
BUFFALO CREEK 20.0
END DESCRIPTION:
XS GIS Cut Line= 4
      2895615.29     10092705.25      2894816.69     10092496.92
      2894534.58     10092648.83      2893853.29     10093495.01
#Sta/Elev= 30
  4047.6 1332.79  4096.0 1329.24  4569.0 1314.18  4648.1 1310.98  4703.9 1309.73
  4744.4 1305.66  4809.1 1303.36  4872.9 1298.64  4876.7 1296.89  4898.6 1294.25
  4914.8 1282.61  4920.5 1281.64  4927.7 1273.30  4936.7 1266.17  4950.4 1259.59
  4958.6 1257.16  4999.4 1256.04  5002.2 1255.54  5005.4 1256.04  5030.0 1258.52
  5062.4 1258.66  5084.3 1264.39  5128.2 1272.34  5200.6 1278.21  5336.5 1277.54
  5642.1 1290.46  5912.4 1297.17  6030.5 1303.42  6098.0 1306.37  6279.7 1310.21
#Mann=6,-1,0
  4047.6    0.16       0  4569.0    0.05       0  4648.1    0.16       0
  4999.4    0.07       0  5005.4    0.16       0  6030.5     0.1       0
Bank Sta=4999.4,5005.4
Exp/Cntr=0.3,0.1