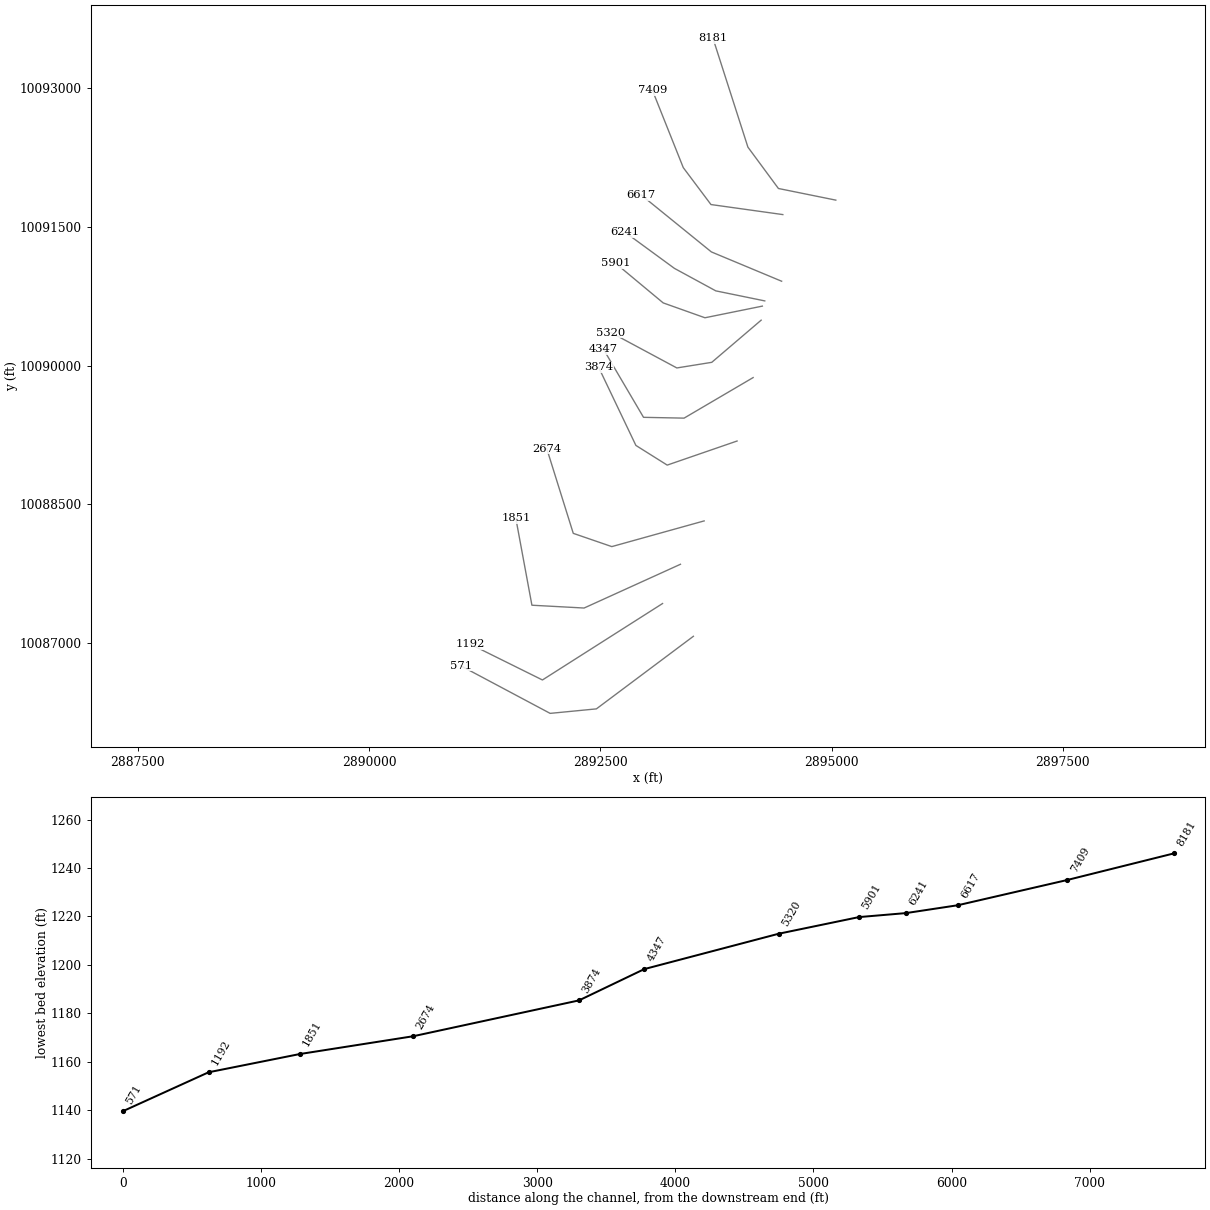
HEC-RAS study BUFFALO CREEK.prj: BUFFALO CREEK Base Level Engineering

--- BUFFALO CREEK.g01 (geometry) --- (continued)

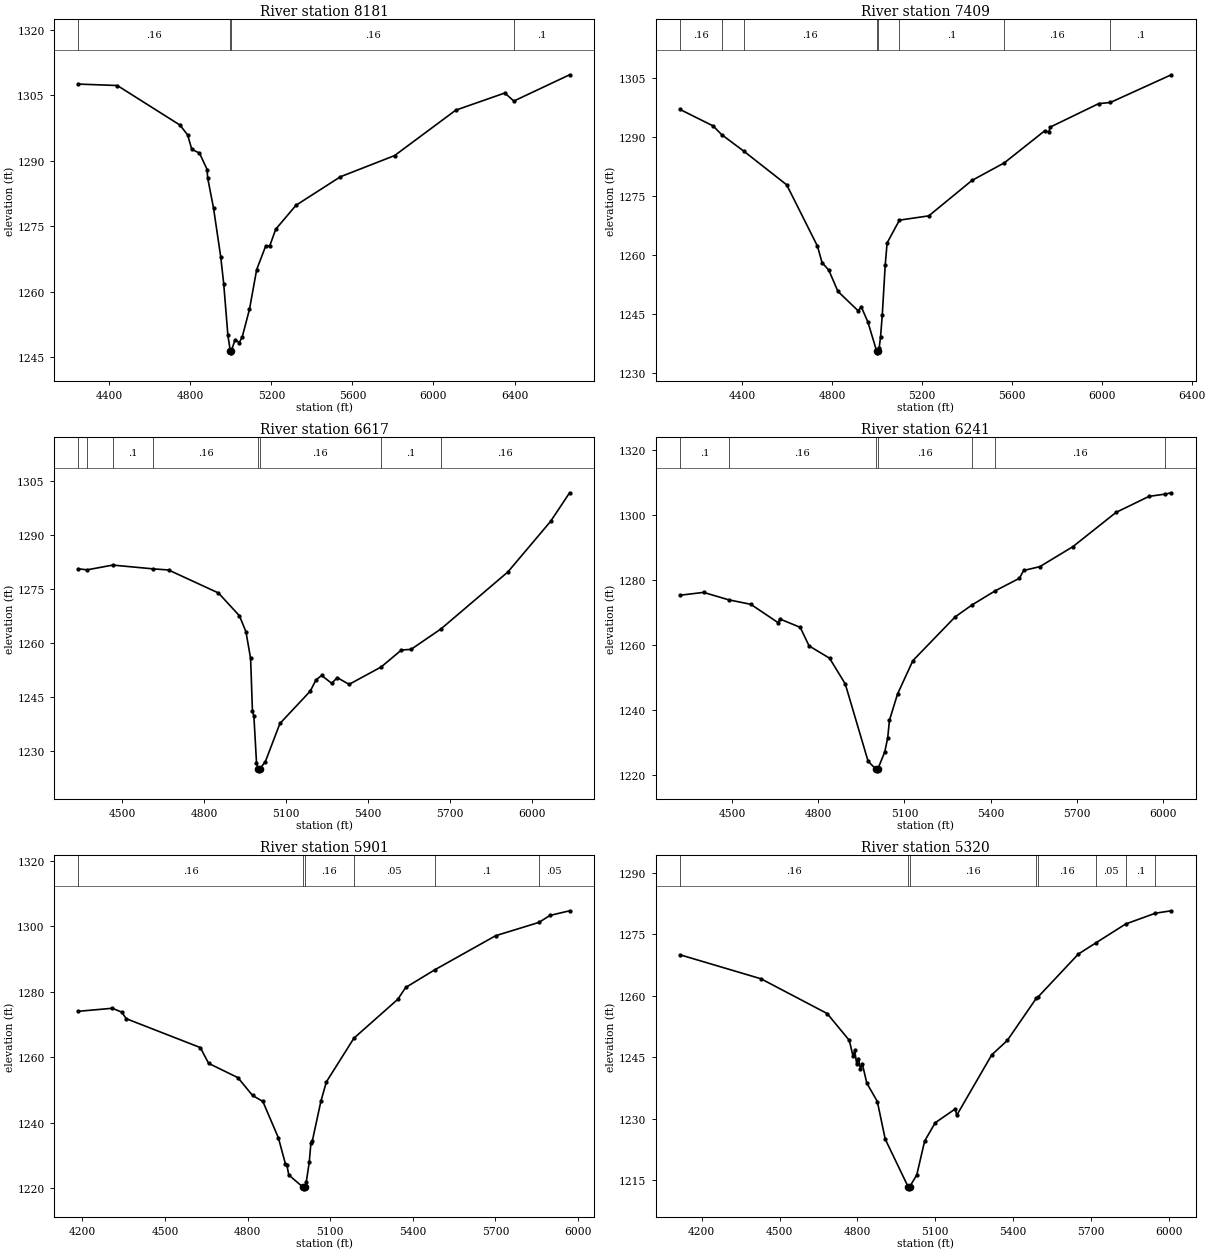
Type RM Length L Ch R = 1,8181,772,772,772
BEGIN DESCRIPTION:
BUFFALO CREEK 18.0
END DESCRIPTION:
XS GIS Cut Line= 4
      2895046.70     10091789.46      2894426.07     10091915.33
      2894096.21     10092362.37      2893718.60     10093538.61
#Sta/Elev= 30
  4247.6 1307.56  4439.7 1307.23  4749.0 1298.17  4786.6 1295.92  4807.0 1292.64
  4845.2 1291.75  4883.0 1287.98  4885.2 1286.15  4914.4 1279.18  4949.9 1268.03
  4964.6 1261.89  4985.4 1250.00  4997.0 1246.53  4999.8 1246.03  5003.0 1246.53
  5020.9 1249.07  5041.7 1248.37  5056.4 1249.72  5091.9 1256.01  5127.4 1265.09
  5171.3 1270.41  5192.1 1270.54  5221.4 1274.33  5321.6 1279.82  5540.6 1286.34
  5808.0 1291.19  6110.0 1301.59  6351.6 1305.51  6396.7 1303.68  6671.8 1309.69
#Mann=4,-1,0
  4247.6    0.16       0  4997.0    0.07       0  5003.0    0.16       0
  6396.7     0.1       0
Bank Sta=4997,5003
Exp/Cntr=0.3,0.1

Type RM Length L Ch R = 1,7409,792,792,792
BEGIN DESCRIPTION:
BUFFALO CREEK 17.0
END DESCRIPTION:
XS GIS Cut Line= 4
      2894473.80     10091633.21      2893696.90     10091741.71
      2893397.42     10092141.02      2893063.35     10092978.37
#Sta/Elev= 30
  4124.0 1296.89  4270.7 1292.72  4308.8 1290.51  4409.0 1286.23  4598.3 1277.74
  4735.2 1262.15  4755.4 1257.99  4785.7 1256.04  4826.1 1250.67  4915.7 1245.75
  4930.3 1246.71  4959.4 1242.87  4998.1 1235.55  5000.9 1235.05  5004.1 1235.55
  5009.4 1236.23  5015.7 1239.07  5023.5 1244.72  5036.5 1257.35  5044.9 1262.98
  5099.8 1268.77  5230.3 1269.86  5422.4 1278.86  5566.8 1283.35  5745.9 1291.47
  5764.7 1291.16  5770.1 1292.40  5985.7 1298.37  6037.9 1298.67  6309.1 1305.71
#Mann=8,-1,0
  4124.0    0.16       0  4308.8     0.1       0  4409.0    0.16       0
  4998.1    0.07       0  5004.1    0.16       0  5099.8     0.1       0
  5566.8    0.16       0  6037.9     0.1       0
Bank Sta=4998.1,5004.1
Exp/Cntr=0.3,0.1

Type RM Length L Ch R = 1,6617,376,376,376
BEGIN DESCRIPTION:
BUFFALO CREEK 15.0
END DESCRIPTION:
XS GIS Cut Line= 3
      2894460.81     10090912.71      2893701.24     10091229.56
      2892942.58     10091845.16
#Sta/Elev= 30
  4338.7 1280.71  4370.4 1280.42  4464.7 1281.74  4612.5 1280.69  4668.9 1280.38
  4851.9 1274.00  4928.8 1267.66  4952.6 1263.25  4969.7 1255.85  4976.4 1241.36
  4981.8 1239.77  4991.3 1226.90  4997.2 1225.13  5000.0 1224.63  5003.2 1225.13
  5023.9 1227.21  5077.1 1237.77  5188.4 1246.76  5209.2 1249.88  5230.0 1251.10
  5266.7 1248.94  5287.5 1250.49  5330.6 1248.63  5448.0 1253.45  5522.4 1258.17
  5557.6 1258.34  5667.3 1264.02  5912.5 1279.83  6069.1 1293.88  6138.7 1301.81
#Mann=8,-1,0
  4338.7     0.1       0  4370.4    0.16       0  4464.7     0.1       0
  4612.5    0.16       0  4997.2    0.07       0  5003.2    0.16       0
  5448.0     0.1       0  5667.3    0.16       0
Bank Sta=4997.2,5003.2
Exp/Cntr=0.3,0.1

Type RM Length L Ch R = 1,6241,340,340,340
BEGIN DESCRIPTION:
BUFFALO CREEK 14.0
END DESCRIPTION:
XS GIS Cut Line= 4
      2894278.46     10090700.06      2893748.99     10090808.55
      2893301.94     10091051.61      2892768.11     10091442.21
#Sta/Elev= 30
  4318.5 1275.31  4400.2 1276.18  4488.1 1273.89  4564.8 1272.52  4660.5 1266.85
  4665.6 1268.03  4737.0 1265.44  4767.6 1259.76  4839.1 1255.96  4893.7 1248.08
  4973.4 1224.30  5000.9 1221.88  5003.6 1221.38  5006.9 1221.88  5031.4 1227.19
  5041.7 1231.56  5047.6 1236.89  5075.8 1244.96  5129.3 1255.23  5276.5 1268.66
  5335.2 1272.32  5416.0 1276.66  5500.3 1280.51  5515.0 1282.91  5571.4 1284.08
  5686.4 1290.21  5837.0 1300.75  5952.0 1305.67  6007.3 1306.35  6029.3 1306.77
#Mann=7,-1,0
  4318.5     0.1       0  4488.1    0.16       0  5000.9    0.07       0
  5006.9    0.16       0  5335.2    0.05       0  5416.0    0.16       0
  6007.3    0.05       0
Bank Sta=5000.9,5006.9
Exp/Cntr=0.3,0.1

Type RM Length L Ch R = 1,5901,581,581,581
BEGIN DESCRIPTION:
BUFFALO CREEK 13.0
END DESCRIPTION:
XS GIS Cut Line= 4
      2894252.49     10090643.63      2893631.80     10090517.76
      2893180.41     10090678.35      2892663.91     10091108.04
#Sta/Elev= 30
  4185.2 1274.04  4308.6 1274.97  4342.4 1273.78  4359.2 1271.77  4628.1 1262.94
  4658.1 1258.12  4764.6 1253.74  4817.7 1248.30  4855.2 1246.46  4911.6 1235.33
  4937.1 1227.39  4942.4 1227.02  4949.4 1223.97  5001.1 1220.23  5003.9 1219.73
  5007.1 1220.23  5013.1 1221.93  5023.7 1227.81  5029.7 1233.65  5035.0 1234.41
  5066.2 1246.59  5086.0 1252.45  5186.2 1265.84  5345.4 1277.71  5374.1 1281.33
  5479.1 1286.70  5700.8 1297.16  5857.3 1301.21  5898.7 1303.38  5969.5 1304.79
#Mann=6,-1,0
  4185.2    0.16       0  5001.1    0.07       0  5007.1    0.16       0
  5186.2    0.05       0  5479.1     0.1       0  5857.3    0.05       0
Bank Sta=5001.1,5007.1
Exp/Cntr=0.3,0.1

Type RM Length L Ch R = 1,5320,973,973,973
BEGIN DESCRIPTION:
BUFFALO CREEK 12.0
END DESCRIPTION:
XS GIS Cut Line= 4
      2894239.47     10090491.74      2893705.58     10090035.99
      2893327.98     10089975.22      2892616.20     10090357.15
#Sta/Elev= 30
  4116.7 1269.99  4428.2 1264.14  4683.4 1255.65  4768.5 1249.10  4782.8 1245.26
  4789.4 1246.66  4797.1 1243.26  4803.7 1244.66  4811.4 1242.17  4818.7 1243.34
  4836.0 1238.66  4876.5 1234.18  4906.9 1225.00  4995.1 1213.36  4997.8 1212.86
  5001.1 1213.36  5028.4 1216.26  5058.8 1224.53  5099.3 1228.98  5177.2 1232.39
  5182.2 1230.80  5317.0 1245.55  5377.1 1249.08  5489.2 1259.41  5494.8 1259.64
  5650.8 1270.17  5718.5 1272.91  5833.1 1277.51  5947.7 1280.15  6008.9 1280.74
#Mann=8,-1,0
  4116.7    0.16       0  4995.1    0.07       0  5001.1    0.16       0
  5489.2     0.1       0  5494.8    0.16       0  5718.5    0.05       0
  5833.1     0.1       0  5947.7    0.05       0
Bank Sta=4995.1,5001.1
Exp/Cntr=0.3,0.1

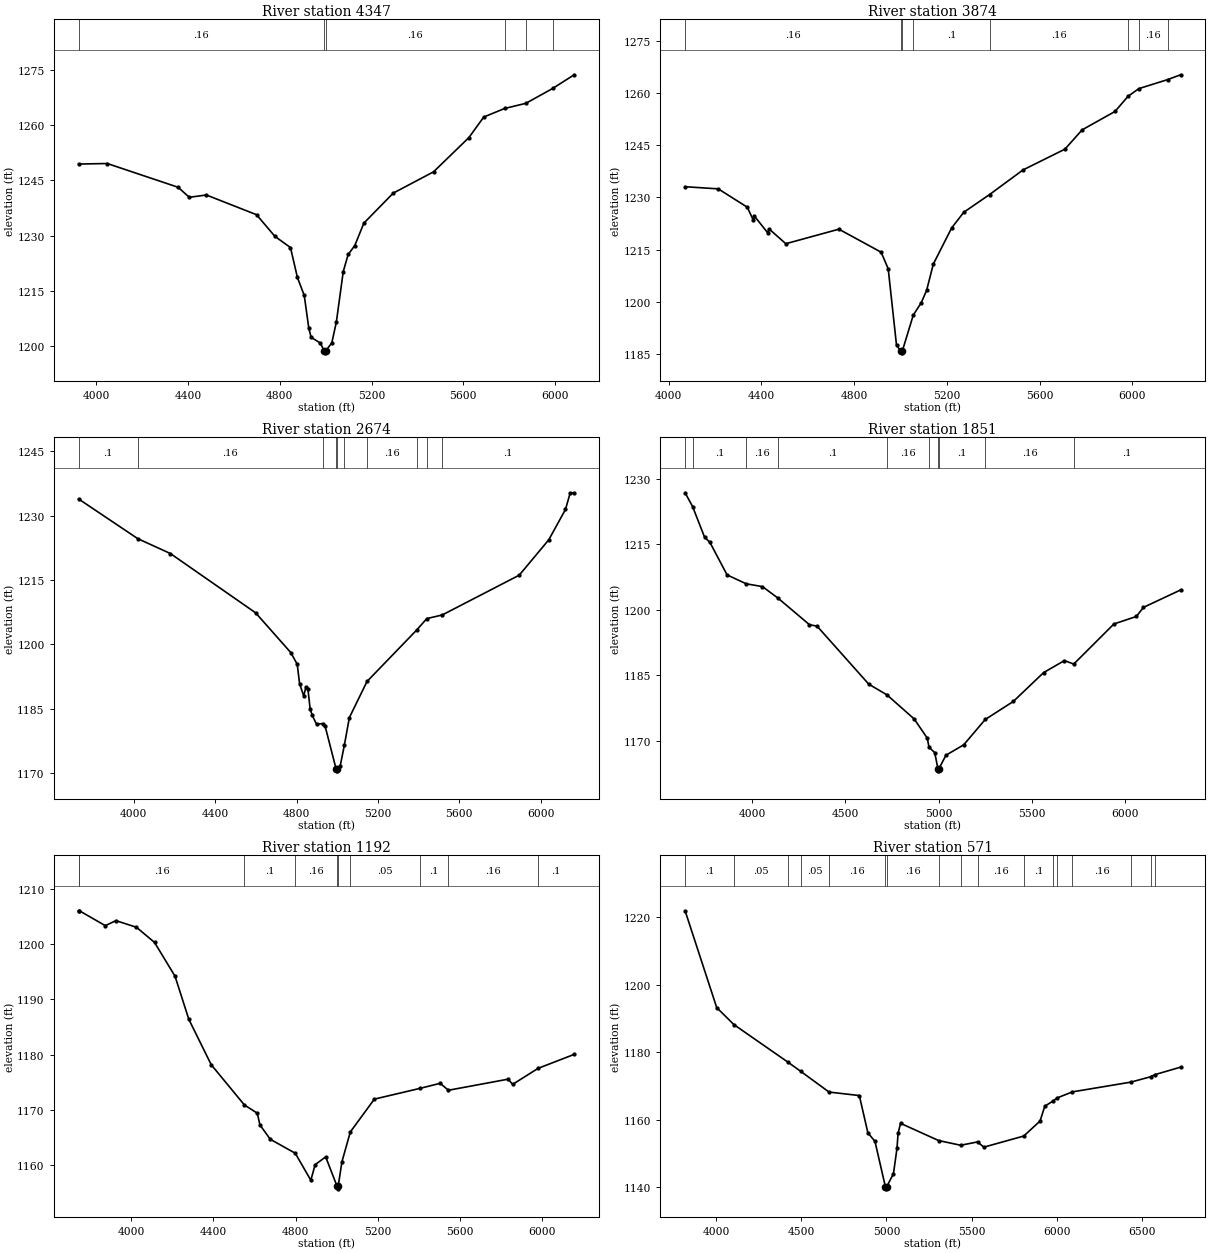
Type RM Length L Ch R = 1,4347,473,473,473
BEGIN DESCRIPTION:
BUFFALO CREEK 10.0
END DESCRIPTION:
XS GIS Cut Line= 4
      2894152.64     10089871.06      2893406.10     10089432.69
      2892967.74     10089441.37      2892533.87     10090178.94
#Sta/Elev= 30
  3923.4 1249.45  4048.2 1249.59  4357.0 1243.15  4405.7 1240.43  4480.0 1241.06
  4698.8 1235.71  4778.9 1229.84  4846.8 1226.80  4876.8 1218.74  4906.8 1213.81
  4926.8 1204.88  4936.8 1202.46  4976.8 1200.93  4993.8 1198.76  4996.6 1198.26
  4999.8 1198.76  5026.8 1200.94  5046.8 1206.62  5076.8 1220.31  5098.2 1224.93
  5126.8 1227.32  5166.8 1233.44  5294.6 1241.56  5470.4 1247.34  5624.7 1256.64
  5689.1 1262.19  5779.9 1264.51  5872.8 1265.91  5989.8 1269.95  6083.3 1273.65
#Mann=6,-1,0
  3923.4    0.16       0  4993.8    0.07       0  4999.8    0.16       0
  5779.9     0.1       0  5872.8    0.16       0  5989.8     0.1       0
Bank Sta=4993.8,4999.8
Exp/Cntr=0.3,0.1

Type RM Length L Ch R = 1,3874,1200,1200,1200
BEGIN DESCRIPTION:
BUFFALO CREEK 8.0
END DESCRIPTION:
XS GIS Cut Line= 4
      2893979.04     10089185.30      2893223.81     10088924.87
      2892885.27     10089137.55      2892481.60     10089983.95
#Sta/Elev= 30
  4071.3 1233.06  4214.4 1232.44  4339.2 1227.18  4365.2 1223.51  4370.5 1224.59
  4427.6 1219.80  4432.9 1220.96  4505.6 1216.68  4734.3 1220.86  4916.4 1214.25
  4947.0 1209.47  4982.8 1187.49  5001.7 1185.83  5004.5 1185.33  5007.7 1185.83
  5055.0 1196.16  5089.6 1199.76  5112.7 1203.30  5141.4 1210.83  5220.3 1221.20
  5272.7 1225.72  5383.8 1230.80  5527.9 1237.87  5708.9 1243.85  5783.1 1249.40
  5924.8 1254.68  5981.0 1259.04  6027.9 1261.25  6151.1 1263.82  6207.7 1265.22
#Mann=8,-1,0
  4071.3    0.16       0  5001.7    0.07       0  5007.7    0.16       0
  5055.0     0.1       0  5383.8    0.16       0  5981.0     0.1       0
  6027.9    0.16       0  6151.1     0.1       0
Bank Sta=5001.7,5007.7
Exp/Cntr=0.3,0.1

Type RM Length L Ch R = 1,2674,823,823,823
BEGIN DESCRIPTION:
BUFFALO CREEK 6.0
END DESCRIPTION:
XS GIS Cut Line= 4
      2893623.11     10088321.57      2892624.85     10088043.80
      2892208.19     10088187.03      2891921.74     10089102.79
#Sta/Elev= 30
  3728.7 1233.92  4019.5 1224.67  4179.9 1221.20  4598.8 1207.38  4771.6 1198.12
  4803.4 1195.38  4815.0 1190.85  4835.1 1188.02  4846.3 1190.05  4856.2 1189.53
  4866.8 1184.99  4877.5 1183.44  4898.2 1181.40  4929.1 1181.56  4940.8 1180.89
  4994.2 1171.03  4996.9 1170.53  5000.2 1171.03  5014.8 1171.69  5035.0 1176.47
  5059.7 1182.94  5146.5 1191.37  5391.7 1203.41  5440.4 1206.03  5516.5 1206.88
  5895.0 1216.16  6040.3 1224.42  6122.3 1231.49  6145.0 1235.26  6165.0 1235.37
#Mann=10,-1,0
  3728.7     0.1       0  4019.5    0.16       0  4929.1     0.1       0
  4994.2    0.07       0  5000.2     0.1       0  5035.0     0.1       0
  5146.5    0.16       0  5391.7     0.1       0  5440.4    0.05       0
  5516.5     0.1       0
Bank Sta=4994.2,5000.2
Exp/Cntr=0.3,0.1

Type RM Length L Ch R = 1,1851,659,659,659
BEGIN DESCRIPTION:
BUFFALO CREEK 4.0
END DESCRIPTION:
XS GIS Cut Line= 4
      2893367.06     10087852.84      2892325.37     10087379.74
      2891761.14     10087410.12      2891587.52     10088347.63
#Sta/Elev= 30
  3638.3 1226.78  3678.6 1223.63  3743.0 1216.61  3771.6 1215.44  3863.9 1207.99
  3967.0 1205.95  4054.0 1205.31  4137.7 1202.67  4306.7 1196.59  4347.3 1196.27
  4625.2 1182.99  4723.6 1180.52  4869.4 1175.02  4939.5 1170.64  4948.8 1168.57
  4979.6 1167.33  4996.6 1163.66  4999.4 1163.16  5002.6 1163.66  5039.7 1166.73
  5135.3 1169.11  5250.9 1174.91  5402.0 1179.04  5564.7 1185.64  5676.6 1188.39
  5726.6 1187.59  5942.4 1196.76  6063.0 1198.48  6101.1 1200.56  6300.9 1204.55
#Mann=10,-1,0
  3638.3    0.16       0  3678.6     0.1       0  3967.0    0.16       0
  4137.7     0.1       0  4723.6    0.16       0  4948.8     0.1       0
  4996.6    0.07       0  5002.6     0.1       0  5250.9    0.16       0
  5726.6     0.1       0
Bank Sta=4996.6,5002.6
Exp/Cntr=0.3,0.1

Type RM Length L Ch R = 1,1192,621,621,621
BEGIN DESCRIPTION:
BUFFALO CREEK 2.0
END DESCRIPTION:
XS GIS Cut Line= 3
      2893173.44     10087428.33      2891874.85     10086601.96
      2891091.77     10086990.03
#Sta/Elev= 30
  3743.4 1206.10  3747.1 1206.10  3873.4 1203.40  3925.0 1204.31  4024.9 1203.11
  4113.0 1200.36  4212.9 1194.22  4279.8 1186.42  4389.0 1178.17  4550.9 1170.85
  4613.4 1169.37  4626.4 1167.23  4676.9 1164.63  4798.4 1162.10  4874.1 1157.20
  4895.3 1160.03  4946.5 1161.44  5001.5 1156.14  5004.3 1155.64  5007.5 1156.14
  5025.7 1160.56  5066.4 1165.96  5183.5 1171.92  5405.7 1173.87  5504.0 1174.79
  5544.2 1173.53  5834.7 1175.54  5857.1 1174.60  5981.2 1177.51  6156.6 1180.04
#Mann=10,-1,0
  3743.4     0.1       0  3747.1    0.16       0  4550.9     0.1       0
  4798.4    0.16       0  5001.5    0.07       0  5007.5    0.16       0
  5066.4    0.05       0  5405.7     0.1       0  5544.2    0.16       0
  5981.2     0.1       0
Bank Sta=5001.5,5007.5
Exp/Cntr=0.3,0.1

Type RM Length L Ch R = 1,571,0,0,0
BEGIN DESCRIPTION:
BUFFALO CREEK 1.0
END DESCRIPTION:
XS GIS Cut Line= 4
      2893506.81     10087074.19      2892458.19     10086289.46
      2891958.19     10086240.85      2890993.21     10086754.57
#Sta/Elev= 30
  3819.4 1221.87  4004.7 1193.21  4105.4 1188.18  4424.5 1176.98  4497.7 1174.32
  4663.4 1168.20  4840.9 1167.17  4891.0 1156.14  4932.6 1153.60  4994.2 1140.05
  4997.0 1139.55  5000.2 1140.05  5041.0 1144.04  5061.8 1151.58  5068.1 1156.03
  5082.7 1158.94  5305.6 1153.85  5435.2 1152.45  5534.0 1153.44  5570.9 1151.89
  5804.8 1155.18  5900.5 1159.62  5928.2 1164.01  5976.1 1165.53  6000.6 1166.47
  6090.5 1168.26  6433.7 1171.15  6548.1 1172.73  6573.3 1173.35  6724.7 1175.58
#Mann=17,-1,0
  3819.4     0.1       0  4105.4    0.05       0  4424.5    0.16       0
  4497.7    0.05       0  4663.4    0.16       0  4994.2    0.07       0
  5000.2    0.16       0  5305.6    0.05       0  5435.2     0.1       0
  5534.0    0.16       0  5804.8     0.1       0  5976.1    0.16       0
  6000.6     0.1       0  6090.5    0.16       0  6433.7     0.1       0
  6548.1    0.16       0  6573.3     0.1       0
Bank Sta=4994.2,5000.2
Exp/Cntr=0.3,0.1

Chan Stop Cuts=-1