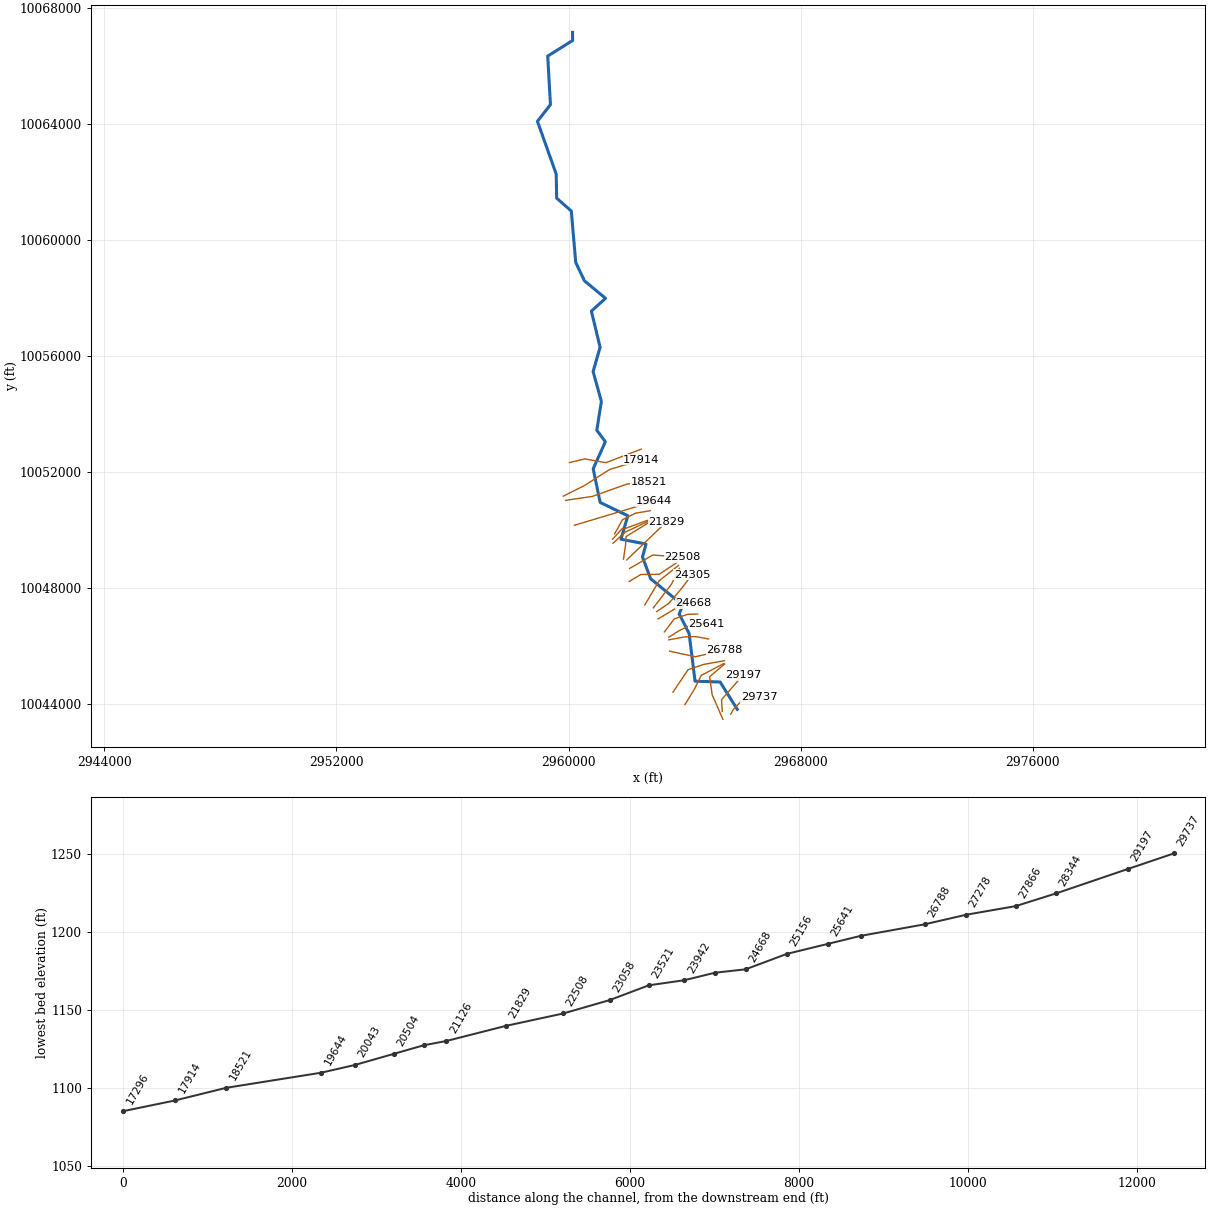
--- CALOHAN CREEK.prj (project) ---

Proj Title=CALOHAN CREEK Base Level Engineering
Current Plan=p01
Default Exp/Contr=0.3,0.1
English Units
Geom File=g01
Flow File=f01
Plan File=p01
Y Axis Title=Elevation
X Axis Title(PF)=Main Channel Distance
X Axis Title(XS)=Station
BEGIN DESCRIPTION:
CALOHAN CREEK
END DESCRIPTION:
DSS Export Rating Curves= 0
DSS Export Rating Curve Sorted= 0
DSS Export Volume Flow Curves= 0
DXF OffsetX= 0
DXF OffsetY= 0
DXF ScaleX= 1
DXF ScaleY= 10

--- CALOHAN CREEK.p01 (plan) ---

Plan Title=Multiple Run
Short Identifier=Multiple
Geom File=g01
Flow File=f01
Subcritical Flow
K Sum by GR= 0
Std Step Tol= 0.01
Critical Tol= 0.01
Num of Std Step Trials= 20
Max Error Tol= 0.3
Flow Tol Ratio= 0.001
Split Flow NTrial= 30
Split Flow Tol= 0.02
Split Flow Ratio= 0.02
Log Output Level= 0
Friction Slope Method= 1
Unsteady Friction Slope Method= 2
Unsteady Bridges Friction Slope Method= 1
Parabolic Critical Depth
Global Vel Dist=  1 , 1 , 1
Global Log Level= 0
CheckData=True
Encroach Param= -1, 0, 0, 0
BEGIN DESCRIPTION:
Multiple Run
END DESCRIPTION:

--- CALOHAN CREEK.f01 (steady flow) ---

Flow Title=Multiple
Program Version=4.10
Number of Profiles= 7
Profile Names=10-year,25-year,50-year,1pct_min,100-year,1pct_plu,500-year
River Rch & RM=CALOHAN CREEK,Reach-1         ,29737
    1085    1601    2058    1938    2622    3545    4268
River Rch & RM=CALOHAN CREEK,Reach-1         ,27278
    1188    1755    2257    2127    2876    3889    4683
River Rch & RM=CALOHAN CREEK,Reach-1         ,24305
    1356    2015    2601    2457    3323    4493    5442
River Rch & RM=CALOHAN CREEK,Reach-1         ,21829
    1472    2192    2834    2680    3625    4902    5951
River Rch & RM=CALOHAN CREEK,Reach-1         ,19644
    2286    3471    4547    4349    5882    7954    9882
River Rch & RM=CALOHAN CREEK,Reach-1         ,18521
    2286    3471    4547    4349    5882    7954    9882
River Rch & RM=CALOHAN CREEK,Reach-1         ,12852
    2682    4095    5383    5164    6983    9444   11803
River Rch & RM=CALOHAN CREEK,Reach-1         ,8769
    2916    4464    5878    5645    7635   10325   12936
River Rch & RM=CALOHAN CREEK,Reach-1         ,6699
    3029    4632    6094    5846    7906   10691   13363
Boundary for River Rch & Prof#=CALOHAN CREEK,Reach-1         , 1
Up Type= 0
Dn Type= 3
Dn Slope=0.005
Boundary for River Rch & Prof#=CALOHAN CREEK,Reach-1         , 2
Up Type= 0
Dn Type= 3
Dn Slope=0.005
Boundary for River Rch & Prof#=CALOHAN CREEK,Reach-1         , 3
Up Type= 0
Dn Type= 3
Dn Slope=0.005
Boundary for River Rch & Prof#=CALOHAN CREEK,Reach-1         , 4
Up Type= 0
Dn Type= 3
Dn Slope=0.005
Boundary for River Rch & Prof#=CALOHAN CREEK,Reach-1         , 5
Up Type= 0
Dn Type= 3
Dn Slope=0.005
Boundary for River Rch & Prof#=CALOHAN CREEK,Reach-1         , 6
Up Type= 0
Dn Type= 3
Dn Slope=0.005
Boundary for River Rch & Prof#=CALOHAN CREEK,Reach-1         , 7
Up Type= 0
Dn Type= 3
Dn Slope=0.005
DSS Import GetInterval= 0
DSS Import GetPeak= 0
DSS Import FillOption= 0

--- CALOHAN CREEK.g01 (geometry) ---

Geom Title=Existing Conditions
Program Version=4.10

River Reach=CALOHAN CREEK   ,Reach-1
Reach XY= 30
      2965815.87     10043814.15      2965224.89     10044756.14
      2964360.76     10044784.68      2964156.05     10046432.67
      2963814.99      10047100.1      2963936.23     10047408.45
      2962830.93     10048314.75       2962549.5     10049064.35
      2962670.99     10049511.32      2961808.24     10049677.45
      2962043.56     10050486.31      2961091.43     10050944.97
       2960849.8     10052104.02       2961269.1     10053035.52
      2960975.76     10053433.71      2961131.65     10054426.99
      2960848.59     10055454.59      2961088.47     10056293.73
      2960788.22     10057536.91      2961275.67     10057980.18
      2960546.64     10058586.42      2960248.48     10059217.33
      2960096.43     10060987.94      2959591.61     10061431.18
      2959575.59     10062262.54      2958929.21     10064078.99
      2959377.63     10064654.16      2959283.12     10066326.52
      2960142.37     10066865.89      2960138.47     10067143.73

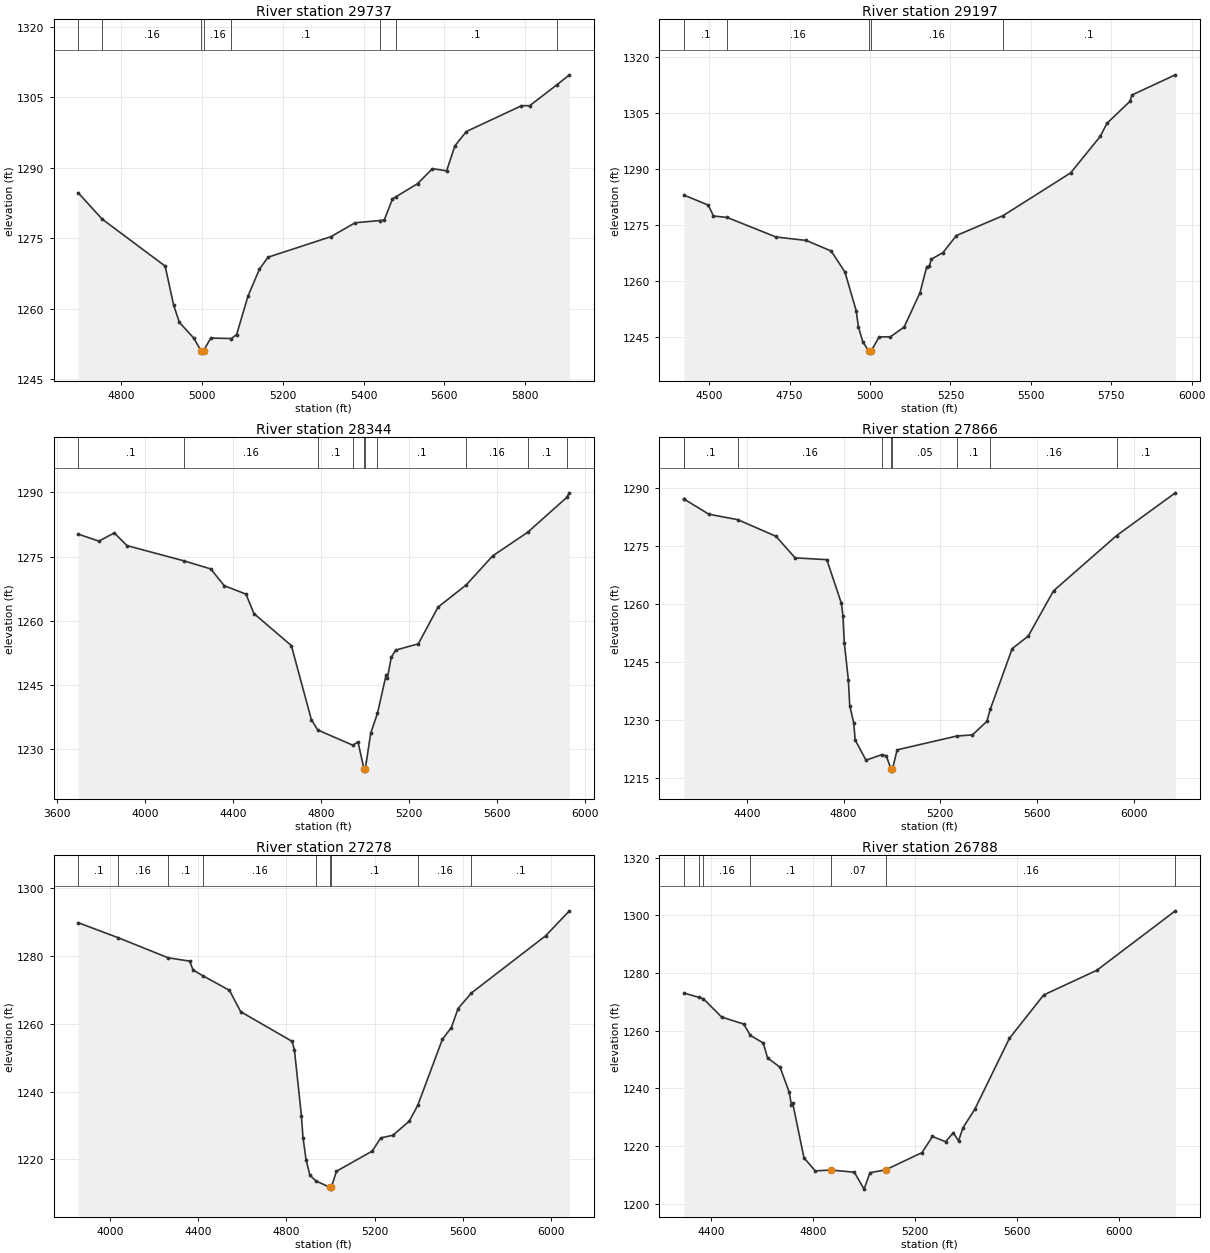
Type RM Length L Ch R = 1 ,29737   ,540,540,540
BEGIN DESCRIPTION:
CALOHAN CREEK 65.0
END DESCRIPTION:
XS GIS Cut Line= 4
      2965591.65     10043647.93      2965674.96     10043807.61
      2965942.33     10044085.39      2966573.88     10044238.07
#Sta/Elev= 30
  4693.9 1284.69  4753.4 1279.08  4909.2 1269.09  4930.3 1260.77  4944.5 1257.12
  4979.7 1253.82  4998.1 1251.09  5000.8 1250.59  5004.1 1251.09  5022.1  1253.8
    5073 1253.69    5086 1254.54  5114.3 1262.75  5142.6 1268.46  5163.6 1270.98
  5319.4 1275.35    5379  1278.3  5439.9 1278.77  5451.1 1278.86  5471.6 1283.37
  5479.6  1283.8  5533.8 1286.63  5570.5 1289.81  5605.4 1289.33    5626 1294.65
  5654.2 1297.69  5790.6 1303.18  5811.1  1303.2  5877.5 1307.58  5909.3 1309.75
#Mann= 8 ,-1 , 0
  4693.9      .1       0  4753.4     .16       0  4998.1     .07       0
  5004.1     .16       0    5073      .1       0  5439.9     .05       0
  5479.6      .1       0  5877.5     .05       0
Bank Sta=4998.1,5004.1
XS Rating Curve= 0 ,0
Exp/Cntr=0.3,0.1

Type RM Length L Ch R = 1 ,29197   ,853,853,853
BEGIN DESCRIPTION:
CALOHAN CREEK 64.0
END DESCRIPTION:
XS GIS Cut Line= 3
      2965299.96     10043748.63      2965272.19     10044144.42
      2966014.32     10044997.53
#Sta/Elev= 30
  4421.8 1283.03  4497.1 1280.36  4513.4 1277.44  4556.1 1277.04  4707.6 1271.81
  4801.6 1270.88  4879.4 1268.05  4922.1 1262.42  4957.2 1252.03  4963.9 1247.77
  4978.1  1243.6    4997 1241.18  4999.7 1240.68    5003 1241.18  5028.5 1245.02
  5063.6 1245.06  5106.3 1247.68  5155.7 1256.92  5176.5 1263.89  5184.2 1263.92
  5190.8 1265.85  5226.9 1267.63  5268.6 1272.19    5414 1277.54  5623.8 1288.99
  5715.9 1298.77  5736.8 1302.29    5808 1308.15  5814.6 1309.87  5949.3 1315.27
#Mann= 5 ,-1 , 0
  4421.8      .1       0  4556.1     .16       0    4997     .07       0
    5003     .16       0    5414      .1       0
Bank Sta=4997,5003
XS Rating Curve= 0 ,0
Exp/Cntr=0.3,0.1

Type RM Length L Ch R = 1 ,28344   ,478,478,478
BEGIN DESCRIPTION:
CALOHAN CREEK 62.0
END DESCRIPTION:
XS GIS Cut Line= 4
      2965320.79     10043470.82      2964952.74     10044311.08
      2964862.46     10044939.56      2965385.73     10045379.66
#Sta/Elev= 30
    3695 1280.25  3789.5  1278.6  3859.6 1280.52  3917.3 1277.56  4176.7    1274
  4298.6 1272.12    4360 1268.21    4459 1266.24  4495.1 1261.72  4665.5 1254.23
  4756.5 1236.96  4785.8 1234.54    4946 1230.98  4968.6  1231.8  4995.9 1225.45
  4998.7 1224.95  5001.9 1225.45  5026.7 1233.83  5057.4 1238.43  5097.2 1247.49
  5102.3 1246.59  5120.1 1251.48  5140.4 1253.19  5243.3 1254.64  5333.1 1263.22
    5461 1268.37  5581.5 1275.15  5740.8 1280.66  5918.4 1288.78    5931 1289.87
#Mann= 10 ,-1 , 0
    3695      .1       0  4176.7     .16       0  4785.8      .1       0
    4946     .05       0  4995.9    .035       0  5001.9     .05       0
  5057.4      .1       0    5461     .16       0  5740.8      .1       0
  5918.4     .16       0
Bank Sta=4995.9,5001.9
XS Rating Curve= 0 ,0
Exp/Cntr=0.3,0.1

Type RM Length L Ch R = 1 ,27866   ,588,588,588
BEGIN DESCRIPTION:
CALOHAN CREEK 61.0
END DESCRIPTION:
XS GIS Cut Line= 4
      2964011.78     10043977.76      2964327.74     10044488.17
      2964574.27     10044984.69      2965352.02     10045390.93
#Sta/Elev= 30
  4140.1 1287.08  4140.4 1287.06  4242.7 1283.16  4362.6 1281.74  4520.4 1277.46
  4599.6 1271.88  4730.8 1271.41  4791.3 1260.09  4797.5 1256.83  4803.1  1249.9
  4819.9 1240.34  4825.5 1233.73  4842.4 1229.13  4847.9 1224.86  4892.8 1219.61
  4958.7 1221.05  4976.8 1220.74  4996.2 1217.28    4999 1216.78  5002.2 1217.28
  5021.6 1222.28  5267.6 1225.84  5333.3 1226.15  5392.6 1229.63  5406.7 1232.73
  5497.4 1248.42  5563.6 1251.65  5668.4 1263.36  5929.4 1277.64  6172.2 1288.68
#Mann= 9 ,-1 , 0
  4140.1     .16       0  4140.4      .1       0  4362.6     .16       0
  4958.7     .05       0  4996.2    .035       0  5002.2     .05       0
  5267.6      .1       0  5406.7     .16       0  5929.4      .1       0
Bank Sta=4996.2,5002.2
XS Rating Curve= 0 ,0
Exp/Cntr=0.3,0.1

Type RM Length L Ch R = 1 ,27278   ,490,490,490
BEGIN DESCRIPTION:
CALOHAN CREEK 60.0
END DESCRIPTION:
XS GIS Cut Line= 4
      2963602.07     10044408.34      2964119.41     10045179.14
      2964661.08     10045363.17      2965374.96     10045491.39
#Sta/Elev= 30
  3856.6 1289.84  4039.2 1285.37  4264.5 1279.47  4362.2 1278.49  4377.2 1275.87
  4422.7 1274.14  4542.3 1269.87  4593.3 1263.56  4826.2 1254.81  4836.7 1252.21
  4868.4 1232.73  4875.3 1226.42  4889.5 1219.82  4906.7 1215.31  4934.4 1213.63
  4997.8 1211.72  5000.6 1211.22  5003.8 1211.72  5026.8 1216.49  5189.2 1222.45
  5227.5 1226.33  5283.3 1227.13    5357  1231.3  5395.1 1235.93  5506.7 1255.42
  5547.4 1258.89  5577.9  1264.5    5638 1269.08  5974.1 1285.94  6082.3 1293.33
#Mann= 9 ,-1 , 0
  3856.6      .1       0  4039.2     .16       0  4264.5      .1       0
  4422.7     .16       0  4934.4      .1       0  4997.8     .07       0
  5003.8      .1       0  5395.1     .16       0    5638      .1       0
Bank Sta=4997.8,5003.8
XS Rating Curve= 0 ,0
Exp/Cntr=0.3,0.1

Type RM Length L Ch R = 1 ,26788   ,759,759,759
BEGIN DESCRIPTION:
CALOHAN CREEK 59.0
END DESCRIPTION:
XS GIS Cut Line= 3
      2963483.98     10045818.03      2964372.88     10045627.06
      2965369.36     10045852.74
#Sta/Elev= 30
    4292  1273.1  4351.3 1271.59  4368.6  1271.1  4439.8 1264.78  4526.7 1262.35
  4552.7 1258.42  4603.4  1255.8  4620.3 1250.64  4669.7 1247.34  4705.7 1238.66
    4714 1234.38  4719.1 1234.94  4763.4 1215.99  4807.6 1211.43  4869.4 1211.72
  4961.4 1210.97  4999.7  1205.1  5022.8 1210.79  5084.2 1211.78  5227.4 1217.78
  5268.4 1223.36  5319.7 1221.55  5350.5 1224.64    5371 1221.82  5388.1 1226.35
  5435.1 1232.85  5570.9  1257.4  5705.5 1272.44  5914.4    1281  6222.9 1301.62
#Mann= 7 ,-1 , 0
    4292     .16       0  4351.3      .1       0  4368.6     .16       0
  4552.7      .1       0  4869.4     .07       0  5084.2     .16       0
  6222.9     .05       0
Bank Sta=4869.4,5084.2
XS Rating Curve= 0 ,0
Exp/Cntr=0.3,0.1

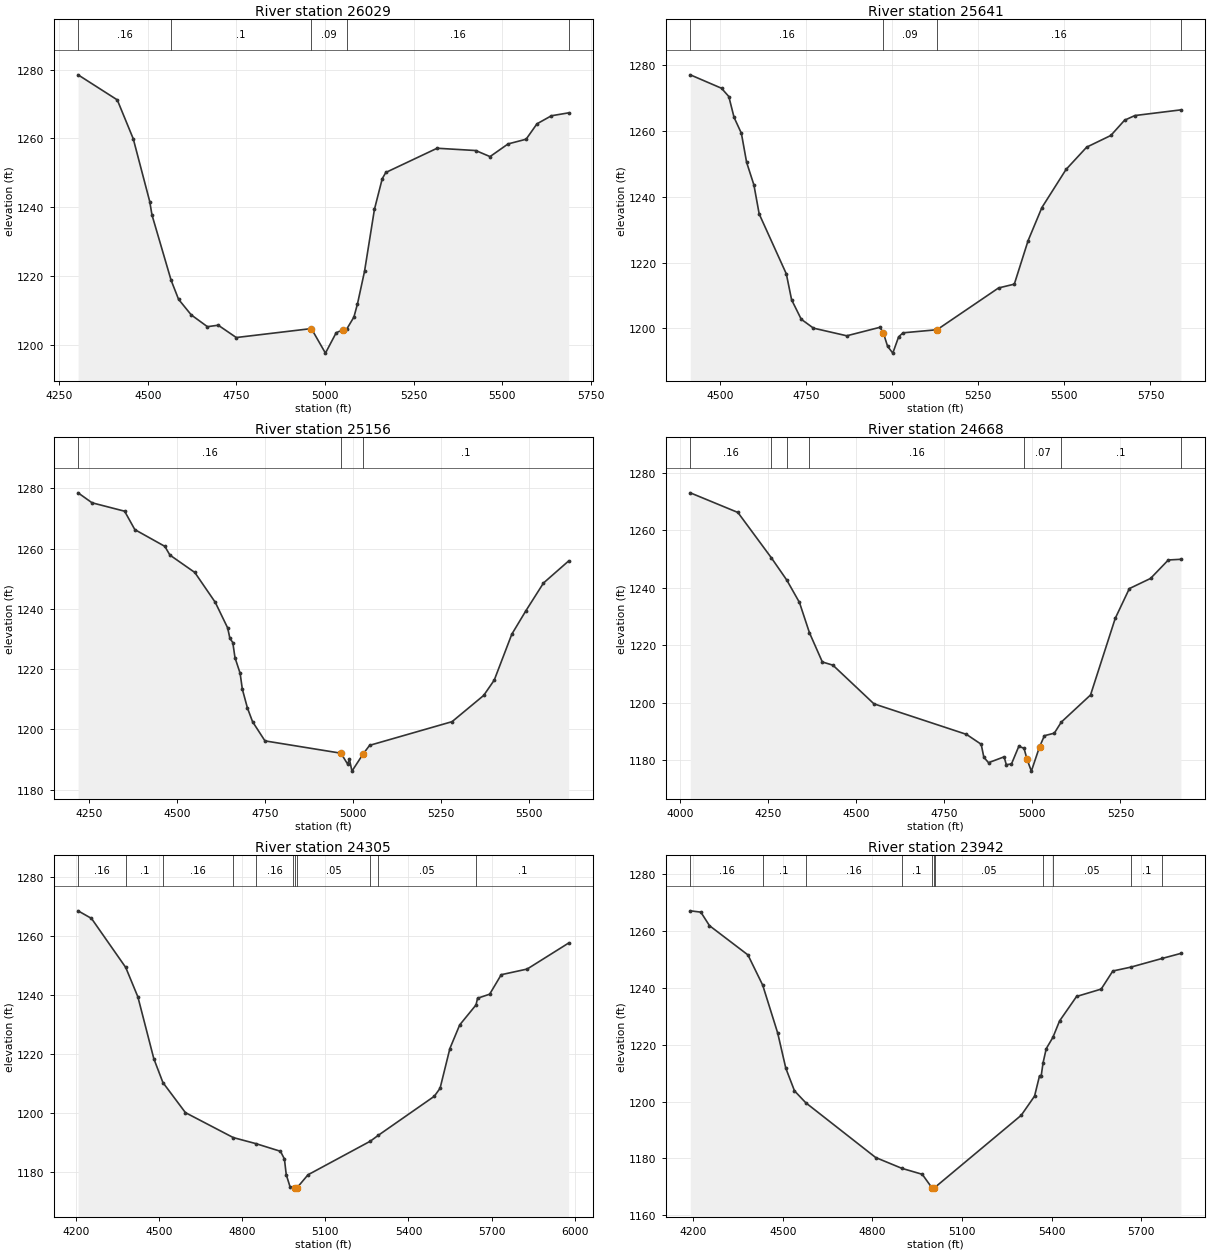
Type RM Length L Ch R = 1 ,26029   ,388,388,388
BEGIN DESCRIPTION:
CALOHAN CREEK 57.0
END DESCRIPTION:
XS GIS Cut Line= 4
      2963459.71     10046210.39      2964001.35     10046311.08
      2964393.71      10046321.5       2964826.3     10046238.44
#Sta/Elev= 30
  4303.2 1278.49  4413.8 1271.21  4458.9  1259.9  4505.4 1241.67  4511.7 1237.79
  4565.7 1218.81  4586.7 1213.29  4622.4 1208.77  4668.1 1205.34  4698.6 1205.77
  4749.5 1202.19  4961.3 1204.79    5001 1197.66  5031.3 1203.58  5051.3 1204.48
  5061.3 1204.69  5081.3 1208.13  5091.3 1211.93  5111.3 1221.43  5139.3 1239.46
  5161.3 1248.34  5171.3 1250.13    5316 1257.17    5425  1256.5  5465.3 1254.74
  5516.2 1258.42  5567.1 1259.79  5597.7 1264.26  5638.4  1266.6  5687.1 1267.45
#Mann= 5 ,-1 , 0
  4303.2     .16       0  4565.7      .1       0  4961.3     .09       0
  5061.3     .16       0  5687.1     .05       0
Bank Sta=4961.3,5051.3
XS Rating Curve= 0 ,0
Exp/Cntr=0.3,0.1

Type RM Length L Ch R = 1 ,25641   ,485,485,485
BEGIN DESCRIPTION:
CALOHAN CREEK 56.0
END DESCRIPTION:
XS GIS Cut Line= 4
      2963456.24     10046300.68      2963796.49     10046515.94
      2964265.24     10046752.06      2964761.75     10046769.42
#Sta/Elev= 30
    4414 1276.95  4504.6 1272.88  4525.8 1270.37  4541.1 1264.03  4562.3 1259.22
  4577.5 1250.41  4598.7 1243.54    4614 1234.74  4692.8 1216.56  4708.1 1208.71
  4736.1  1202.8  4771.6  1200.1  4868.3 1197.78  4964.4 1200.35  4974.2 1198.73
  4986.8  1194.6  5001.9 1192.52  5018.8 1197.45  5031.6 1198.68  5130.4 1199.62
  5308.9 1212.29  5354.7 1213.45  5394.7 1226.64  5434.8 1236.69  5504.8 1248.23
  5564.8 1255.01  5634.9 1258.55  5674.9 1263.19  5704.9  1264.6  5838.3 1266.32
#Mann= 4 ,-1 , 0
    4414     .16       0  4974.2     .09       0  5130.4     .16       0
  5838.3      .1       0
Bank Sta=4974.2,5130.4
XS Rating Curve= 0 ,0
Exp/Cntr=0.3,0.1

Type RM Length L Ch R = 1 ,25156   ,488,488,488
BEGIN DESCRIPTION:
CALOHAN CREEK 55.0
END DESCRIPTION:
XS GIS Cut Line= 4
      2963304.29     10046482.07      2963647.19     10046933.48
      2964107.26     10047089.73      2964450.09     10047098.41
#Sta/Elev= 30
  4218.2 1278.48    4258 1275.17  4350.6 1272.38  4379.7 1266.27    4465 1260.72
  4479.5 1257.82  4550.3 1252.05  4608.5 1242.14  4643.8 1233.63  4650.1  1230.2
  4658.4 1228.78  4664.6 1223.78  4679.2  1218.6  4685.5 1213.33    4700 1207.07
  4714.6 1202.52  4749.9 1196.15    4966 1192.06  4984.9 1188.47  4990.2 1190.04
  4997.4 1186.11  5029.3 1191.84  5047.7 1194.67  5282.2 1202.53  5372.2 1211.24
  5402.2 1216.32  5452.2 1231.57  5492.2 1239.33  5542.3 1248.55  5613.9 1255.87
#Mann= 3 ,-1 , 0
  4218.2     .16       0    4966     .07       0  5029.3      .1       0
Bank Sta=4966,5029.3
XS Rating Curve= 0 ,0
Exp/Cntr=0.3,0.1

Type RM Length L Ch R = 1 ,24668   ,363,363,363
BEGIN DESCRIPTION:
CALOHAN CREEK 54.0
END DESCRIPTION:
XS GIS Cut Line= 4
      2963087.29     10046929.14      2963742.67      10047324.1
      2963985.73     10047497.72      2964314.53     10047476.08
#Sta/Elev= 30
  4028.4 1272.98  4163.6 1266.15  4258.6 1250.39  4302.5 1242.63  4338.4 1234.87
  4366.8 1224.34  4403.4 1214.17  4433.5 1213.05    4550 1199.61  4812.8 1188.99
  4854.6 1185.55  4862.2 1181.02  4875.5 1179.14  4919.7 1181.18  4925.9 1178.46
  4940.6 1178.69  4961.5 1184.84  4976.3 1184.15  4984.9  1180.3  4997.1 1176.21
  5020.5 1184.71  5034.2 1188.53  5062.3 1189.41  5082.1 1193.25  5165.2 1202.69
  5235.3 1229.32  5275.4 1239.68  5335.6 1243.21  5386.1 1249.63  5421.8 1249.87
#Mann= 7 ,-1 , 0
  4028.4     .16       0  4258.6     .05       0  4302.5      .1       0
  4366.8     .16       0  4976.3     .07       0  5082.1      .1       0
  5421.8      .1       0
Bank Sta=4984.9,5020.5
XS Rating Curve= 0 ,0
Exp/Cntr=0.3,0.1

Type RM Length L Ch R = 1 ,24305   ,363,363,363
BEGIN DESCRIPTION:
CALOHAN CREEK 53.0
END DESCRIPTION:
XS GIS Cut Line= 4
      2963039.57     10047184.36      2963451.87     10047462.13
      2963881.56     10047961.26      2964253.02     10048449.34
#Sta/Elev= 30
  4208.6 1268.59  4256.9 1266.01  4380.5 1249.34  4424.3 1239.34  4481.7 1218.36
  4514.5 1210.24  4595.7 1200.01  4768.2 1191.53  4849.9 1189.47  4938.4 1186.87
  4952.7 1184.26  4959.3 1178.92  4973.5 1174.65  4985.3  1174.6  4992.5 1174.51
  4995.2 1174.01  4998.5 1174.51  5037.7 1178.88  5262.2 1190.29  5291.1 1192.29
  5493.1 1205.56    5514 1208.29  5549.4  1221.8  5584.8 1229.82  5643.6 1236.61
  5649.2 1238.88  5692.8 1240.26  5734.5 1246.88    5828  1248.8  5977.7 1257.65
#Mann= 11 ,-1 , 0
  4208.6     .16       0  4380.5      .1       0  4514.5     .16       0
  4768.2     .05       0  4849.9     .16       0  4985.3     .05       0
  4992.5    .035       0  4998.5     .05       0  5262.2      .1       0
  5291.1     .05       0  5643.6      .1       0
Bank Sta=4992.5,4998.5
XS Rating Curve= 0 ,0
Exp/Cntr=0.3,0.1

Type RM Length L Ch R = 1 ,23942   ,421,421,421
BEGIN DESCRIPTION:
CALOHAN CREEK 52.0
END DESCRIPTION:
XS GIS Cut Line= 3
      2962922.39     10047310.25      2963547.36     10048126.19
      2963824.31     10048675.76
#Sta/Elev= 30
  4189.9 1267.02  4225.2 1266.56  4254.2  1261.8    4383 1251.52  4432.4  1240.9
  4482.7 1224.05  4509.8 1211.71  4538.9 1203.75  4576.7 1199.56  4810.9 1180.31
  4898.5 1176.52  4966.8 1174.42  4999.1 1169.71  5001.9 1169.21  5005.1 1169.71
  5008.4 1169.75  5298.4 1195.17    5343  1201.9  5359.7 1209.06  5365.3 1209.07
  5371.4 1213.57  5382.1 1218.58  5404.5 1222.56  5426.7 1228.31  5483.7 1236.92
  5566.1 1239.51  5605.1 1245.87  5665.4 1247.23  5770.1 1250.28  5833.1 1252.06
#Mann= 11 ,-1 , 0
  4189.9     .16       0  4432.4      .1       0  4576.7     .16       0
  4898.5      .1       0  4999.1     .07       0  5005.1      .1       0
  5008.4     .05       0  5371.4      .1       0  5404.5     .05       0
  5665.4      .1       0  5770.1     .05       0
Bank Sta=4999.1,5005.1
XS Rating Curve= 0 ,0
Exp/Cntr=0.3,0.1

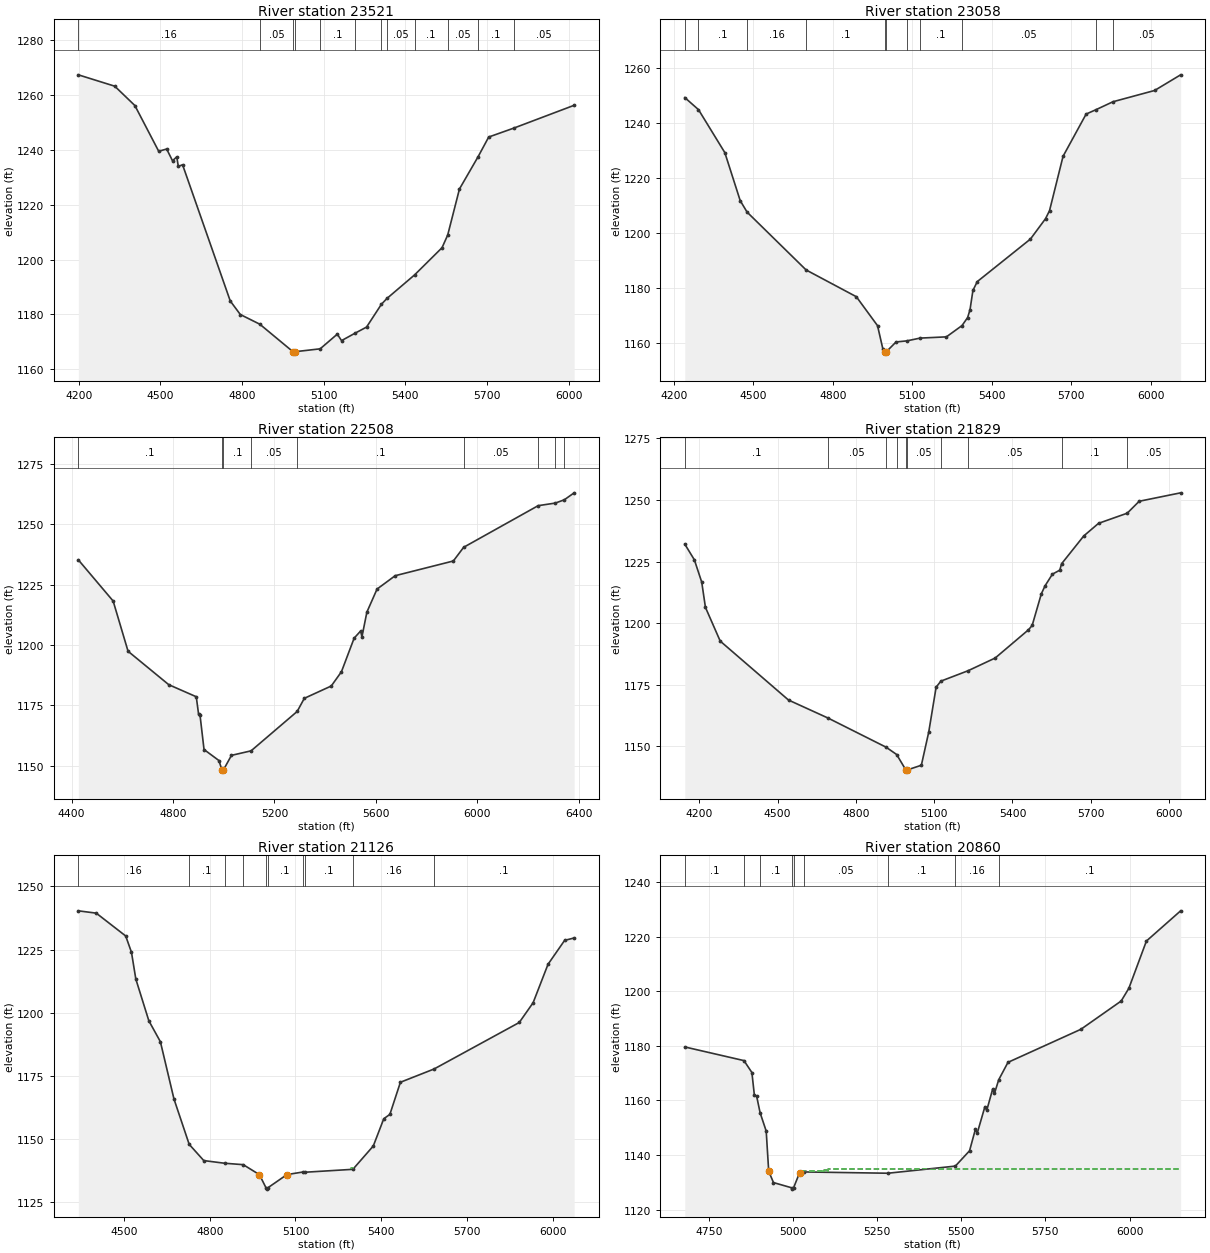
Type RM Length L Ch R = 1 ,23521   ,463,463,463
BEGIN DESCRIPTION:
CALOHAN CREEK 51.0
END DESCRIPTION:
XS GIS Cut Line= 3
      2962627.21     10047410.02      2963126.35     10048247.72
      2963790.45     10048772.91
#Sta/Elev= 30
  4198.7 1267.34  4332.5  1263.2  4406.5 1256.14    4494 1239.49  4523.3  1240.3
  4544.7 1236.02  4560.3 1237.45  4566.1 1233.96  4581.7 1234.57  4756.9 1184.93
  4793.9 1179.99  4865.5 1176.46  4987.6 1166.42  4990.3 1165.92  4993.6 1166.42
  5087.3 1167.49  5150.2 1172.84  5165.8 1170.48  5216.7 1173.25  5257.7 1175.41
  5312.4 1183.74  5332.8 1185.86  5434.1 1194.42    5535 1204.33  5555.8 1208.93
  5599.1 1225.75  5667.9 1237.56  5706.5 1244.67  5799.2 1247.94  6020.5 1256.24
#Mann= 12 ,-1 , 0
  4198.7     .16       0  4865.5     .05       0  4987.6    .035       0
  4993.6     .05       0  5087.3      .1       0  5216.7     .05       0
  5312.4      .1       0  5332.8     .05       0  5434.1      .1       0
  5555.8     .05       0  5667.9      .1       0  5799.2     .05       0
Bank Sta=4987.6,4993.6
XS Rating Curve= 0 ,0
Exp/Cntr=0.3,0.1

Type RM Length L Ch R = 1 ,23058   ,550,550,550
BEGIN DESCRIPTION:
CALOHAN CREEK 50.0
END DESCRIPTION:
XS GIS Cut Line= 4
      2962089.03     10048217.33      2962488.33     10048460.39
      2963126.35     10048469.07      2963763.92     10048894.11
#Sta/Elev= 30
  4241.3 1249.13    4293 1244.75  4392.4 1229.17  4450.5 1211.74  4476.5 1207.58
  4699.2 1186.61  4888.9  1176.9  4968.9  1166.4  4988.9    1158  4995.9 1156.94
  4998.7 1156.44  5001.9 1156.94  5038.9 1160.49  5079.2 1160.88  5129.5 1161.89
  5228.9 1162.34  5287.9 1166.44    5309 1169.34    5318 1172.17    5329 1179.17
  5345.4 1182.38  5546.1 1197.81  5603.2 1205.22  5618.2 1208.11  5669.3 1227.84
  5756.4 1243.15  5793.6 1244.74  5857.8 1247.62  6014.8  1251.7  6113.1 1257.38
#Mann= 11 ,-1 , 0
  4241.3     .16       0    4293      .1       0  4476.5     .16       0
  4699.2      .1       0  4995.9     .07       0  5001.9      .1       0
  5079.2     .05       0  5129.5      .1       0  5287.9     .05       0
  5793.6      .1       0  5857.8     .05       0
Bank Sta=4995.9,5001.9
XS Rating Curve= 0 ,0
Exp/Cntr=0.3,0.1

Type RM Length L Ch R = 1 ,22508   ,679,679,679
BEGIN DESCRIPTION:
CALOHAN CREEK 49.0
END DESCRIPTION:
XS GIS Cut Line= 3
       2962106.4     10048668.73        2962905.     10049133.13
      2963933.53     10049055.02
#Sta/Elev= 30
  4426.6  1235.2  4563.9 1218.17  4622.7 1197.41  4783.2 1183.59  4891.7  1178.6
  4900.8  1171.4  4906.5 1170.99  4922.3 1156.78    4981 1152.23  4992.8 1148.35
  4995.6 1147.85  4998.8 1148.35  5030.5 1154.37  5107.9 1156.24  5289.5 1172.51
  5317.8 1177.95  5424.1 1183.05  5464.2 1188.94  5514.3 1202.84    5540  1205.8
    5545 1203.36  5564.5 1213.59  5604.6 1223.12  5676.2 1228.65  5905.5 1234.73
  5946.1 1240.39  6239.9  1257.6    6308 1258.68  6343.2 1260.04  6381.9 1262.91
#Mann= 9 ,-1 , 0
  4426.6      .1       0  4992.8     .07       0  4998.8      .1       0
  5107.9     .05       0  5289.5      .1       0  5946.1     .05       0
  6239.9      .1       0    6308     .05       0  6343.2      .1       0
Bank Sta=4992.8,4998.8
XS Rating Curve= 0 ,0
Exp/Cntr=0.3,0.1

Type RM Length L Ch R = 1 ,21829   ,703,703,703
BEGIN DESCRIPTION:
CALOHAN CREEK 47.0
END DESCRIPTION:
XS GIS Cut Line= 2
      2962006.53     10048963.83      2963377.95     10050278.83
#Sta/Elev= 30
  4144.4 1232.07    4181 1225.72  4209.3 1216.63  4223.5 1206.39  4280.1  1192.7
  4541.8 1168.76  4693.6 1161.43  4915.6 1149.62  4956.2 1146.64  4991.3 1140.39
  4994.1 1139.89  4997.3 1140.39  5050.9 1142.28  5079.2 1155.77  5107.5 1173.99
  5125.8 1176.44  5229.9 1180.66  5333.9 1185.83  5461.3 1197.28  5475.5 1199.05
  5510.7 1211.92  5524.8 1215.13  5553.1 1219.88  5581.4 1221.51  5588.1 1224.08
  5673.3 1235.41  5729.9 1240.52  5839.8 1244.64  5885.6 1249.48  6044.4 1252.91
#Mann= 10 ,-1 , 0
  4144.4      .1       0  4693.6     .05       0  4915.6      .1       0
  4956.2     .05       0  4991.3    .035       0  4997.3     .05       0
  5125.8      .1       0  5229.9     .05       0  5588.1      .1       0
  5839.8     .05       0
Bank Sta=4991.3,4997.3
XS Rating Curve= 0 ,0
Exp/Cntr=0.3,0.1

Type RM Length L Ch R = 1 ,21126   ,266,266,266
BEGIN DESCRIPTION:
CALOHAN CREEK 46.0
END DESCRIPTION:
XS GIS Cut Line= 4
      2961893.71     10048989.86      2961963.16     10049454.31
      2961984.86     10049771.15      2962792.19     10050265.97
#Sta/Elev= 30
  4340.5 1240.37  4403.2 1239.45  4506.2 1230.41  4526.4 1223.94  4541.6 1213.35
  4587.1 1196.85  4627.5 1188.56    4675 1165.88  4728.2 1147.94  4779.2 1141.51
  4851.8 1140.46  4917.3 1139.89 4973.86 1135.94    4997 1130.71  4999.7 1130.21
    5003 1130.71  5070.1 1135.97  5124.7 1136.96  5133.7  1136.9  5300.7 1138.05
  5372.1 1147.29  5408.8 1158.08  5430.1  1159.8  5466.9 1172.51  5584.8 1177.77
  5882.6 1196.17  5931.1    1204  5983.2 1219.21  6041.3 1228.68  6074.6 1229.62
#Mann= 10 ,-1 , 0
  4340.5     .16       0  4728.2      .1       0  4851.8     .05       0
  4917.3      .1       0    4997     .07       0    5003      .1       0
  5124.7     .05       0  5133.7      .1       0  5300.7     .16       0
  5584.8      .1       0
#XS Ineff= 3 ,-1
 5176.94 5230.96  1136.8  5271.4 5284.48 1137.58  5293.6 5305.44 1138.43
Permanent Ineff=
       T       T       T
Bank Sta=4973.86,5070.1
XS Rating Curve= 0 ,0
Exp/Cntr=0.3,0.1

Type RM Length L Ch R = 1 ,20860   ,356,356,356
BEGIN DESCRIPTION:
CALOHAN CREEK 45.0
END DESCRIPTION:
XS GIS Cut Line= 3
      2961533.48     10049536.78       2961945.8     10049918.72
      2962770.47     10050305.02
#Sta/Elev= 30
  4678.9 1179.56  4854.6 1174.56  4878.2  1170.2  4885.6 1161.84  4892.4 1161.47
  4902.6 1155.45  4920.7 1148.74  4928.1 1134.03  4942.3 1129.89    4996 1127.99
  4998.7 1127.49    5002 1127.99  5019.9  1133.5    5032 1133.79  5282.1 1133.31
  5482.5 1135.92  5524.7 1141.54    5542 1149.39  5547.5    1148  5570.3 1157.69
  5575.8 1156.36  5593.2 1164.08  5598.7 1162.52  5611.2 1167.52  5638.8 1173.92
  5855.3 1186.02    5975 1196.38  5997.8 1201.03    6050 1218.35  6151.6 1229.41
#Mann= 9 ,-1 , 0
  4678.9      .1       0  4854.6     .16       0  4902.6      .1       0
    4996     .07       0    5002      .1       0    5032     .05       0
  5282.1      .1       0  5482.5     .16       0  5611.2      .1       0
#XS Ineff= 3 ,-1
  5026.5 5088.38 1133.96 5090.94 5101.78 1134.56 5104.34  6151.6  1134.9
Permanent Ineff=
       T       T       T
Bank Sta=4928.1,5019.9
XS Rating Curve= 0 ,0
Exp/Cntr=0.3,0.1

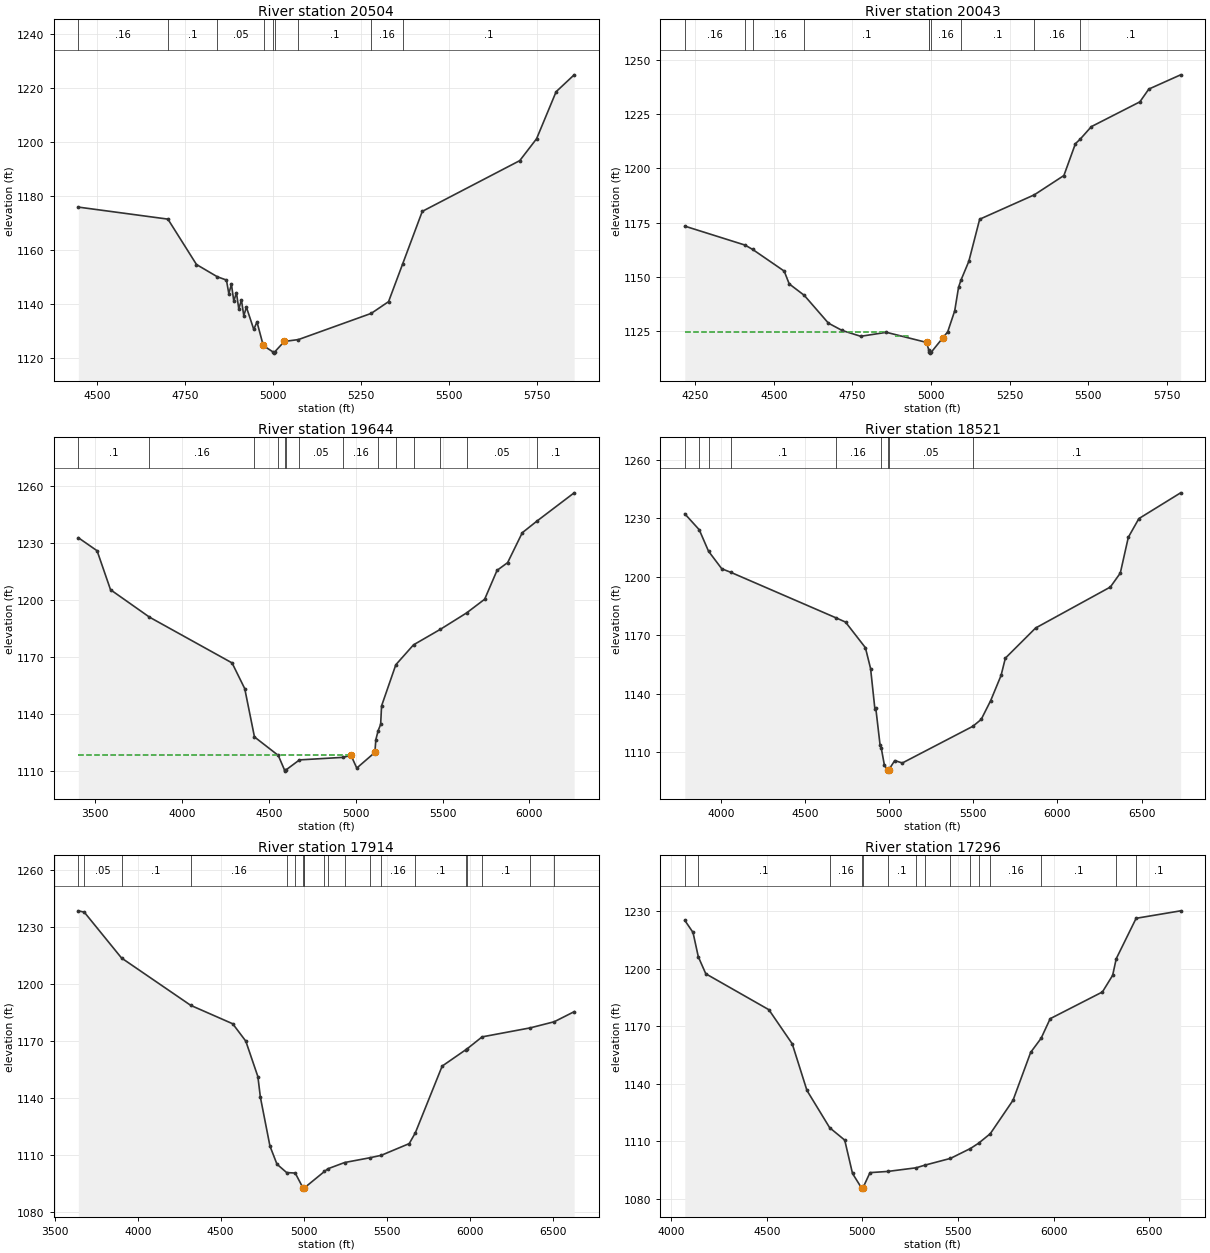
Type RM Length L Ch R = 1 ,20504   ,461,461,461
BEGIN DESCRIPTION:
Mapping XS 525c2f8d
END DESCRIPTION:
XS GIS Cut Line= 4
      2961519.32     10049678.22      2961857.88     10050053.24
      2961970.73     10050051.51      2962713.62     10050325.75
#Sta/Elev= 30
  4445.8 1175.91  4700.5 1171.47  4781.8  1154.7  4841.2 1150.16    4867 1148.96
  4873.7 1143.97  4881.2 1147.38  4887.9 1141.17  4895.4 1144.29  4902.1 1138.28
  4909.6 1141.63  4916.3  1135.8  4923.8 1138.93  4944.7 1130.73  4953.8 1133.49
  4971.6 1124.83  4972.6 1124.69  4998.6 1122.46  5001.4 1121.96  5004.6 1122.46
  5031.6 1126.28  5071.7 1126.97  5278.8 1136.65    5328 1140.98  5367.7 1154.78
  5423.9 1174.33  5701.1 1193.08    5749 1201.18  5804.5 1218.54  5855.8 1224.78
#Mann= 9 ,-1 , 0
  4445.8     .16       0  4700.5      .1       0  4841.2     .05       0
  4972.6     .16       0  4998.6     .07       0  5004.6     .16       0
  5071.7      .1       0  5278.8     .16       0  5367.7      .1       0
Bank Sta=4971.6,5031.6
XS Rating Curve= 0 ,0
Exp/Cntr=0.3,0.1

Type RM Length L Ch R = 1 ,20043   ,399,399,399
BEGIN DESCRIPTION:
CALOHAN CREEK 43.0
END DESCRIPTION:
XS GIS Cut Line= 4
      2961589.91     10049862.32      2961863.33     10050352.75
      2962306.04      10050574.1      2962818.17     10050660.91
#Sta/Elev= 30
  4217.2 1173.34  4408.7  1164.6  4433.2 1162.57  4533.1 1152.62  4549.1 1146.71
  4596.9 1141.44  4673.7 1128.62  4717.1 1125.26  4776.4 1122.57  4858.1  1124.4
  4985.7 1119.74  4992.2 1116.47  4994.9 1115.31  4997.6 1114.81  5000.9 1115.31
    5037  1121.8  5052.8 1124.63  5075.1 1134.31  5087.3 1145.17  5094.8 1148.38
  5119.9 1157.11  5154.4 1176.52  5327.9 1187.75  5422.1 1196.66  5458.7 1211.33
  5474.2 1213.47  5509.4  1219.2  5663.5 1230.61    5692  1236.5  5793.1 1243.07
#Mann= 10 ,-1 , 0
  4217.2     .16       0  4408.7      .1       0  4433.2     .16       0
  4596.9      .1       0  4992.2     .16       0  4994.9     .07       0
  5000.9     .16       0  5094.8      .1       0  5327.9     .16       0
  5474.2      .1       0
#XS Ineff= 2 ,-1
  4217.2 4857.86 1124.46 4885.95 4925.11 1122.56
Permanent Ineff=
       T       T
Bank Sta=4985.7,5037
XS Rating Curve= 0 ,0
Exp/Cntr=0.3,0.1

Type RM Length L Ch R = 1 ,19644   ,1123,1123,1123
BEGIN DESCRIPTION:
CALOHAN CREEK 42.0
END DESCRIPTION:
XS GIS Cut Line= 2
      2960201.01     10050157.44      2962934.46     10050977.47
#Sta/Elev= 30
  3403.8 1232.93  3511.7 1226.06  3589.1  1205.5  3813.4 1191.04  4288.6 1166.91
  4361.6 1153.34  4417.6 1127.88  4554.5 1118.14    4591 1110.35  4593.8 1109.85
    4597 1110.35  4676.6 1115.77  4926.1 1117.11  4973.4 1118.12  5006.4 1111.46
  5110.8 1119.73  5116.1 1126.44  5129.5 1131.19  5143.9 1134.53  5149.1 1144.24
  5231.2 1165.95    5333 1176.44    5488 1184.65  5638.1 1193.25  5742.5 1200.49
  5813.8 1215.72  5874.7 1219.79    5959 1235.56  6044.9 1241.81  6257.6  1256.6
#Mann= 14 ,-1 , 0
  3403.8      .1       0  3813.4     .16       0  4417.6      .1       0
  4554.5     .16       0    4591     .07       0    4597     .16       0
  4676.6     .05       0  4926.1     .16       0  5129.5      .1       0
  5231.2     .16       0    5333      .1       0    5488     .16       0
  5638.1     .05       0  6044.9      .1       0
#XS Ineff= 2 , 0
         4972.51 1118.12
Permanent Ineff=
       T       T
Bank Sta=4973.4,5110.8
XS Rating Curve= 0 ,0
Exp/Cntr=0.3,0.1

Type RM Length L Ch R = 1 ,18521   ,607,607,607
BEGIN DESCRIPTION:
CALOHAN CREEK 40.0
END DESCRIPTION:
XS GIS Cut Line= 4
      2959897.18     10051016.81      2960817.33     10051151.36
      2962023.92     10051581.05      2962755.49     10051645.98
#Sta/Elev= 30
  3786.8 1232.34  3872.6 1224.16  3927.8 1213.13  4006.4 1204.12  4058.9 1202.34
  4682.1 1179.02  4741.6 1176.73  4859.6 1163.58  4890.4 1152.85  4915.9 1132.15
  4921.2 1132.57  4946.8 1113.53  4953.3 1112.25  4972.3  1103.3  4990.9 1100.67
  4993.7 1100.17  4996.9 1100.67  5033.9  1105.6  5078.9 1104.35  5497.7 1123.19
  5547.4 1126.73  5603.7 1136.39  5665.4 1149.32  5690.9  1158.2  5870.6 1173.69
  6314.5 1194.73  6373.6 1201.89  6421.3 1220.29    6484 1229.89    6732 1243.13
#Mann= 9 ,-1 , 0
  3786.8     .05       0  3872.6      .1       0  3927.8     .05       0
  4058.9      .1       0  4682.1     .16       0  4953.3     .05       0
  4990.9    .035       0  4996.9     .05       0  5497.7      .1       0
Bank Sta=4990.9,4996.9
XS Rating Curve= 0 ,0
Exp/Cntr=0.3,0.1

Type RM Length L Ch R = 1 ,17914   ,618,618,618
BEGIN DESCRIPTION:
CALOHAN CREEK 38.0
END DESCRIPTION:
XS GIS Cut Line= 4
      2959819.06     10051160.04      2960552.57     10051528.97
      2961416.28     10052080.18      2962510.05     10052410.05
#Sta/Elev= 30
  3642.2 1238.44    3678 1237.74  3902.5 1213.63  4319.7 1188.71  4572.7 1179.02
  4651.4  1169.9  4724.2 1151.24  4739.4 1140.36    4797  1114.7  4839.3 1105.16
  4897.8 1100.74  4949.3  1100.5    4997 1092.54  4999.8 1092.04    5003 1092.54
    5004 1092.67  5125.7 1101.36  5145.1 1102.71  5246.7 1106.03  5397.3 1108.51
  5467.6 1109.82  5636.4 1115.99  5673.3 1121.69  5834.8 1156.76  5978.5 1165.44
    5983 1165.69  6075.5 1172.13  6365.7 1176.87  6510.5  1180.1  6630.3 1185.38
#Mann= 20 ,-1 , 0
  3642.2      .1       0    3678     .05       0  3902.5      .1       0
  4319.7     .16       0  4897.8      .1       0  4949.3     .16       0
    4997     .07       0    5003     .16       0    5004      .1       0
  5125.7     .05       0  5145.1      .1       0  5246.7     .05       0
  5397.3      .1       0  5467.6     .16       0  5673.3      .1       0
  5978.5     .05       0    5983     .16       0  6075.5      .1       0
  6365.7     .05       0  6510.5      .1       0
Bank Sta=4997,5003
XS Rating Curve= 0 ,0
Exp/Cntr=0.3,0.1

Type RM Length L Ch R = 1 ,17296   ,996,996,996
BEGIN DESCRIPTION:
CALOHAN CREEK 37.0
END DESCRIPTION:
XS GIS Cut Line= 4
      2960031.69     10052318.89      2960565.59     10052444.76
      2961290.42     10052314.56      2962510.07     10052783.32
#Sta/Elev= 30
  4071.7 1225.37  4114.6 1219.07  4142.4 1206.34  4181.4  1197.5  4511.1 1178.75
  4633.3 1160.94  4710.2 1136.61    4829 1117.16  4907.6  1110.7  4948.3  1093.3
  4996.1 1085.62  4998.8 1085.12  5002.1 1085.62  5039.7 1093.73  5133.2 1094.36
  5280.7 1096.25  5326.9 1097.64  5460.3 1101.16  5564.3  1106.3    5607 1109.06
  5668.3 1114.03  5787.4 1131.51  5879.5 1156.49    5934 1163.82  5981.4 1174.06
  6254.5 1188.01    6308  1196.7  6326.7 1205.35  6430.7 1226.45  6663.3 1230.35
#Mann= 15 ,-1 , 0
  4071.7     .05       0  4142.4      .1       0    4829     .16       0
  4996.1     .07       0  5002.1     .16       0  5133.2      .1       0
  5280.7     .05       0  5326.9      .1       0  5460.3     .05       0
  5564.3     .16       0    5607     .05       0  5668.3     .16       0
    5934      .1       0  6326.7     .05       0  6430.7      .1       0
Bank Sta=4996.1,5002.1
XS Rating Curve= 0 ,0
Exp/Cntr=0.3,0.1