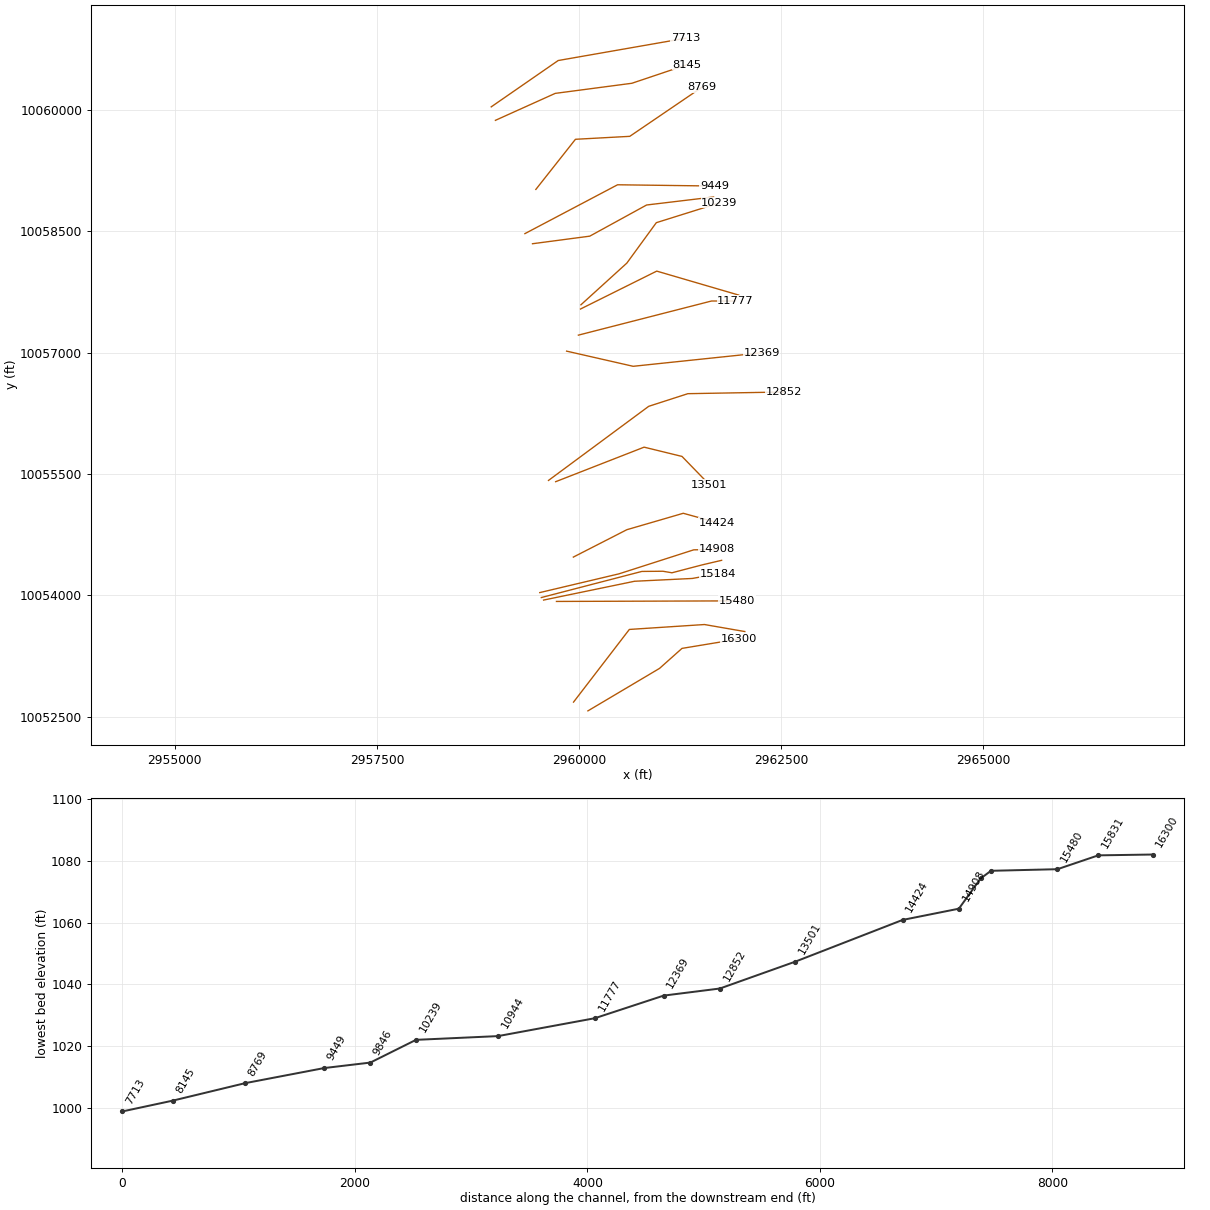
HEC-RAS study CALOHAN CREEK.prj: CALOHAN CREEK Base Level Engineering

--- CALOHAN CREEK.g01 (geometry) --- (continued)

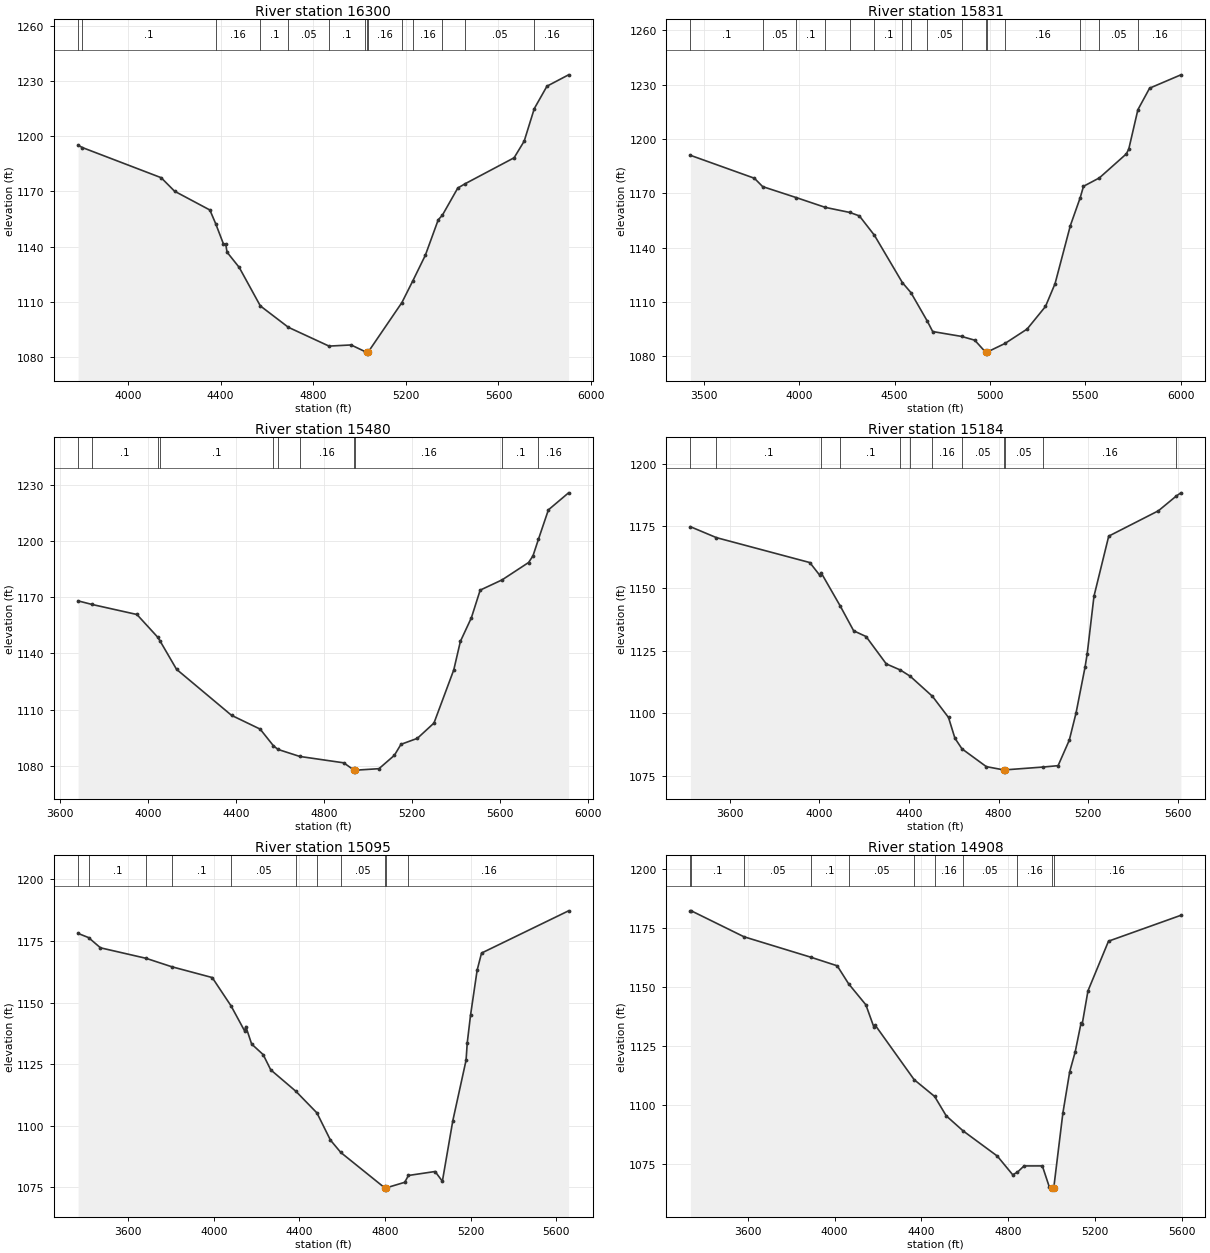
Type RM Length L Ch R = 1 ,16300   ,469,469,469
BEGIN DESCRIPTION:
CALOHAN CREEK 35.0
END DESCRIPTION:
XS GIS Cut Line= 4
      2960109.88     10052570.64      2960995.28     10053095.81
      2961273.06      10053343.2      2961980.51     10053460.39
#Sta/Elev= 30
  3784.4 1195.15  3802.6 1193.89  4143.2 1177.48  4201.3 1170.12  4353.7  1159.9
  4378.7 1152.48  4412.2 1141.47    4422 1141.45  4427.8 1136.97  4480.4 1128.68
  4571.6 1107.74  4692.6 1096.11  4868.3 1085.87  4963.6  1086.5  5024.1 1082.87
  5030.9 1082.55  5033.6 1082.05  5036.9 1082.55    5183 1109.55  5230.8 1121.52
  5284.2 1135.26  5340.1 1154.62  5357.6 1157.02  5424.4 1171.85  5456.9 1174.24
  5667.7 1188.31  5711.2 1197.36  5754.9 1215.08  5809.6 1227.25  5902.9 1233.43
#Mann= 14 ,-1 , 0
  3784.4     .05       0  3802.6      .1       0  4378.7     .16       0
  4571.6      .1       0  4692.6     .05       0  4868.3      .1       0
  5024.1     .16       0  5030.9     .07       0  5036.9     .16       0
    5183      .1       0  5230.8     .16       0  5357.6      .1       0
  5456.9     .05       0  5754.9     .16       0
Bank Sta=5030.9,5036.9
XS Rating Curve= 0 ,0
Exp/Cntr=0.3,0.1

Type RM Length L Ch R = 1 ,15831   ,351,351,351
BEGIN DESCRIPTION:
CALOHAN CREEK 34.0
END DESCRIPTION:
XS GIS Cut Line= 4
      2959931.89     10052679.11      2960622.01     10053577.58
      2961550.83     10053638.34      2962050.01     10053551.53
#Sta/Elev= 30
  3430.3 1190.94  3765.7 1178.28    3809 1173.66  3984.3 1167.63  4137.7 1162.19
  4266.3 1159.39  4315.9 1157.49  4394.5 1146.84  4541.3 1120.67  4585.7 1115.22
  4671.9 1099.42    4700 1093.69  4851.3    1091  4920.4 1088.92  4977.6 1082.28
  4980.3 1081.78  4983.6 1082.28  5078.7  1087.1  5194.8 1095.06  5291.2 1107.54
  5341.3 1120.12  5421.5 1152.16  5473.1 1167.54  5490.3 1173.83  5573.5 1178.47
  5714.9 1191.72  5727.7 1194.43  5775.3 1216.08  5836.7 1227.97  6000.7 1235.34
#Mann= 16 ,-1 , 0
  3430.3      .1       0    3809     .05       0  3984.3      .1       0
  4137.7     .16       0  4266.3     .05       0  4394.5      .1       0
  4541.3     .05       0  4585.7      .1       0  4671.9     .05       0
  4851.3      .1       0  4977.6     .07       0  4983.6      .1       0
  5078.7     .16       0  5473.1      .1       0  5573.5     .05       0
  5775.3     .16       0
Bank Sta=4977.6,4983.6
XS Rating Curve= 0 ,0
Exp/Cntr=0.3,0.1

Type RM Length L Ch R = 1 ,15480   ,572,572,572
BEGIN DESCRIPTION:
CALOHAN CREEK 33.0
END DESCRIPTION:
XS GIS Cut Line= 2
      2959720.95     10053923.93      2961950.14     10053930.88
#Sta/Elev= 30
    3682 1168.05  3745.8 1166.13  3949.5 1160.79    4043 1148.81  4053.4 1146.92
  4129.5 1131.58  4379.5 1107.04  4509.5  1099.7  4570.1 1090.78  4590.7 1088.87
  4689.4 1085.13  4889.5 1081.72  4936.5  1077.8  4939.3  1077.3  4942.5  1077.8
  5049.5  1078.6  5119.5 1085.72  5149.5 1091.58  5223.9 1094.77  5299.5 1102.93
  5389.5 1131.28  5419.5 1146.44  5469.5 1159.05  5509.5 1173.78  5608.9 1179.23
  5729.5  1188.5  5749.5 1192.05  5774.5 1200.97  5819.5 1216.56  5911.2 1225.64
#Mann= 11 ,-1 , 0
    3682     .16       0  3745.8      .1       0    4043     .05       0
  4053.4      .1       0  4570.1     .05       0  4590.7      .1       0
  4689.4     .16       0  4936.5     .07       0  4942.5     .16       0
  5608.9      .1       0  5774.5     .16       0
Bank Sta=4936.5,4942.5
XS Rating Curve= 0 ,0
Exp/Cntr=0.3,0.1

Type RM Length L Ch R = 1 ,15184   ,89,89,89
BEGIN DESCRIPTION:
CALOHAN CREEK 67.0
END DESCRIPTION:
XS GIS Cut Line= 4
      2959561.37     10053940.78      2960686.32     10054173.41
       2961401.6     10054208.13      2961721.02     10054267.15
#Sta/Elev= 30
  3423.8 1174.69  3540.1 1170.31  3956.9 1160.33    4002 1155.16    4007 1156.32
  4092.8 1142.92  4152.7 1132.99    4208  1130.7  4298.2 1119.74  4361.2 1117.28
  4404.7 1114.82  4504.6 1106.73  4576.1 1098.27  4604.7 1089.97  4636.2 1085.71
  4744.9 1078.58    4822 1077.28  4824.7 1076.78    4828 1077.28  4998.4 1078.42
  5065.3 1078.97  5115.3 1089.18  5145.4 1100.05  5185.4 1118.32  5195.4 1123.85
  5225.5 1146.84  5291.3 1170.91  5513.2 1181.07  5592.8 1186.97  5613.5 1188.26
#Mann= 12 ,-1 , 0
  3423.8     .16       0  3540.1      .1       0    4007     .05       0
  4092.8      .1       0  4361.2     .05       0  4404.7      .1       0
  4504.6     .16       0  4636.2     .05       0    4822     .07       0
    4828     .05       0  4998.4     .16       0  5592.8      .1       0
Bank Sta=4822,4828
XS Rating Curve= 0 ,0
Exp/Cntr=0.3,0.1

Type RM Length L Ch R = 1 ,15095   ,187,187,187
BEGIN DESCRIPTION:
CALOHAN CREEK 66.0
END DESCRIPTION:
XS GIS Cut Line= 6
      2959533.51     10053972.01       2960776.6     10054294.93
      2961037.71     10054297.25      2961148.82     10054278.15
      2961523.82     10054376.24      2961763.32     10054432.31
#Sta/Elev= 30
  3366.1 1178.04  3414.9 1176.35  3470.9 1172.19  3683.6 1167.94  3803.2 1164.53
  3992.9 1160.13    4081 1148.62  4144.7 1138.41  4149.9 1140.26  4177.1 1133.15
    4231 1128.86  4266.4 1122.68  4383.5 1114.01  4482.3  1105.2  4545.1  1094.2
  4593.7 1089.16  4799.3 1074.79  4802.1 1074.29  4805.3 1074.79  4892.3 1077.06
  4909.7 1079.83  5034.3 1081.44  5068.3 1077.48    5117 1102.03    5179 1126.59
  5184.4 1133.57  5199.7 1144.76  5230.7 1163.12  5251.3 1170.06  5657.9  1187.2
#Mann= 11 ,-1 , 0
  3366.1     .16       0  3414.9      .1       0  3683.6     .05       0
  3803.2      .1       0    4081     .05       0  4383.5      .1       0
  4482.3     .16       0  4593.7     .05       0  4799.3     .07       0
  4805.3     .05       0  4909.7     .16       0
Bank Sta=4799.3,4805.3
XS Rating Curve= 0 ,0
Exp/Cntr=0.3,0.1

Type RM Length L Ch R = 1 ,14908   ,484,484,484
BEGIN DESCRIPTION:
CALOHAN CREEK 32.0
END DESCRIPTION:
XS GIS Cut Line= 4
      2959514.36      10054033.3      2960493.54     10054265.08
      2961418.02     10054561.95      2961699.26     10054567.16
#Sta/Elev= 30
  3336.2  1182.2  3340.3  1182.2    3583 1171.23  3890.3  1162.6  4012.3 1158.95
  4064.8 1151.34  4144.2 1142.46  4181.3 1132.99  4186.4 1133.95  4366.4 1110.82
  4460.9 1103.71  4514.2 1095.51  4592.2 1089.13  4749.4  1078.5  4820.2 1070.61
  4841.5 1071.63  4872.6 1074.33  4956.8 1074.34  4988.3 1065.59  5003.3 1065.02
    5006 1064.52  5009.3 1065.02  5051.3 1096.68  5082.8 1114.17  5107.9 1122.52
  5134.7  1134.6    5140 1134.14  5166.8 1148.34  5261.4 1169.37  5594.7 1180.31
#Mann= 11 ,-1 , 0
  3336.2     .05       0  3340.3      .1       0    3583     .05       0
  3890.3      .1       0  4064.8     .05       0  4366.4      .1       0
  4460.9     .16       0  4592.2     .05       0  4841.5     .16       0
  5003.3     .07       0  5009.3     .16       0
Bank Sta=5003.3,5009.3
XS Rating Curve= 0 ,0
Exp/Cntr=0.3,0.1

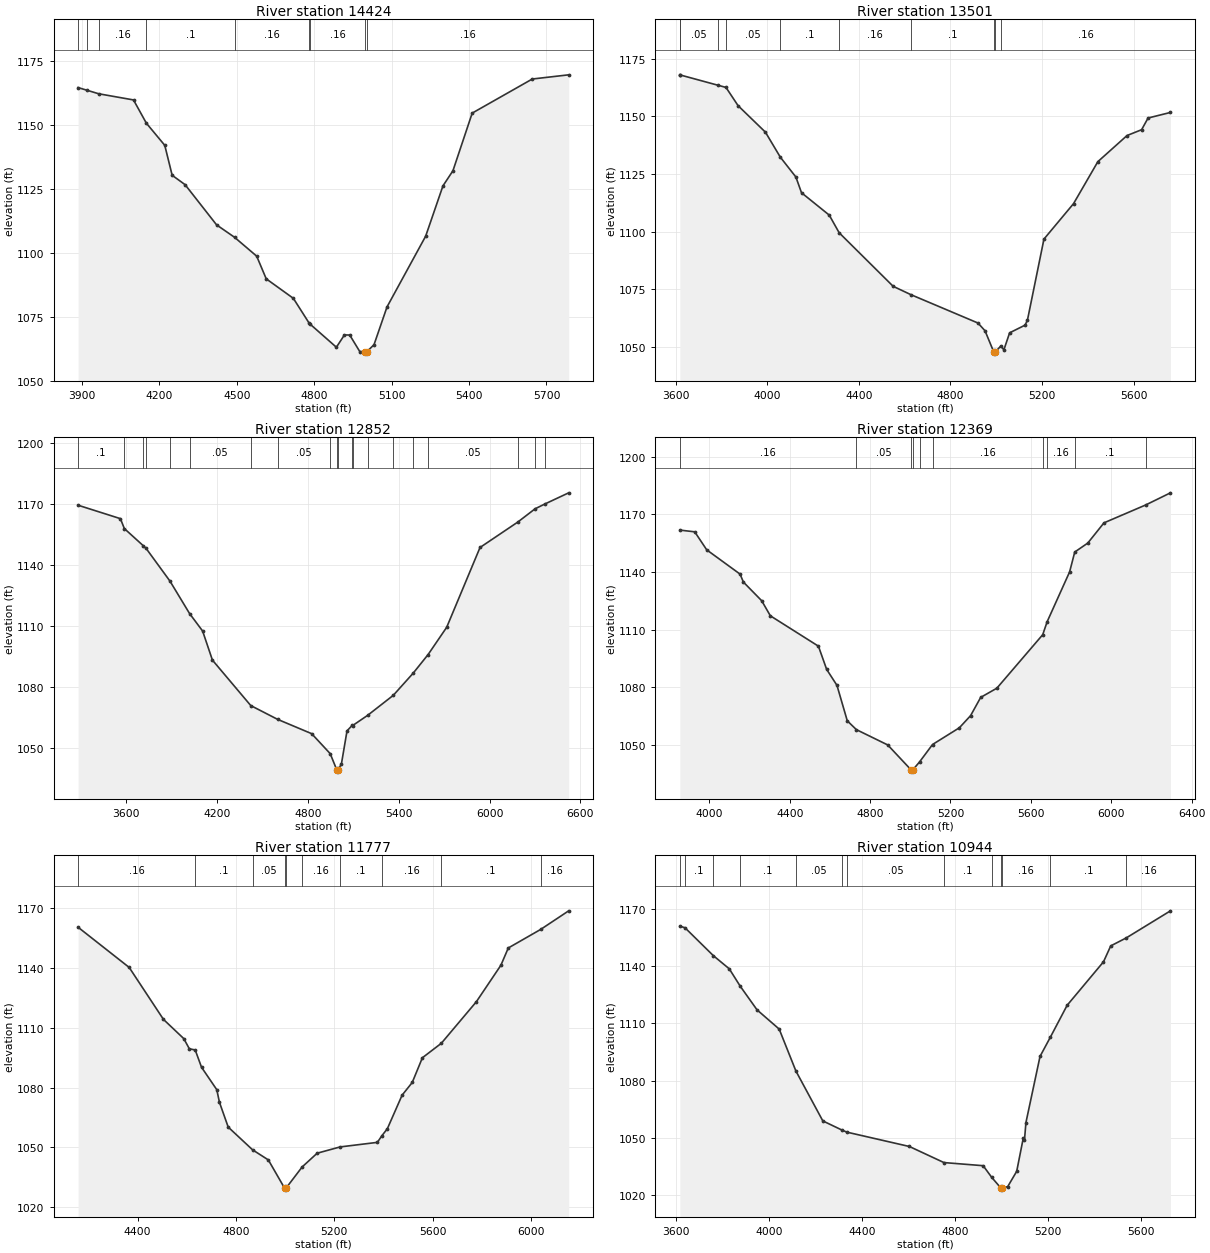
Type RM Length L Ch R = 1 ,14424   ,923,923,923
BEGIN DESCRIPTION:
CALOHAN CREEK 31.0
END DESCRIPTION:
XS GIS Cut Line= 4
      2959929.48      10054472.3      2960590.98     10054810.87
       2961288.9     10055013.99      2961704.49      10054899.7
#Sta/Elev= 30
  3885.2 1164.73  3921.7 1163.63  3965.2 1162.31    4100  1159.9  4149.8 1150.81
  4221.1 1142.15  4249.8 1130.43  4299.9 1126.76  4421.9 1111.04  4491.4 1106.19
  4577.3  1098.8  4614.2 1089.94  4719.4  1082.3    4780 1072.69  4783.2 1072.31
  4886.1 1063.18  4917.3 1068.01  4937.8 1067.95  4976.6 1061.51  4997.6 1061.38
  5000.4 1060.88  5003.6 1061.38  5031.9 1064.18  5082.3 1078.96    5232 1106.62
    5299 1126.29  5337.7 1132.21  5412.3 1154.75  5645.1 1168.08  5786.2 1169.72
#Mann= 9 ,-1 , 0
  3885.2     .16       0  3921.7      .1       0  3965.2     .16       0
  4149.8      .1       0  4491.4     .16       0    4780      .1       0
  4783.2     .16       0  4997.6     .07       0  5003.6     .16       0
Bank Sta=4997.6,5003.6
XS Rating Curve= 0 ,0
Exp/Cntr=0.3,0.1

Type RM Length L Ch R = 1 ,13501   ,649,649,649
BEGIN DESCRIPTION:
CALOHAN CREEK 29.0
END DESCRIPTION:
XS GIS Cut Line= 4
      2959710.77     10055404.62      2960804.52      10055831.7
      2961273.27     10055717.12      2961611.52     10055368.46
#Sta/Elev= 30
  3618.7    1168  3619.2 1167.97  3786.1 1163.46  3820.2 1162.54    3873 1154.63
  3992.4 1143.15  4057.4 1132.32  4125.5  1123.7    4150 1116.89  4271.1  1107.2
  4314.4 1099.55  4550.2 1076.34    4627 1072.75  4920.5 1060.43  4951.4 1057.07
  4989.5 1047.88  4992.3 1047.38  4995.5 1047.88  5020.7 1050.47  5033.7  1048.8
  5058.8 1056.18  5126.4 1059.52  5136.7 1061.72  5208.7 1096.81    5338 1112.18
  5444.2 1130.38  5571.5 1141.69  5635.1 1144.21  5663.4 1149.28  5761.2  1151.7
#Mann= 10 ,-1 , 0
  3618.7      .1       0  3619.2     .05       0  3786.1      .1       0
  3820.2     .05       0  4057.4      .1       0  4314.4     .16       0
    4627      .1       0  4989.5     .07       0  4995.5      .1       0
  5020.7     .16       0
Bank Sta=4989.5,4995.5
XS Rating Curve= 0 ,0
Exp/Cntr=0.3,0.1

Type RM Length L Ch R = 1 ,12852   ,483,483,483
BEGIN DESCRIPTION:
CALOHAN CREEK 28.0
END DESCRIPTION:
XS GIS Cut Line= 4
      2959622.21     10055420.23      2960861.81     10056336.91
      2961346.19     10056493.16      2962533.53     10056513.99
#Sta/Elev= 30
  3284.1 1169.37  3563.4 1162.77  3589.6 1157.89  3713.1 1149.55  3733.6  1148.1
  3890.5 1132.08  4019.9 1116.14  4106.1 1107.54  4170.8 1093.25  4423.9  1070.9
    4601 1064.13  4825.8 1057.09  4948.2 1047.27  4992.2 1039.18  4994.9 1038.68
  4998.2 1039.18  5021.9 1042.08  5059.2 1058.47  5092.7 1061.12  5096.1 1061.07
    5195 1066.08  5364.5 1075.93  5495.8 1086.82  5594.4 1095.98  5717.1 1109.38
  5937.1  1148.6    6186 1161.07  6300.2  1167.6  6368.4 1170.09  6522.3 1175.46
#Mann= 20 ,-1 , 0
  3284.1      .1       0  3589.6     .05       0  3713.1      .1       0
  3733.6     .16       0  3890.5      .1       0  4019.9     .05       0
  4423.9      .1       0    4601     .05       0  4948.2      .1       0
  4992.2     .07       0  4998.2      .1       0  5092.7     .05       0
  5096.1      .1       0    5195     .16       0  5364.5      .1       0
  5495.8     .16       0  5594.4     .05       0    6186      .1       0
  6300.2     .05       0  6368.4      .1       0
Bank Sta=4992.2,4998.2
XS Rating Curve= 0 ,0
Exp/Cntr=0.3,0.1

Type RM Length L Ch R = 1 ,12369   ,592,592,592
BEGIN DESCRIPTION:
CALOHAN CREEK 26.0
END DESCRIPTION:
XS GIS Cut Line= 3
      2959846.22     10057019.19      2960669.11      10056831.7
      2962257.61     10056998.36
#Sta/Elev= 30
  3853.4 1161.78  3927.5 1160.87  3987.2 1151.49  4153.1 1138.87  4169.5 1134.75
  4260.7 1125.02  4303.7 1117.19  4542.9 1101.39  4583.9 1089.31  4635.2    1081
  4686.5 1062.56  4731.9 1057.97  4887.8 1050.01  5005.4 1036.89  5008.2 1036.39
  5011.4 1036.89  5046.3 1041.21  5110.7 1050.24  5244.3 1058.95    5300 1065.24
  5350.3 1074.75  5430.7 1079.53    5659 1107.37  5680.9 1114.09  5792.7 1140.02
  5818.3 1150.36  5883.2 1155.03  5963.7 1165.54  6170.8 1174.82  6294.6 1181.16
#Mann= 10 ,-1 , 0
  3853.4     .16       0  4731.9     .05       0  5005.4    .035       0
  5011.4     .05       0  5046.3      .1       0  5110.7     .16       0
    5659      .1       0  5680.9     .16       0  5818.3      .1       0
  6170.8     .05       0
Bank Sta=5005.4,5011.4
XS Rating Curve= 0 ,0
Exp/Cntr=0.3,0.1

Type RM Length L Ch R = 1 ,11777   ,833,833,833
BEGIN DESCRIPTION:
CALOHAN CREEK 25.0
END DESCRIPTION:
XS GIS Cut Line= 3
      2959992.05     10057217.12      2961637.86     10057638.99
      2961934.14     10057638.99
#Sta/Elev= 30
  4158.1 1160.45    4366 1140.28  4505.4 1114.21    4588 1104.57  4610.7 1099.46
  4634.5 1098.88  4660.2  1090.2  4722.2 1078.96    4733 1072.66  4768.7 1060.18
    4868 1048.77  4931.8 1043.73  4997.9 1029.57  5000.7 1029.07  5003.9 1029.57
  5069.5 1040.21  5130.5 1047.09  5223.8 1050.24  5375.3 1052.53    5393 1055.74
    5416  1059.4  5475.8 1076.19  5517.1 1082.57  5558.4 1094.97  5635.5 1102.24
  5777.9 1123.08  5877.7 1141.39  5907.7 1150.04  6039.4 1159.35  6153.4 1168.68
#Mann= 10 ,-1 , 0
  4158.1     .16       0  4634.5      .1       0    4868     .05       0
  4997.9    .035       0  5003.9     .05       0  5069.5     .16       0
  5223.8      .1       0    5393     .16       0  5635.5      .1       0
  6039.4     .16       0
Bank Sta=4997.9,5003.9
XS Rating Curve= 0 ,0
Exp/Cntr=0.3,0.1

Type RM Length L Ch R = 1 ,10944   ,705,705,705
BEGIN DESCRIPTION:
CALOHAN CREEK 24.0
END DESCRIPTION:
XS GIS Cut Line= 3
      2960018.08     10057540.04      2960960.77     10058008.78
      2961974.94     10057712.33
#Sta/Elev= 30
  3616.9 1160.92  3639.1 1160.06  3760.9 1145.47  3829.5 1138.57  3876.2 1129.53
  3948.8  1117.1    4044 1107.04  4115.9 1085.09  4231.6 1058.98  4312.6 1054.27
  4334.4 1053.12  4603.9 1045.59  4752.3 1037.18    4921 1035.54  4957.9 1029.41
  4997.7 1023.78  5000.4 1023.28  5003.7 1023.78  5026.5 1024.59  5065.2  1032.6
  5093.4 1049.97  5098.6 1048.96  5104.9 1058.14  5165.5 1092.75  5209.6 1102.73
    5282 1119.49  5438.3 1142.24  5469.5 1150.58  5536.7 1154.79  5726.3 1168.93
#Mann= 13 ,-1 , 0
  3616.9     .16       0  3639.1      .1       0  3760.9     .16       0
  3876.2      .1       0  4115.9     .05       0  4312.6      .1       0
  4334.4     .05       0  4752.3      .1       0  4957.9     .16       0
  4997.7     .07       0  5003.7     .16       0  5209.6      .1       0
  5536.7     .16       0
Bank Sta=4997.7,5003.7
XS Rating Curve= 0 ,0
Exp/Cntr=0.3,0.1

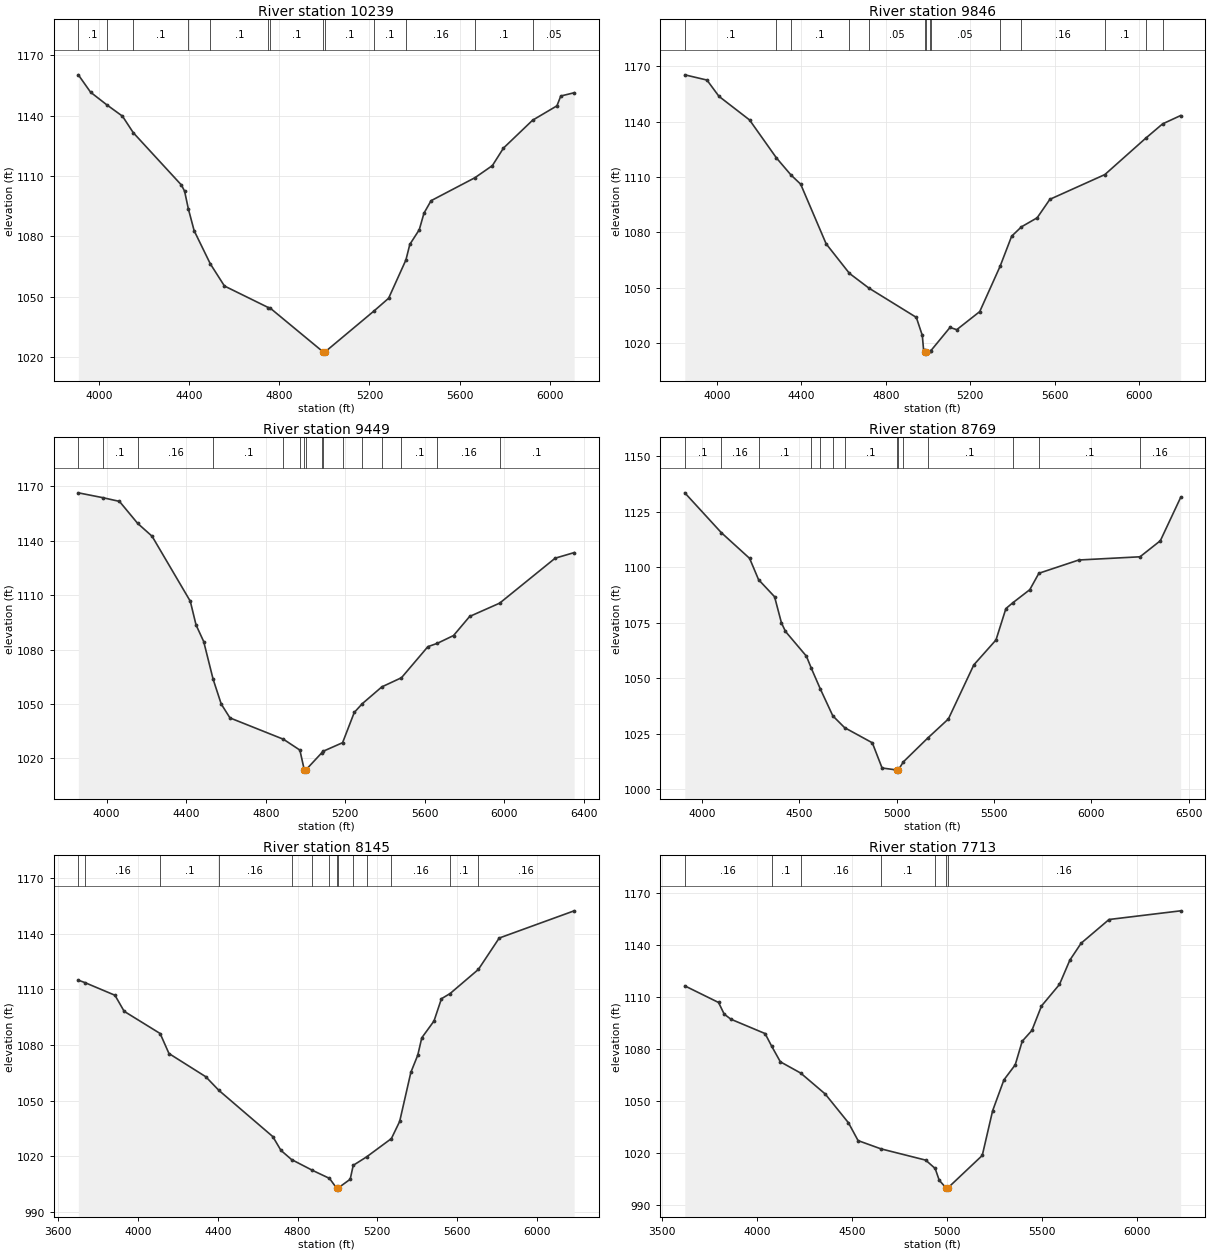
Type RM Length L Ch R = 1 ,10239   ,393,393,393
BEGIN DESCRIPTION:
CALOHAN CREEK 22.0
END DESCRIPTION:
XS GIS Cut Line= 4
      2960023.24     10057592.09      2960590.98     10058107.74
      2960955.56     10058607.74      2961735.12       10058852.
#Sta/Elev= 30
  3906.6 1160.25    3961 1151.62  4032.1 1145.44  4102.8 1139.71  4150.8  1131.5
  4364.5 1105.54  4378.6 1102.51  4395.5 1093.63  4421.2 1082.83  4492.9 1066.41
  4555.7  1055.4  4750.4 1044.71  4759.3 1044.39  4995.4 1022.57  4998.2 1022.07
  5001.4 1022.57  5219.8 1042.97    5285 1049.31  5361.9 1068.33  5379.2 1076.06
  5421.2 1083.34  5442.1 1091.56  5473.6 1097.75  5668.1 1109.14    5746 1115.18
  5795.3 1123.88  5924.6 1137.71  6032.8 1144.86  6049.9 1149.73  6109.3 1151.35
#Mann= 13 ,-1 , 0
  3906.6      .1       0  4032.1     .16       0  4150.8      .1       0
  4395.5     .05       0  4492.9      .1       0  4750.4     .05       0
  4759.3      .1       0  4995.4     .07       0  5001.4      .1       0
  5219.8      .1       0  5361.9     .16       0  5668.1      .1       0
  5924.6     .05       0
Bank Sta=4995.4,5001.4
XS Rating Curve= 0 ,0
Exp/Cntr=0.3,0.1

Type RM Length L Ch R = 1 ,9846    ,397,397,397
BEGIN DESCRIPTION:
CALOHAN CREEK 21.0
END DESCRIPTION:
XS GIS Cut Line= 4
      2959424.34     10058347.33      2960132.65     10058441.07
      2960835.77     10058826.49      2961663.67     10058925.42
#Sta/Elev= 30
  3847.6 1165.29  3952.6 1162.46  4009.4 1153.67  4154.4 1140.89  4282.2 1120.29
  4351.1 1111.07  4396.7 1106.14  4517.5 1073.86    4628 1057.85  4720.7 1049.86
    4945 1034.05  4973.4 1024.27  4979.3 1016.57  4986.5 1015.21  4989.3 1014.71
  4992.5 1015.21  5011.3  1015.7  5012.2 1015.79  5104.7 1028.62  5136.5 1027.39
  5245.5 1037.18  5342.1 1061.71  5396.8 1077.98  5443.2 1083.04  5517.7 1087.93
  5578.1 1097.94  5838.6 1111.32  6031.5 1130.92  6112.1 1138.74  6197.7 1143.26
#Mann= 14 ,-1 , 0
  3847.6      .1       0  4282.2     .16       0  4351.1      .1       0
    4628     .16       0  4720.7     .05       0  4986.5    .035       0
  4992.5     .05       0  5011.3      .1       0  5012.2     .05       0
  5342.1      .1       0  5443.2     .16       0  5838.6      .1       0
  6031.5     .05       0  6112.1      .1       0
Bank Sta=4986.5,4992.5
XS Rating Curve= 0 ,0
Exp/Cntr=0.3,0.1

Type RM Length L Ch R = 1 ,9449    ,680,680,680
BEGIN DESCRIPTION:
CALOHAN CREEK 20.0
END DESCRIPTION:
XS GIS Cut Line= 3
      2959330.58     10058472.33       2960476.4     10059076.49
      2961673.85     10059060.87
#Sta/Elev= 30
  3857.8 1166.43  3979.5 1163.79  4064.5 1161.71  4156.2 1149.57  4228.5  1142.5
  4420.7 1106.64  4449.7 1093.54  4488.1 1084.41  4535.3  1063.7  4576.2 1049.96
  4620.2 1042.29  4889.2 1030.51  4971.7 1024.54  4994.2 1013.44    4997 1012.94
  5000.2 1013.44  5080.8 1022.94  5087.4 1023.83  5186.4 1028.62  5245.2 1045.32
  5285.1  1050.1  5383.8 1059.41  5482.6 1064.46  5615.3 1081.59  5662.4 1083.41
  5744.2 1087.71  5825.3 1098.25  5976.2 1105.59  6255.3 1130.39  6350.7 1133.46
#Mann= 16 ,-1 , 0
  3857.8     .16       0  3979.5      .1       0  4156.2     .16       0
  4535.3      .1       0  4889.2     .16       0  4971.7     .05       0
  4994.2    .035       0  5000.2     .05       0  5080.8      .1       0
  5087.4     .16       0  5186.4     .05       0  5285.1      .1       0
  5383.8     .05       0  5482.6      .1       0  5662.4     .16       0
  5976.2      .1       0
Bank Sta=4994.2,5000.2
XS Rating Curve= 0 ,0
Exp/Cntr=0.3,0.1

Type RM Length L Ch R = 1 ,8769    ,624,624,624
BEGIN DESCRIPTION:
CALOHAN CREEK 19.0
END DESCRIPTION:
XS GIS Cut Line= 4
      2959465.96     10059019.17      2959955.56     10059638.99
      2960627.44     10059675.45      2961523.29     10060284.84
#Sta/Elev= 30
  3912.2 1133.53  4099.3 1115.61    4245 1103.98    4291 1094.38  4373.2 1086.68
  4408.5 1074.89  4429.3 1071.03  4536.7 1059.88    4562 1054.42  4607.4 1045.25
  4672.3 1032.97  4732.9 1027.65  4875.2 1020.82  4925.3 1009.46  5002.4 1008.55
  5005.2 1008.05  5008.4 1008.55  5034.6 1012.23  5158.8 1022.88  5265.8 1031.57
  5396.4 1055.95  5510.2 1067.19  5561.1 1081.34  5596.2 1083.93  5683.8 1089.86
  5730.5 1097.26  5935.2 1103.24  6249.9 1104.69  6354.2 1111.92  6458.4 1131.43
#Mann= 14 ,-1 , 0
  3912.2      .1       0  4099.3     .16       0    4291      .1       0
    4562     .16       0  4607.4      .1       0  4672.3     .16       0
  4732.9      .1       0  5002.4     .07       0  5008.4      .1       0
  5034.6     .05       0  5158.8      .1       0  5596.2     .16       0
  5730.5      .1       0  6249.9     .16       0
Bank Sta=5002.4,5008.4
XS Rating Curve= 0 ,0
Exp/Cntr=0.3,0.1

Type RM Length L Ch R = 1 ,8145    ,432,432,432
BEGIN DESCRIPTION:
CALOHAN CREEK 17.0
END DESCRIPTION:
XS GIS Cut Line= 4
      2958965.99     10059873.37      2959705.56      10060206.7
      2960653.48      10060331.7      2961334.64     10060560.49
#Sta/Elev= 30
  3700.8 1114.94  3732.8 1113.68  3884.4 1106.82  3930.6 1098.17  4110.9 1086.21
  4155.3 1075.42  4339.7 1062.93  4405.3  1055.6  4675.9 1030.67  4716.7 1023.25
  4769.7 1018.32  4874.6  1012.5  4959.9 1008.17  4996.1 1002.88  4998.9 1002.38
  5002.1 1002.88  5063.8  1007.7    5079 1015.19    5146 1019.75  5270.3  1029.6
  5311.8 1038.83  5368.1 1065.33  5402.6 1074.56  5422.7 1083.89    5484 1092.95
  5521.3 1104.95  5564.7 1107.74  5706.5 1120.73    5811 1137.64  6186.7  1152.3
#Mann= 14 ,-1 , 0
  3700.8      .1       0  3732.8     .16       0  4110.9      .1       0
  4405.3     .16       0  4769.7      .1       0  4874.6     .16       0
  4959.9      .1       0  4996.1     .07       0  5002.1      .1       0
    5079     .16       0    5146      .1       0  5270.3     .16       0
  5564.7      .1       0  5706.5     .16       0
Bank Sta=4996.1,5002.1
XS Rating Curve= 0 ,0
Exp/Cntr=0.3,0.1

Type RM Length L Ch R = 1 ,7713    ,440,440,440
BEGIN DESCRIPTION:
CALOHAN CREEK 16.0
END DESCRIPTION:
XS GIS Cut Line= 3
      2958913.92     10060040.05      2959742.02     10060612.95
      2961319.41     10060888.86
#Sta/Elev= 30
  3619.9 1116.27  3797.6 1106.67  3827.3 1099.92  3863.1 1096.98  4042.2 1088.73
  4077.5 1081.31  4122.6 1072.42  4229.5 1065.92  4358.5 1053.84  4480.8 1037.21
  4531.5 1026.92  4651.3 1022.17  4887.2 1015.64  4936.9 1010.83  4958.3 1004.03
  4995.9   999.4  4998.6   998.9  5001.9   999.4  5184.7 1018.34  5239.1 1044.12
  5298.6 1061.98  5358.1 1070.67  5394.8 1084.29  5445.6 1090.51  5496.3 1104.66
  5590.9  1117.1  5645.3  1131.1  5704.8  1140.9  5851.6 1154.59  6228.2  1159.6
#Mann= 7 ,-1 , 0
  3619.9     .16       0  4077.5      .1       0  4229.5     .16       0
  4651.3      .1       0  4936.9     .16       0  4995.9     .07       0
  5001.9     .16       0
Bank Sta=4995.9,5001.9
XS Rating Curve= 0 ,0
Exp/Cntr=0.3,0.1