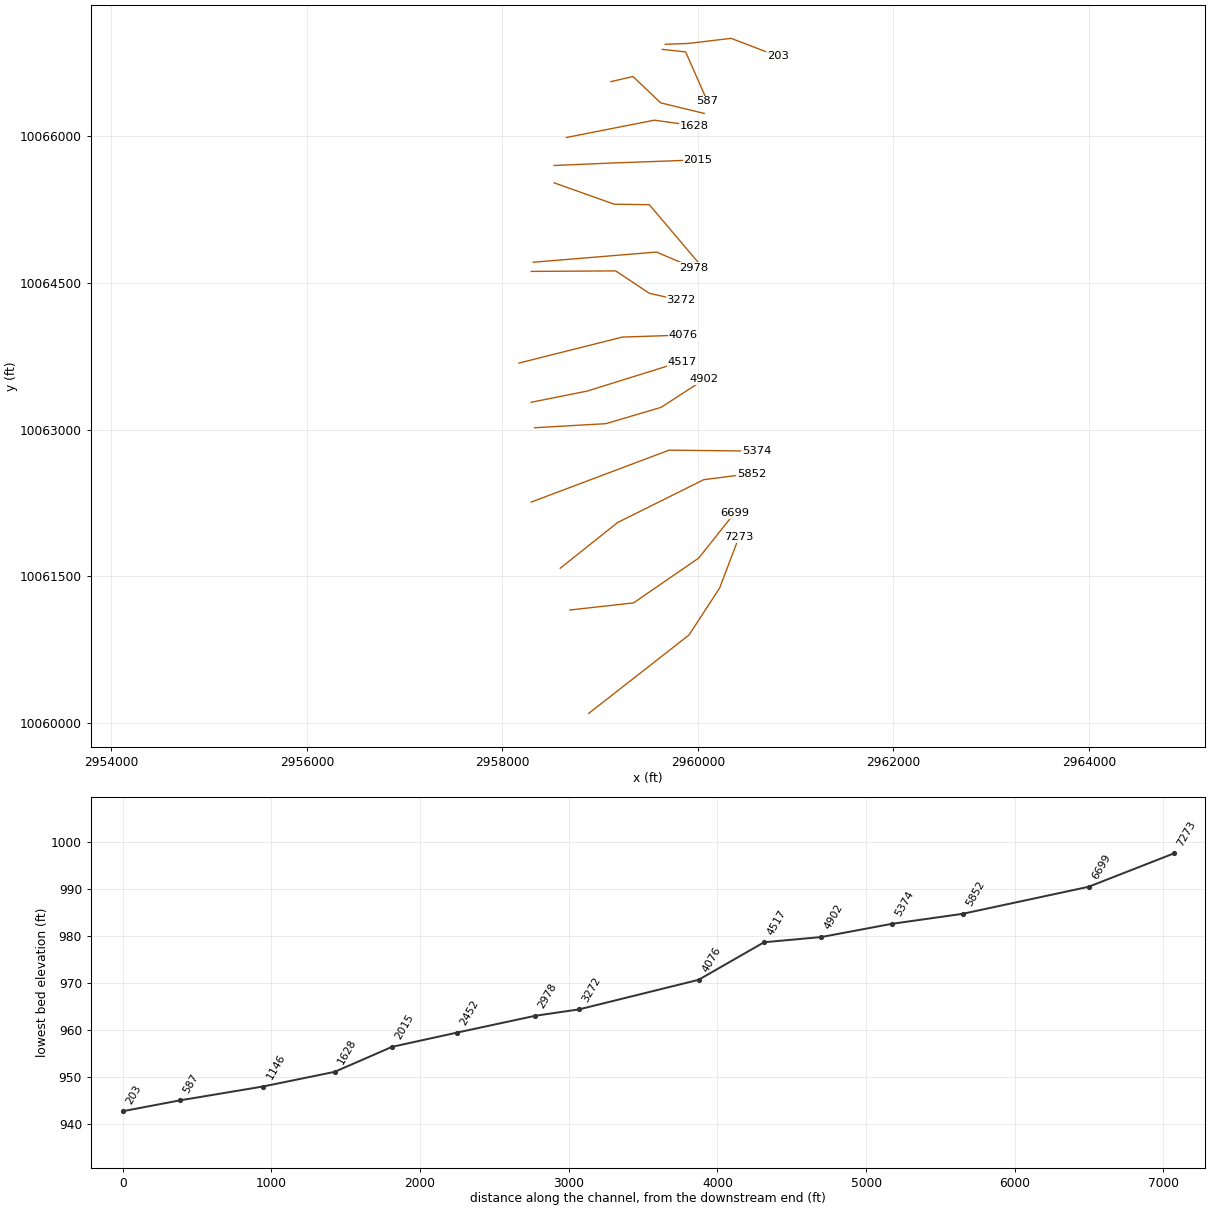
HEC-RAS study CALOHAN CREEK.prj: CALOHAN CREEK Base Level Engineering

--- CALOHAN CREEK.g01 (geometry) --- (continued)

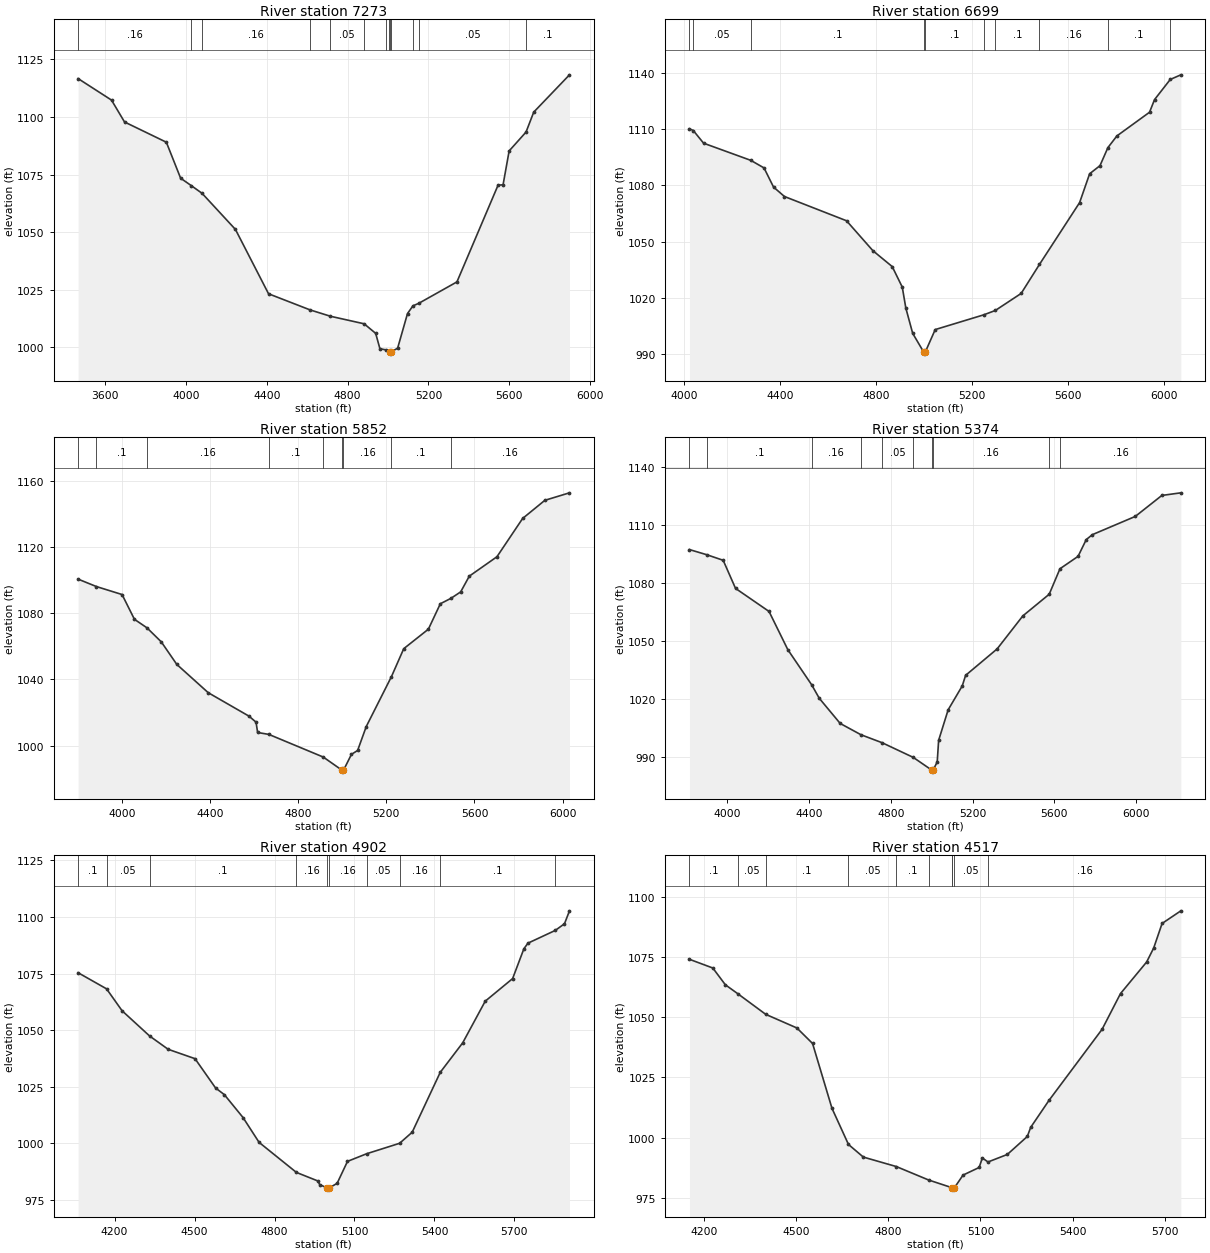
Type RM Length L Ch R = 1 ,7273    ,574,574,574
BEGIN DESCRIPTION:
CALOHAN CREEK 15.0
END DESCRIPTION:
XS GIS Cut Line= 4
      2958882.65     10060097.33      2959908.69     10060899.41
      2960221.19     10061378.57      2960418.97     10061899.06
#Sta/Elev= 30
  3466.8  1116.7  3632.1 1107.36  3696.4 1097.87  3903.4 1089.08    3974 1073.47
  4027.4  1070.2  4079.9 1066.92  4245.3 1051.22    4409  1023.3  4614.9 1016.29
  4715.5 1013.54    4882 1010.27  4939.1 1006.12  4960.1  999.44  4990.5  998.95
  5002.8  998.12  5008.5  998.04  5011.2  997.54  5014.5  998.04  5047.7  999.68
  5096.6 1014.72  5123.5 1018.07    5152 1019.14  5341.2 1028.46  5544.7 1070.45
  5569.4  1070.6  5599.5 1085.31  5683.1  1093.5  5721.1 1102.14    5898 1118.33
#Mann= 13 ,-1 , 0
  3466.8     .16       0  4027.4      .1       0  4079.9     .16       0
  4614.9      .1       0  4715.5     .05       0    4882     .16       0
  4990.5      .1       0  5002.8     .05       0  5008.5     .07       0
  5014.5     .05       0  5123.5      .1       0    5152     .05       0
  5683.1      .1       0
Bank Sta=5008.5,5014.5
XS Rating Curve= 0 ,0
Exp/Cntr=0.3,0.1

Type RM Length L Ch R = 1 ,6699    ,847,847,847
BEGIN DESCRIPTION:
CALOHAN CREEK 14.0
END DESCRIPTION:
XS GIS Cut Line= 4
      2958689.91     10061154.61      2959340.98     10061227.53
      2960007.65     10061685.87      2960372.22     10062144.19
#Sta/Elev= 30
  4021.3 1110.25  4037.2 1109.33  4080.2 1102.55  4277.3 1093.38  4332.3 1089.34
    4372 1079.12  4417.5 1074.08  4676.4 1061.13  4786.6 1045.12  4867.1 1036.65
    4909 1025.69  4923.9 1014.46  4952.5 1000.98  4998.7  990.93  5001.4  990.43
  5004.7  990.93  5046.4 1003.01  5248.6 1010.87    5297  1013.2  5404.9 1022.31
  5481.3 1037.81  5648.8 1070.83  5690.6 1086.23  5733.8 1090.56  5766.8 1100.18
  5804.3 1106.43  5940.5 1119.09  5961.3 1125.82  6026.9 1136.59  6071.1 1139.07
#Mann= 10 ,-1 , 0
  4021.3      .1       0  4037.2     .05       0  4277.3      .1       0
  4998.7     .07       0  5004.7      .1       0  5248.6     .05       0
    5297      .1       0  5481.3     .16       0  5766.8      .1       0
  6026.9     .16       0
Bank Sta=4998.7,5004.7
XS Rating Curve= 0 ,0
Exp/Cntr=0.3,0.1

Type RM Length L Ch R = 1 ,5852    ,478,478,478
BEGIN DESCRIPTION:
CALOHAN CREEK 12.0
END DESCRIPTION:
XS GIS Cut Line= 4
      2958590.97     10061581.69      2959179.52     10062050.45
      2960059.73     10062487.95       2960549.3     10062550.45
#Sta/Elev= 30
  3802.2 1100.51  3885.5 1096.02  4001.6 1091.22  4057.7 1076.28  4114.7 1071.12
  4179.4 1062.68  4249.9 1049.06  4392.4    1032  4577.3 1017.85  4609.3 1014.22
  4616.5 1007.99  4667.6 1006.83  4914.4  993.16  4999.9  985.18  5002.7  984.68
  5005.9  985.18  5042.1   994.8  5070.1  997.15  5109.3 1011.59  5223.6 1041.71
  5279.3 1058.55    5391 1070.31  5445.3 1085.66  5493.2 1088.91  5537.6 1092.82
  5576.6  1102.3  5702.1 1114.02  5818.6 1137.11  5919.4 1148.06  6031.1 1152.58
#Mann= 9 ,-1 , 0
  3802.2     .16       0  3885.5      .1       0  4114.7     .16       0
  4667.6      .1       0  4914.4     .16       0  4999.9     .07       0
  5005.9     .16       0  5223.6      .1       0  5493.2     .16       0
Bank Sta=4999.9,5005.9
XS Rating Curve= 0 ,0
Exp/Cntr=0.3,0.1

Type RM Length L Ch R = 1 ,5374    ,472,472,472
BEGIN DESCRIPTION:
CALOHAN CREEK 11.0
END DESCRIPTION:
XS GIS Cut Line= 3
       2958294.1     10062258.78      2959705.56     10062790.03
      2960601.37     10062779.62
#Sta/Elev= 30
  3814.6 1097.15  3900.4 1094.45  3979.5 1091.61  4039.9 1077.08  4203.9 1065.14
  4295.9 1045.35    4412 1027.27  4449.7 1020.21  4551.9 1007.21  4653.5 1001.37
  4757.2  997.23  4909.4  989.65  5000.4  983.04  5003.1  982.54  5006.4  983.04
  5026.7  987.32  5033.6  998.47  5080.1 1014.25  5149.1 1026.62  5165.6 1032.09
  5319.8 1045.77  5445.6 1062.85  5574.5 1074.04  5627.2 1087.23  5715.7 1093.64
  5755.7 1102.31  5785.7 1104.87  5995.7  1114.3  6125.7 1125.16  6218.6 1126.51
#Mann= 10 ,-1 , 0
  3814.6     .16       0  3900.4      .1       0    4412     .16       0
  4653.5      .1       0  4757.2     .05       0  4909.4     .16       0
  5000.4     .07       0  5006.4     .16       0  5574.5      .1       0
  5627.2     .16       0
Bank Sta=5000.4,5006.4
XS Rating Curve= 0 ,0
Exp/Cntr=0.3,0.1

Type RM Length L Ch R = 1 ,4902    ,385,385,385
BEGIN DESCRIPTION:
CALOHAN CREEK 10.0
END DESCRIPTION:
XS GIS Cut Line= 4
      2958330.59      10063019.2      2959059.73     10063060.87
      2959622.23     10063227.53      2960064.18      10063513.5
#Sta/Elev= 30
  4063.2 1075.39  4169.9 1068.27  4228.3 1058.56  4331.6 1047.41  4401.1 1041.54
  4501.8  1037.4  4578.9 1024.45    4612 1021.48  4682.1 1011.35  4742.2  1000.4
  4882.1  987.13  4963.2  983.32  4969.5  981.73  4998.6  980.24  5001.4  979.74
  5004.6  980.24  5034.9   982.3  5073.8  992.01  5145.9  995.39  5269.3    1000
  5316.5 1004.89  5421.7 1031.35    5506  1044.4  5590.5 1062.81  5693.3  1072.8
  5735.6 1085.99  5750.7 1088.45  5853.1 1094.08  5887.9 1097.04  5906.6 1102.75
#Mann= 10 ,-1 , 0
  4063.2      .1       0  4169.9     .05       0  4331.6      .1       0
  4882.1     .16       0  4998.6     .07       0  5004.6     .16       0
  5145.9     .05       0  5269.3     .16       0  5421.7      .1       0
  5853.1     .16       0
Bank Sta=4998.6,5004.6
XS Rating Curve= 0 ,0
Exp/Cntr=0.3,0.1

Type RM Length L Ch R = 1 ,4517    ,441,441,441
BEGIN DESCRIPTION:
CALOHAN CREEK 9.0
END DESCRIPTION:
XS GIS Cut Line= 3
      2958294.07     10063279.61      2958867.02      10063394.2
      2959834.67     10063695.94
#Sta/Elev= 30
  4153.7 1073.96  4229.6 1070.35  4270.4 1063.39  4311.3 1059.64  4401.7 1051.13
    4503 1045.48    4554 1039.04  4617.1 1012.15  4670.8  997.15  4719.1  991.92
  4826.2     988  4931.1  982.43  5006.1  979.27  5008.9  979.13  5011.6  978.63
  5014.9  979.13  5043.3  984.45  5095.7  987.61  5106.1  991.56  5124.5  989.89
  5187.3  993.01  5252.3 1000.47  5263.3 1004.25  5322.6  1015.4  5495.6 1044.95
  5555.4 1059.75  5640.4 1072.85  5663.4 1078.68  5690.6 1088.83  5751.6 1094.07
#Mann= 10 ,-1 , 0
  4153.7      .1       0  4311.3     .05       0  4401.7      .1       0
  4670.8     .05       0  4826.2      .1       0  4931.1     .16       0
  5006.1     .05       0  5008.9     .07       0  5014.9     .05       0
  5124.5     .16       0
Bank Sta=5008.9,5014.9
XS Rating Curve= 0 ,0
Exp/Cntr=0.3,0.1

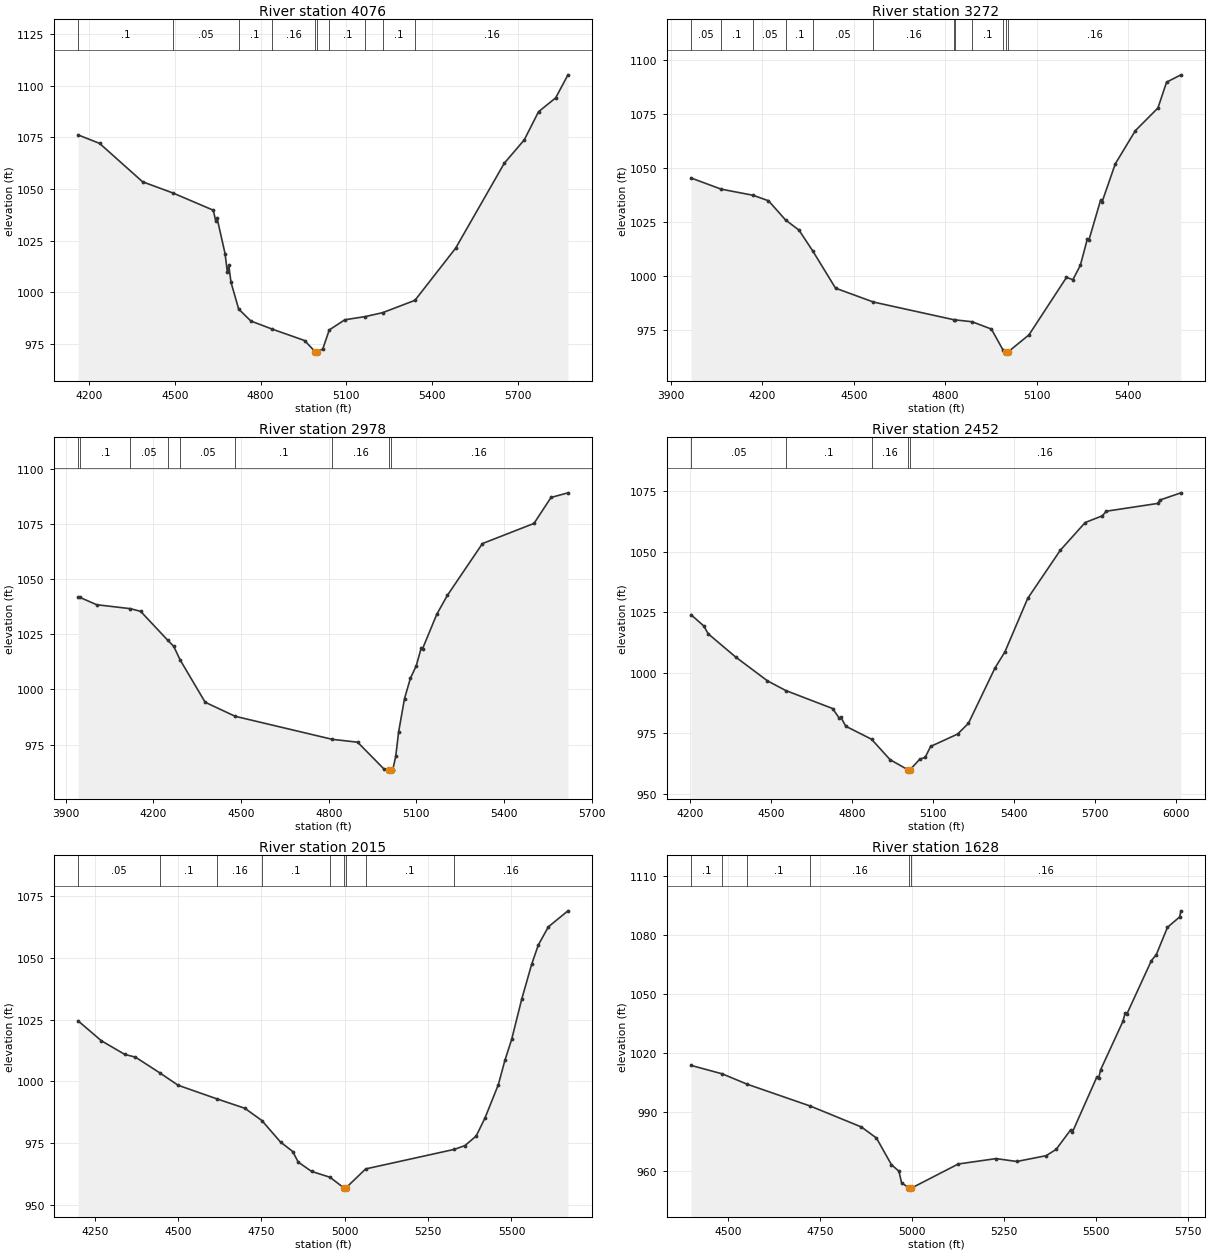
Type RM Length L Ch R = 1 ,4076    ,804,804,804
BEGIN DESCRIPTION:
CALOHAN CREEK 8.0
END DESCRIPTION:
XS GIS Cut Line= 3
      2958169.09     10063680.65       2959226.4     10063946.28
      2959851.38     10063967.12
#Sta/Elev= 30
    4161 1076.14  4236.4 1072.05  4387.2 1053.46  4492.7 1048.09  4634.7 1039.73
  4642.7 1034.75  4647.9 1035.87  4675.9  1018.7  4683.8 1009.82    4689 1013.03
  4696.5 1004.93  4723.5  991.94  4766.1  986.17  4839.3  982.32  4954.3  976.72
  4992.5  971.13  4995.3  970.63  4998.5  971.13  5018.1  972.69  5040.7  981.84
  5095.3  986.76  5167.2  988.31  5228.4  990.23  5340.8  996.17  5483.4 1021.42
  5653.5 1062.43  5723.5 1073.73  5773.5 1087.35  5833.6 1094.06  5876.5 1105.19
#Mann= 10 ,-1 , 0
    4161      .1       0  4492.7     .05       0  4723.5      .1       0
  4839.3     .16       0  4992.5     .07       0  4998.5     .16       0
  5040.7      .1       0  5167.2     .16       0  5228.4      .1       0
  5340.8     .16       0
Bank Sta=4992.5,4998.5
XS Rating Curve= 0 ,0
Exp/Cntr=0.3,0.1

Type RM Length L Ch R = 1 ,3272    ,294,294,294
BEGIN DESCRIPTION:
CALOHAN CREEK 6.0
END DESCRIPTION:
XS GIS Cut Line= 4
      2958294.14     10064618.16      2959158.69     10064623.37
      2959502.44      10064394.2      2959824.43     10064321.49
#Sta/Elev= 30
  3966.1 1045.28  4064.7 1040.13  4170.1 1037.27  4220.4 1034.75  4276.7 1025.83
  4320.4  1021.2  4366.2 1011.44  4440.4  994.36  4564.7  987.95  4829.8  979.74
  4831.3  979.74  4888.6  978.84  4951.9  975.46  4989.8  965.86    5000  964.84
  5002.7  964.34    5006  964.84  5075.1  972.76  5198.3  999.31  5219.3  998.29
  5243.8 1004.89    5267 1017.19  5272.1 1016.65  5310.2 1034.99  5315.3 1034.27
  5358.5 1051.81  5424.3 1067.13  5498.4 1077.61  5526.8 1089.54  5573.9 1092.94
#Mann= 12 ,-1 , 0
  3966.1     .05       0  4064.7      .1       0  4170.1     .05       0
  4276.7      .1       0  4366.2     .05       0  4564.7     .16       0
  4829.8      .1       0  4831.3     .16       0  4888.6      .1       0
  4989.8     .16       0    5000     .07       0    5006     .16       0
Bank Sta=5000,5006
XS Rating Curve= 0 ,0
Exp/Cntr=0.3,0.1

Type RM Length L Ch R = 1 ,2978    ,526,526,526
BEGIN DESCRIPTION:
CALOHAN CREEK 5.0
END DESCRIPTION:
XS GIS Cut Line= 3
      2958314.97     10064711.91      2959575.36     10064816.07
      2959954.51     10064655.07
#Sta/Elev= 30
  3942.1 1041.79  3949.4 1041.64  4005.8 1038.37  4121.3 1036.58  4156.3 1035.37
  4248.5 1022.36  4269.7 1019.49  4291.1 1013.46  4377.1  994.19  4479.7  987.83
  4811.9  977.39  4898.8  976.09  4989.2  963.93  5006.2  963.48    5009  962.98
  5012.2  963.48  5019.3  963.62  5029.3  969.71  5039.3   980.8  5059.4  995.84
  5079.5 1005.03  5099.5 1010.69  5116.1 1018.57  5121.1 1018.43  5169.8 1034.03
  5205.8 1042.56  5326.1 1066.08  5502.5  1075.2  5560.7 1086.95  5618.7 1089.06
#Mann= 9 ,-1 , 0
  3942.1     .05       0  3949.4      .1       0  4121.3     .05       0
  4248.5      .1       0  4291.1     .05       0  4479.7      .1       0
  4811.9     .16       0  5006.2     .07       0  5012.2     .16       0
Bank Sta=5006.2,5012.2
XS Rating Curve= 0 ,0
Exp/Cntr=0.3,0.1

Type RM Length L Ch R = 1 ,2452    ,437,437,437
BEGIN DESCRIPTION:
CALOHAN CREEK 4.0
END DESCRIPTION:
XS GIS Cut Line= 4
      2958528.46     10065524.42      2959143.06     10065305.66
      2959502.44     10065300.45      2960022.05      10064687.3
#Sta/Elev= 30
    4202 1023.97  4249.3 1019.31  4265.7 1016.08  4367.3  1006.5  4485.3  996.66
  4553.2  992.66  4726.7  985.24  4752.2  981.15  4757.5  981.63  4775.2  977.95
    4871  972.57  4939.8  964.12  5006.8   959.9  5009.5   959.4  5012.8   959.9
  5049.8  964.32  5069.8  965.08  5089.8  969.58  5189.8  974.69    5230  979.12
  5328.8 1002.03  5365.1 1008.58  5449.7 1030.68  5570.5 1050.55  5662.8    1062
  5726.5 1064.77  5740.8 1066.66  5931.9 1069.88  5939.7 1071.28  6017.5 1074.25
#Mann= 5 ,-1 , 0
    4202     .05       0  4553.2      .1       0    4871     .16       0
  5006.8     .07       0  5012.8     .16       0
Bank Sta=5006.8,5012.8
XS Rating Curve= 0 ,0
Exp/Cntr=0.3,0.1

Type RM Length L Ch R = 1 ,2015    ,387,387,387
BEGIN DESCRIPTION:
CALOHAN CREEK 3.0
END DESCRIPTION:
XS GIS Cut Line= 3
      2958528.48     10065701.49      2959137.86     10065727.53
      2959997.26     10065758.78
#Sta/Elev= 30
  4199.6  1024.5  4269.6 1016.42  4339.7 1010.91    4372 1009.78  4445.2  1003.4
  4499.9  998.41  4616.2  992.91    4700   989.1  4751.2  984.13  4807.3  975.41
  4843.8  971.59  4860.2  967.32  4900.2  963.55  4955.7  961.17  4997.3  956.87
    5000  956.37  5003.3  956.87  5062.6  964.55  5328.8  972.47  5360.5     974
  5394.2  977.88  5420.5  985.14  5460.6  998.63  5480.6 1008.62  5500.6 1016.96
  5530.6 1033.16  5560.6 1047.37  5580.6 1055.18  5610.7 1062.53  5669.5 1069.01
#Mann= 9 ,-1 , 0
  4199.6     .05       0  4445.2      .1       0  4616.2     .16       0
  4751.2      .1       0  4955.7     .16       0  4997.3     .07       0
  5003.3     .16       0  5062.6      .1       0  5328.8     .16       0
Bank Sta=4997.3,5003.3
XS Rating Curve= 0 ,0
Exp/Cntr=0.3,0.1

Type RM Length L Ch R = 1 ,1628    ,482,482,482
BEGIN DESCRIPTION:
CALOHAN CREEK 2.0
END DESCRIPTION:
XS GIS Cut Line= 3
      2958653.45     10065987.94      2959554.52     10066165.03
      2959964.76     10066107.91
#Sta/Elev= 30
  4398.6 1013.83  4483.7 1009.52  4552.2 1004.22  4723.2  993.18  4862.3  982.55
  4903.1  976.94  4943.8  963.42  4964.2  960.13  4971.2  954.33  4991.8  951.54
  4994.6  951.04  4997.8  951.54  5125.4  963.79  5228.2  966.53  5284.7  965.07
  5364.5  968.01  5391.6   971.2    5431  981.05  5436.1  980.02  5502.6    1008
  5507.6 1007.61  5512.7 1011.59  5573.3 1036.15  5579.2 1040.29  5584.3    1040
  5650.8 1066.98  5664.2 1070.06  5694.5 1083.88  5727.5 1089.13  5731.1 1092.25
#Mann= 6 ,-1 , 0
  4398.6      .1       0  4483.7     .05       0  4552.2      .1       0
  4723.2     .16       0  4991.8     .07       0  4997.8     .16       0
Bank Sta=4991.8,4997.8
XS Rating Curve= 0 ,0
Exp/Cntr=0.3,0.1

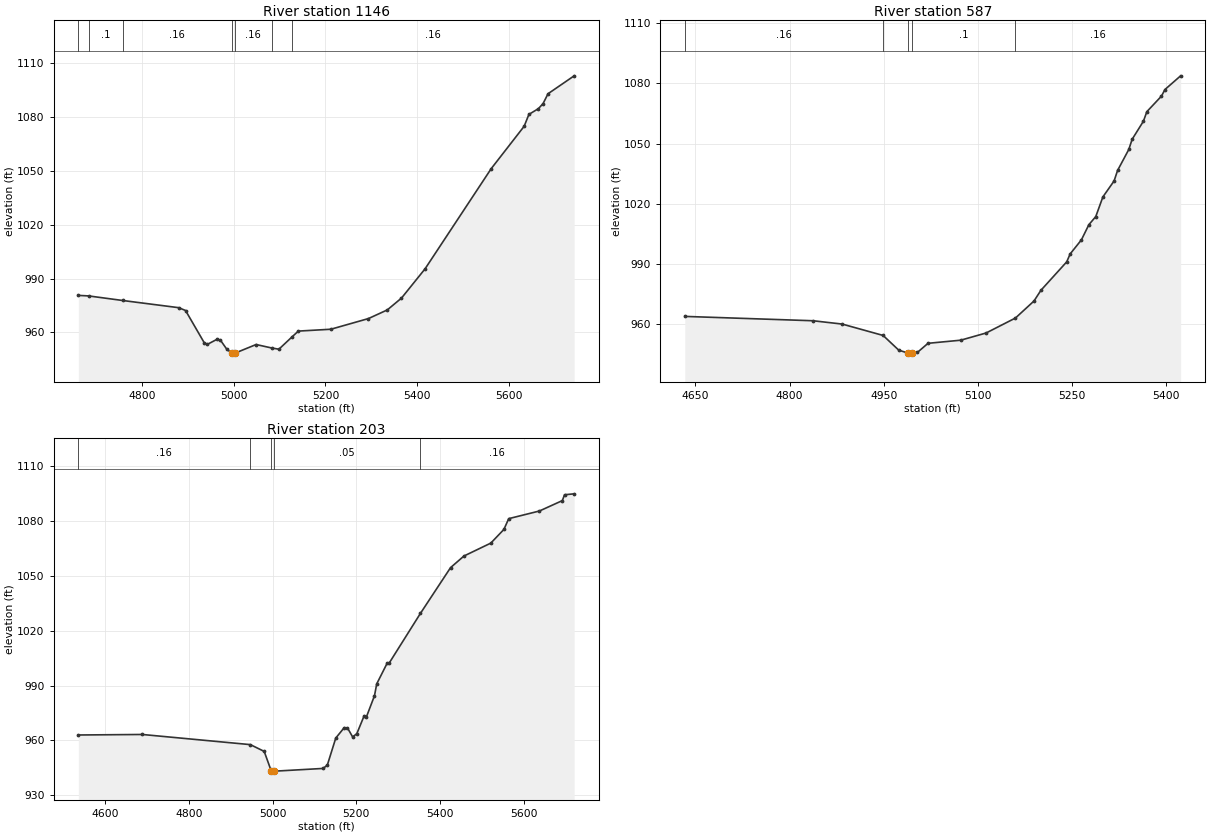
Type RM Length L Ch R = 1 ,1146    ,559,559,559
BEGIN DESCRIPTION:
Mapping XS 265fc098
END DESCRIPTION:
XS GIS Cut Line= 4
      2959110.11     10066559.53       2959335.8     10066611.62
      2959617.92     10066342.52      2960064.26     10066234.19
#Sta/Elev= 30
  4661.3  980.64  4683.5  980.35  4757.8   977.8  4880.2  973.79    4895  972.22
  4935.9  954.19  4942.8  953.38  4964.2  956.26  4971.1  955.68  4985.2  950.55
  4996.4  948.42  4999.1  947.92  5002.4  948.42  5048.8  953.27  5082.7  951.35
  5098.5  950.66  5127.8  957.68  5140.9  960.75  5211.7  961.78  5293.7  967.73
  5334.8  972.55  5365.7  979.13  5417.1  995.43  5561.2 1051.21  5633.1 1074.84
  5643.5 1081.47  5664.1 1084.64  5674.4 1087.49  5685.1 1092.95  5742.1 1102.94
#Mann= 7 ,-1 , 0
  4661.3     .16       0  4683.5      .1       0  4757.8     .16       0
  4996.4     .07       0  5002.4     .16       0  5082.7      .1       0
  5127.8     .16       0
Bank Sta=4996.4,5002.4
XS Rating Curve= 0 ,0
Exp/Cntr=0.3,0.1

Type RM Length L Ch R = 1 ,587     ,384,384,384
BEGIN DESCRIPTION:
Mapping XS aeaa629a
END DESCRIPTION:
XS GIS Cut Line= 3
      2959635.25      10066889.4      2959873.99     10066863.35
      2960095.33     10066359.92
#Sta/Elev= 30
    4633  963.79  4837.4  961.62  4883.7  959.97    4949  954.29  4973.9  946.96
  4988.8  945.47  4991.5  944.97  4994.8  945.47  5003.8  945.87  5020.6  950.37
  5072.7  951.92  5113.1  955.51  5159.9  962.98  5189.5  971.49  5200.5  976.82
  5241.6  991.01  5247.1  994.97    5265 1001.97  5276.9 1009.55  5287.9  1013.6
  5299.2 1023.39  5317.1 1031.38  5322.6 1036.58  5340.5 1047.07  5345.9 1052.18
  5363.8 1061.16  5369.3 1065.93  5392.6  1073.7  5398.1 1076.97  5423.1 1083.81
#Mann= 5 ,-1 , 0
    4633     .16       0    4949      .1       0  4988.8     .07       0
  4994.8      .1       0  5159.9     .16       0
Bank Sta=4988.8,4994.8
XS Rating Curve= 0 ,0
Exp/Cntr=0.3,0.1

Type RM Length L Ch R = 1 ,203     ,0,0,0
BEGIN DESCRIPTION:
CALOHAN CREEK 1.0
END DESCRIPTION:
XS GIS Cut Line= 4
      2959665.63     10066941.48      2959904.38     10066950.16
       2960338.4     10067002.24      2960814.63     10066820.41
#Sta/Elev= 30
  4535.3  962.98  4688.2  963.26  4946.7  957.71  4979.8     954  4996.9  943.16
  4999.6  942.66  5002.9  943.16  5120.8  944.68  5130.8  946.53    5151  961.31
  5171.1  966.97    5179  966.85  5191.3  961.93  5201.3  963.69    5219  973.56
  5224.3  972.89  5243.5  984.41    5249  990.98  5273.8 1002.23  5279.1 1002.47
  5353.4  1029.5  5425.5 1054.55  5457.6 1060.91  5521.8 1067.97  5553.1 1075.46
  5564.6 1081.35    5638 1085.53  5692.8 1091.22  5698.1 1094.42  5721.1 1094.93
#Mann= 5 ,-1 , 0
  4535.3     .16       0  4946.7     .05       0  4996.9    .035       0
  5002.9     .05       0  5353.4     .16       0
Bank Sta=4996.9,5002.9
XS Rating Curve= 0 ,0
Exp/Cntr=0.3,0.1

Chan Stop Cuts=-1
Use User Specified Reach Order=0
Composite Channel Slope=5