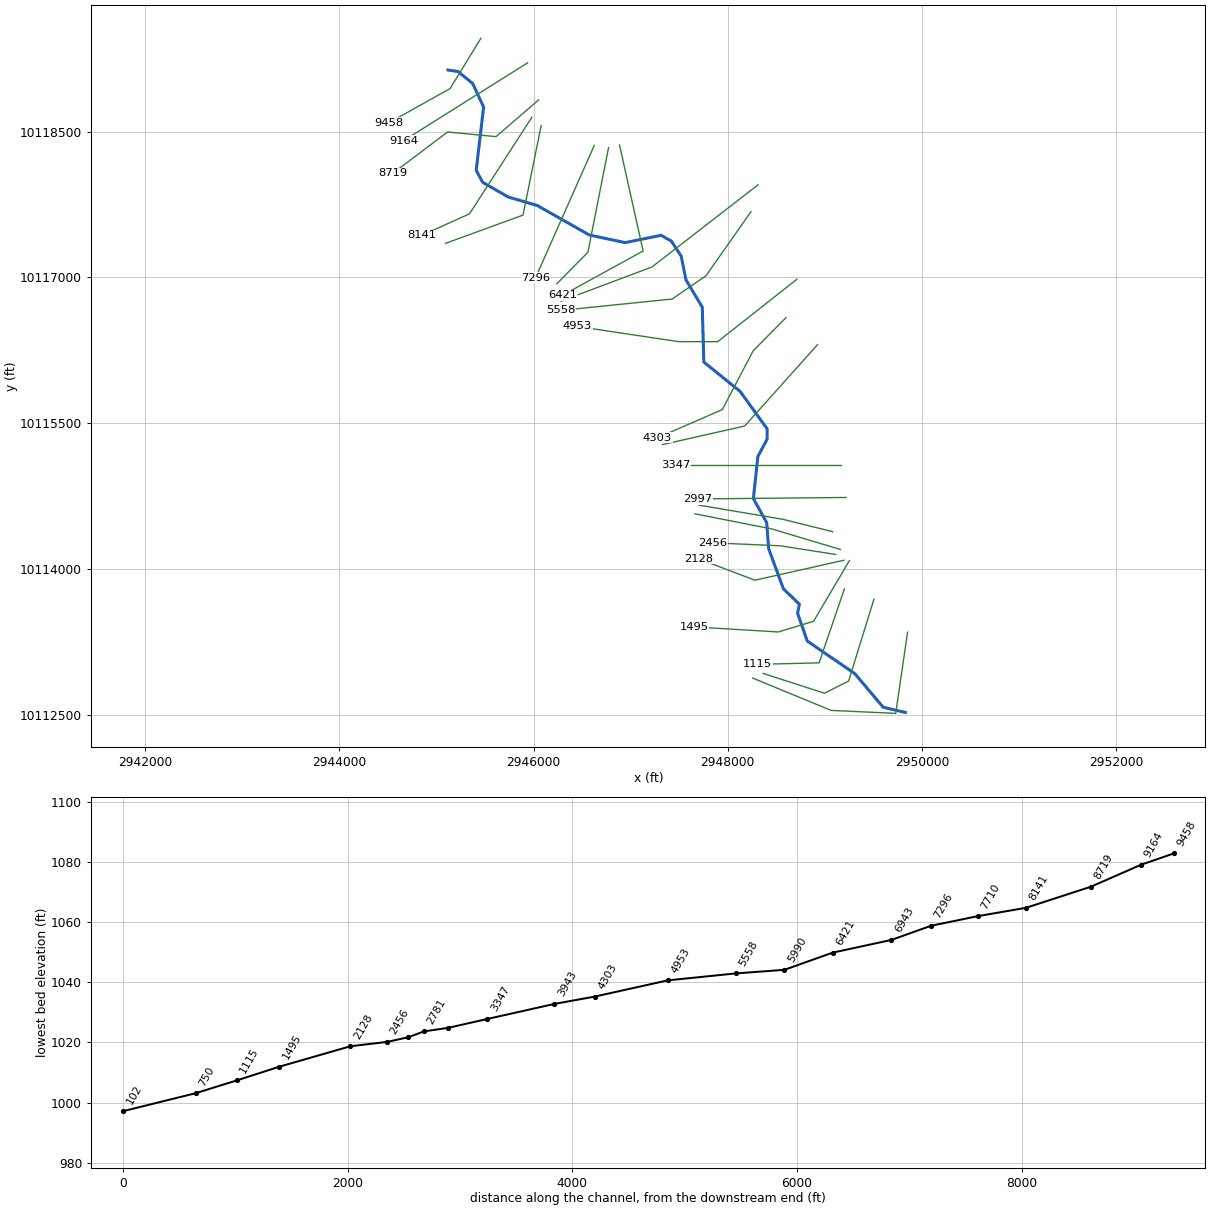
--- CLEVELAND BRANCH.prj (project) ---

Proj Title=CLEVELAND BRANCH Base Level Engineering
Current Plan=p01
Default Exp/Contr=0.3,0.1
English Units
Geom File=g01
Flow File=f01
Plan File=p01
BEGIN DESCRIPTION:
CLEVELAND BRANCH
END DESCRIPTION:

--- CLEVELAND BRANCH.p01 (plan) ---

Plan Title=Multiple Run
Short Identifier=Multiple
Geom File=g01
Flow File=f01
Subcritical Flow
K Sum by GR= 0
Std Step Tol= 0.01
Critical Tol= 0.01
Num of Std Step Trials= 20
Max Error Tol= 0.3
Flow Tol Ratio= 0.001
Split Flow NTrial= 30
Split Flow Tol= 0.02
Split Flow Ratio= 0.02
Log Output Level= 0
Friction Slope Method= 1
Unsteady Friction Slope Method= 2
Unsteady Bridges Friction Slope Method= 1
Parabolic Critical Depth
Global Vel Dist=  1 , 1 , 1
Global Log Level= 0
CheckData=True
Encroach Param= -1, 0, 0, 0
BEGIN DESCRIPTION:
Multiple Run
END DESCRIPTION:

--- CLEVELAND BRANCH.f01 (steady flow) ---

Flow Title=Multiple
Number of Profiles=7
Profile Names=10-year,25-year,50-year,1pct_min,100-year,1pct_plu,500-year
River Rch & RM= CLEVELAND BRANCH,Reach-1,9458
     866    1257    1597    1485    2008    2716    3188
River Rch & RM= CLEVELAND BRANCH,Reach-1,5990
    1894    2850    3706    3518    4757    6433    7878
River Rch & RM= CLEVELAND BRANCH,Reach-1,102
    9681   15241   20446   19926   26948   36443   47013
Boundary for River Rch & Prof#=CLEVELAND BRANCH,Reach-1,1
Up Type=0
Dn Type=3
Dn Slope=0.005
Boundary for River Rch & Prof#=CLEVELAND BRANCH,Reach-1,2
Up Type=0
Dn Type=3
Dn Slope=0.005
Boundary for River Rch & Prof#=CLEVELAND BRANCH,Reach-1,3
Up Type=0
Dn Type=3
Dn Slope=0.005
Boundary for River Rch & Prof#=CLEVELAND BRANCH,Reach-1,4
Up Type=0
Dn Type=3
Dn Slope=0.005
Boundary for River Rch & Prof#=CLEVELAND BRANCH,Reach-1,5
Up Type=0
Dn Type=3
Dn Slope=0.005
Boundary for River Rch & Prof#=CLEVELAND BRANCH,Reach-1,6
Up Type=0
Dn Type=3
Dn Slope=0.005
Boundary for River Rch & Prof#=CLEVELAND BRANCH,Reach-1,7
Up Type=0
Dn Type=3
Dn Slope=0.005

--- CLEVELAND BRANCH.g01 (geometry) ---

Geom Title=Existing Conditions

River Reach=CLEVELAND BRANCH,Reach-1
Reach XY= 30
      2945118.47     10119133.73      2945220.92     10119118.28
      2945373.00     10118995.29      2945485.51     10118752.50
      2945409.06     10118101.51      2945475.48     10117978.71
      2945739.60     10117826.48      2946036.99     10117740.17
      2946574.39     10117435.95      2946943.47     10117357.71
      2947313.31     10117433.18      2947418.47     10117373.73
      2947520.35     10117218.74      2947570.09     10116972.91
      2947737.59     10116693.37      2947753.56     10116128.96
      2948127.72     10115826.60      2948405.03     10115442.18
      2948405.28     10115335.03      2948310.04     10115156.61
      2948263.82     10114724.54      2948400.98     10114476.60
      2948421.02     10114209.68      2948572.83     10113795.85
      2948737.54     10113638.10      2948719.41     10113544.52
      2948818.52     10113258.68      2949308.39     10112923.27
      2949600.69     10112577.14      2949828.47     10112523.73

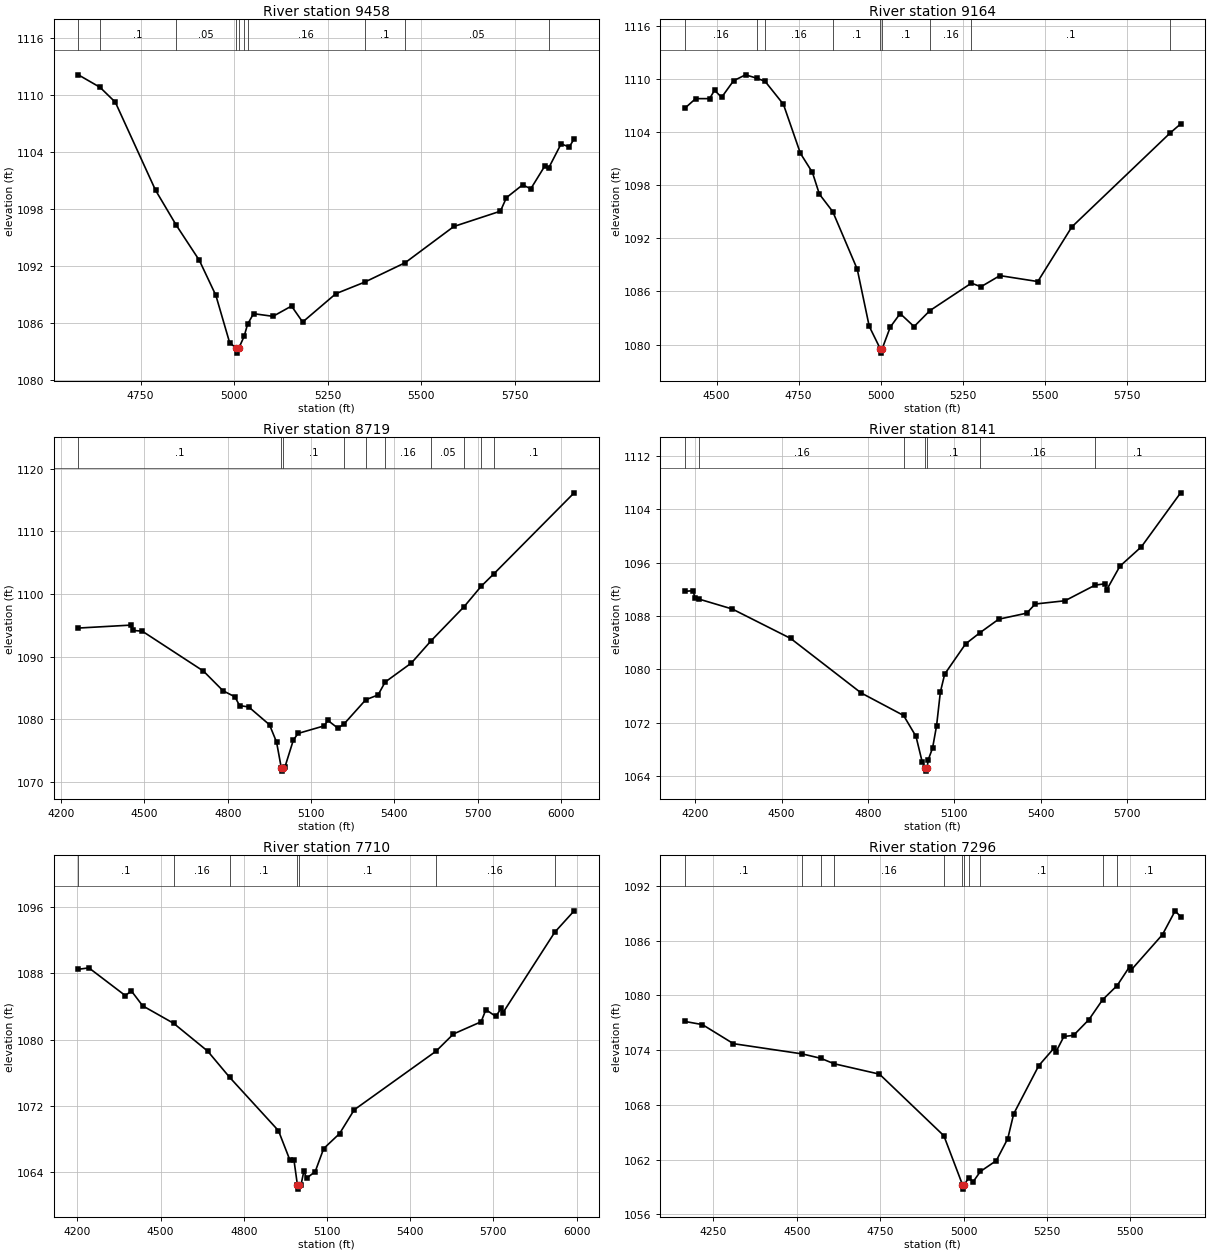
Type RM Length L Ch R = 1,9458,294,294,294
BEGIN DESCRIPTION:
CLEVELAND BRANCH 21.0
END DESCRIPTION:
XS GIS Cut Line= 3
      2945457.31     10119459.54      2945140.47     10118943.05
      2944512.27     10118592.13
#Sta/Elev= 30
  4583.6 1112.09  4641.5 1110.78  4682.5 1109.21  4789.9 1099.96  4845.0 1096.30
  4907.2 1092.57  4951.3 1088.89  4988.0 1083.93  5006.3 1083.32  5009.0 1082.82
  5012.3 1083.32  5026.7 1084.57  5036.0 1085.85  5051.9 1086.97  5104.0 1086.69
  5153.5 1087.77  5183.3 1086.09  5272.0 1089.07  5348.7 1090.28  5457.4 1092.33
  5587.5 1096.14  5712.0 1097.75  5728.0 1099.17  5771.4 1100.52  5793.1 1100.10
  5830.8 1102.51  5840.7 1102.27  5874.2 1104.83  5895.9 1104.50  5909.1 1105.35
#Mann=10,-1,0
  4583.6    0.16       0  4641.5     0.1       0  4845.0    0.05       0
  5006.3   0.035       0  5012.3    0.05       0  5026.7     0.1       0
  5036.0    0.16       0  5348.7     0.1       0  5457.4    0.05       0
  5840.7     0.1       0
Bank Sta=5006.3,5012.3
Exp/Cntr=0.3,0.1

Type RM Length L Ch R = 1,9164,445,445,445
BEGIN DESCRIPTION:
CLEVELAND BRANCH 20.0
END DESCRIPTION:
XS GIS Cut Line= 2
      2945939.11     10119207.82      2944658.66     10118404.83
#Sta/Elev= 30
  4403.0 1106.70  4436.1 1107.79  4478.5 1107.79  4493.8 1108.74  4515.1 1107.93
  4551.6 1109.81  4588.1 1110.48  4623.2 1110.09  4647.8 1109.74  4703.6 1107.15
  4755.4 1101.61  4792.0 1099.45  4813.2 1097.00  4854.0 1095.02  4928.7 1088.51
  4965.2 1082.06  4998.7 1079.53  5001.5 1079.03  5004.7 1079.53  5029.4 1081.98
  5059.5 1083.50  5101.9 1082.03  5150.0 1083.83  5276.6 1086.94  5305.7 1086.53
  5363.5 1087.79  5479.0 1087.12  5582.7 1093.29  5882.8 1103.92  5914.4 1104.93
#Mann=9,-1,0
  4403.0    0.16       0  4623.2     0.1       0  4647.8    0.16       0
  4854.0     0.1       0  4998.7    0.07       0  5004.7     0.1       0
  5150.0    0.16       0  5276.6     0.1       0  5882.8    0.05       0
Bank Sta=4998.7,5004.7
Exp/Cntr=0.3,0.1

Type RM Length L Ch R = 1,8719,578,578,578
BEGIN DESCRIPTION:
CLEVELAND BRANCH 19.0
END DESCRIPTION:
XS GIS Cut Line= 4
      2946051.95     10118825.88      2945613.56     10118448.26
      2945114.43     10118496.00      2944550.20     10118070.66
#Sta/Elev= 30
  4261.6 1094.56  4450.4 1095.03  4457.0 1094.19  4492.1 1094.06  4712.6 1087.69
  4782.9 1084.56  4825.6 1083.60  4842.7 1082.19  4875.5 1081.98  4950.5 1079.13
  4975.9 1076.37  4993.0 1072.24  4995.8 1071.74  4999.0 1072.24  5006.0 1072.39
  5036.2 1076.67  5053.2 1077.75  5146.7 1078.95  5161.0 1079.82  5196.9 1078.59
  5219.1 1079.27  5297.2 1083.12  5341.6 1083.89  5367.0 1085.94  5461.8 1088.99
  5532.2 1092.51  5652.0 1097.99  5713.1 1101.22  5759.3 1103.23  6048.2 1116.13
#Mann=10,-1,0
  4261.6     0.1       0  4993.0    0.07       0  4999.0     0.1       0
  5219.1    0.16       0  5297.2     0.1       0  5367.0    0.16       0
  5532.2    0.05       0  5652.0     0.1       0  5713.1    0.05       0
  5759.3     0.1       0
Bank Sta=4993,4999
Exp/Cntr=0.3,0.1

Type RM Length L Ch R = 1,8141,431,431,431
BEGIN DESCRIPTION:
CLEVELAND BRANCH 18.0
END DESCRIPTION:
XS GIS Cut Line= 3
      2945982.49     10118647.93      2945340.12     10117653.99
      2944849.71     10117432.65
#Sta/Elev= 30
  4164.2 1091.70  4193.0 1091.80  4199.1 1090.75  4214.9 1090.52  4329.1 1089.05
  4531.6 1084.64  4776.4 1076.46  4923.8 1073.08  4966.9 1069.94  4988.1 1066.17
  4999.7 1065.23  5002.4 1064.73  5005.7 1065.23  5009.2 1066.41  5024.4 1068.18
  5038.4 1071.55  5051.5 1076.59  5066.6 1079.29  5139.2 1083.82  5189.8 1085.52
  5254.0 1087.52  5351.3 1088.43  5380.8 1089.80  5484.3 1090.29  5589.1 1092.64
  5623.0 1092.83  5628.5 1091.89  5674.8 1095.47  5749.6 1098.39  5885.7 1106.48
#Mann=7,-1,0
  4164.2     0.1       0  4214.9    0.16       0  4923.8     0.1       0
  4999.7    0.07       0  5005.7     0.1       0  5189.8    0.16       0
  5589.1     0.1       0
Bank Sta=4999.7,5005.7
Exp/Cntr=0.3,0.1

Type RM Length L Ch R = 1,7710,414,414,414
BEGIN DESCRIPTION:
CLEVELAND BRANCH 17.0
END DESCRIPTION:
XS GIS Cut Line= 3
      2946077.97     10118561.11      2945891.34     10117640.97
      2945093.09     10117350.30
#Sta/Elev= 30
  4203.1 1088.49  4241.2 1088.66  4372.7 1085.31  4394.3 1085.88  4435.1 1084.08
  4547.0 1081.96  4669.8 1078.60  4748.9 1075.44  4924.9 1069.00  4965.7 1065.49
  4980.7 1065.49  4993.3 1062.44  4996.1 1061.94  4999.3 1062.44  5006.5 1062.49
  5016.7 1064.14  5026.2 1063.25  5057.5 1064.06  5088.1 1066.84  5145.2 1068.64
  5198.2 1071.52  5493.0 1078.59  5556.2 1080.68  5655.9 1082.15  5673.2 1083.62
  5709.1 1082.79  5729.0 1083.84  5734.4 1083.23  5921.6 1092.97  5991.5 1095.55
#Mann=7,-1,0
  4203.1     0.1       0  4547.0    0.16       0  4748.9     0.1       0
  4993.3    0.07       0  4999.3     0.1       0  5493.0    0.16       0
  5921.6     0.1       0
Bank Sta=4993.3,4999.3
Exp/Cntr=0.3,0.1

Type RM Length L Ch R = 1,7296,353,353,353
BEGIN DESCRIPTION:
CLEVELAND BRANCH 16.0
END DESCRIPTION:
XS GIS Cut Line= 2
      2946624.83     10118357.08      2946021.59     10116998.70
#Sta/Elev= 30
  4164.3 1077.14  4217.1 1076.79  4310.1 1074.70  4516.2 1073.58  4571.6 1073.10
  4612.0 1072.50  4747.9 1071.36  4940.9 1064.61  4996.5 1059.26  4999.3 1058.76
  5002.5 1059.26  5015.4 1060.02  5028.5 1059.56  5050.5 1060.70  5098.0 1061.88
  5132.4 1064.29  5150.2 1067.01  5225.5 1072.30  5272.0 1074.25  5277.5 1073.84
  5300.7 1075.49  5329.5 1075.61  5376.0 1077.35  5416.6 1079.51  5460.3 1081.07
  5497.8 1083.15  5503.2 1082.81  5596.3 1086.66  5634.2 1089.26  5650.6 1088.62
#Mann=11,-1,0
  4164.3     0.1       0  4516.2    0.16       0  4571.6     0.1       0
  4612.0    0.16       0  4940.9     0.1       0  4996.5    0.07       0
  5002.5     0.1       0  5015.4    0.16       0  5050.5     0.1       0
  5416.6    0.05       0  5460.3     0.1       0
Bank Sta=4996.5,5002.5
Exp/Cntr=0.3,0.1

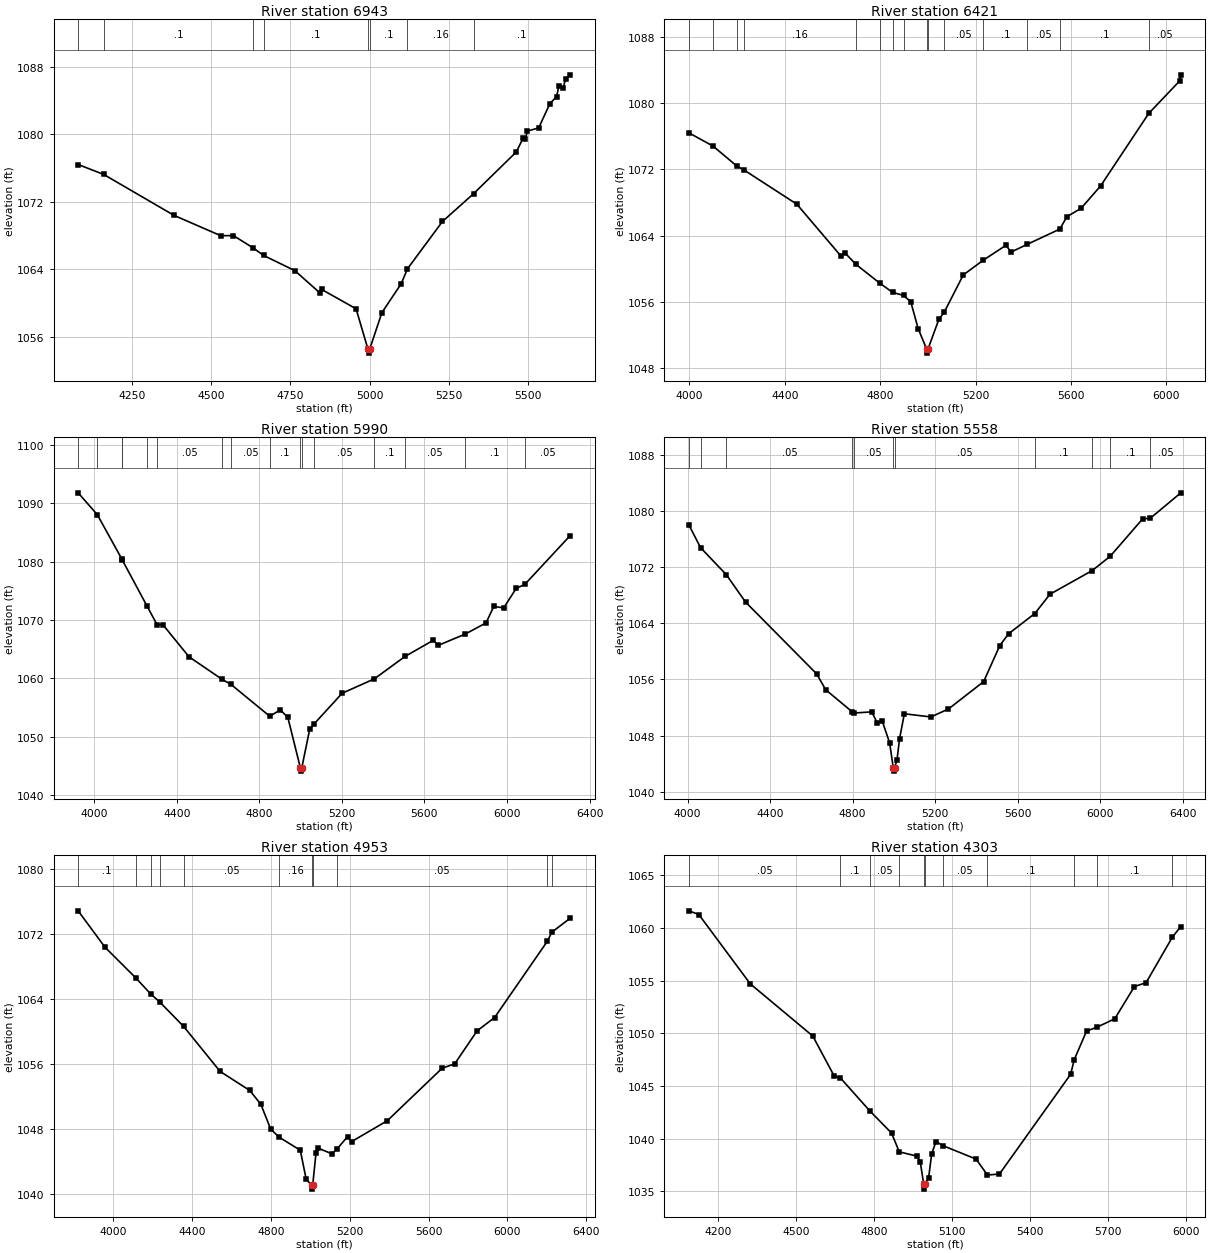
Type RM Length L Ch R = 1,6943,522,522,522
BEGIN DESCRIPTION:
CLEVELAND BRANCH 15.0
END DESCRIPTION:
XS GIS Cut Line= 3
      2946772.42     10118335.46      2946559.74     10117259.02
      2946238.59     10116933.54
#Sta/Elev= 30
  4079.0 1076.43  4159.8 1075.25  4382.3 1070.39  4529.3 1067.99  4570.0 1067.99
  4632.6 1066.52  4665.1 1065.64  4763.7 1063.84  4843.8 1061.17  4848.9 1061.60
  4957.4 1059.31  4994.7 1054.55  4997.4 1054.05  5000.7 1054.55  5038.9 1058.85
  5100.1 1062.29  5119.7 1064.05  5230.4 1069.67  5328.5 1072.96  5463.8 1077.92
  5484.9 1079.53  5492.1 1079.43  5499.1 1080.40  5534.5 1080.77  5569.8 1083.65
  5591.1 1084.49  5598.1 1085.71  5612.2 1085.56  5619.3 1086.56  5633.5 1087.07
#Mann=8,-1,0
  4079.0    0.16       0  4159.8     0.1       0  4632.6    0.16       0
  4665.1     0.1       0  4994.7    0.07       0  5000.7     0.1       0
  5119.7    0.16       0  5328.5     0.1       0
Bank Sta=4994.7,5000.7
Exp/Cntr=0.3,0.1

Type RM Length L Ch R = 1,6421,431,431,431
BEGIN DESCRIPTION:
CLEVELAND BRANCH 14.0
END DESCRIPTION:
XS GIS Cut Line= 3
      2946885.27     10118361.44      2947128.32     10117272.05
      2946299.31     10116816.31
#Sta/Elev= 30
  3997.9 1076.39  4099.2 1074.79  4199.0 1072.38  4227.9 1071.93  4450.2 1067.79
  4634.2 1061.57  4651.3 1061.94  4698.0 1060.53  4799.2 1058.24  4851.4 1057.16
  4897.5 1056.79  4927.9 1056.02  4958.9 1052.78  4994.2 1050.33  4997.0 1049.83
  5000.2 1050.33  5045.8 1053.91  5067.6 1054.73  5148.1 1059.26  5232.5 1061.05
  5326.8 1062.83  5348.6 1062.02  5417.0 1062.96  5553.0 1064.79  5582.6 1066.29
  5642.2 1067.30  5723.7 1069.99  5926.0 1078.75  6055.2 1082.65  6060.1 1083.39
#Mann=15,-1,0
  3997.9     0.1       0  4099.2    0.16       0  4199.0     0.1       0
  4227.9    0.16       0  4698.0     0.1       0  4799.2    0.16       0
  4851.4    0.05       0  4897.5     0.1       0  4994.2    0.07       0
  5000.2     0.1       0  5067.6    0.05       0  5232.5     0.1       0
  5417.0    0.05       0  5553.0     0.1       0  5926.0    0.05       0
Bank Sta=4994.2,5000.2
Exp/Cntr=0.3,0.1

Type RM Length L Ch R = 1,5990,432,432,432
BEGIN DESCRIPTION:
CLEVELAND BRANCH 13.0
END DESCRIPTION:
XS GIS Cut Line= 3
      2948313.21     10117953.47      2947219.46     10117107.11
      2946282.73     10116755.84
#Sta/Elev= 30
  3922.0 1091.81  4014.8 1088.07  4134.5 1080.42  4135.6 1080.32  4256.5 1072.36
  4304.5 1069.20  4332.3 1069.23  4459.1 1063.71  4618.9 1059.86  4663.1 1058.96
  4850.3 1053.52  4901.6 1054.60  4938.0 1053.33  4999.3 1044.61  5002.1 1044.11
  5005.3 1044.61  5044.0 1051.28  5066.1 1052.23  5201.5 1057.46  5357.5 1059.93
  5505.6 1063.76  5642.3 1066.52  5667.2 1065.67  5798.9 1067.62  5898.6 1069.52
  5936.2 1072.35  5984.0 1072.08  6044.6 1075.43  6086.0 1076.10  6305.4 1084.45
#Mann=16,-1,0
  3922.0     0.1       0  4014.8    0.16       0  4134.5     0.1       0
  4135.6    0.05       0  4256.5    0.16       0  4304.5    0.05       0
  4618.9     0.1       0  4663.1    0.05       0  4850.3     0.1       0
  4999.3    0.07       0  5005.3     0.1       0  5066.1    0.05       0
  5357.5     0.1       0  5505.6    0.05       0  5798.9     0.1       0
  6086.0    0.05       0
Bank Sta=4999.3,5005.3
Exp/Cntr=0.3,0.1

Type RM Length L Ch R = 1,5558,605,605,605
BEGIN DESCRIPTION:
CLEVELAND BRANCH 12.0
END DESCRIPTION:
XS GIS Cut Line= 4
      2948239.45     10117675.72      2947775.02     10117015.97
      2947427.80     10116777.25      2946277.64     10116660.07
#Sta/Elev= 30
  4006.5 1078.02  4063.1 1074.79  4187.1 1070.96  4280.8 1067.04  4625.7 1056.79
  4669.3 1054.53  4799.0 1051.35  4806.8 1051.21  4892.4 1051.37  4919.4 1049.80
  4942.6 1050.13  4979.0 1046.99  4996.9 1043.42  4999.7 1042.92  5002.9 1043.42
  5014.8 1044.47  5027.6 1047.57  5050.7 1051.10  5179.2 1050.65  5264.2 1051.78
  5435.1 1055.69  5513.3 1060.83  5555.7 1062.51  5683.0 1065.40  5756.7 1068.16
  5961.3 1071.53  6048.5 1073.57  6205.3 1078.89  6243.6 1079.01  6390.8 1082.62
#Mann=11,-1,0
  4006.5    0.05       0  4063.1    0.16       0  4187.1    0.05       0
  4799.0     0.1       0  4806.8    0.05       0  4996.9   0.035       0
  5002.9    0.05       0  5683.0     0.1       0  5961.3    0.05       0
  6048.5     0.1       0  6243.6    0.05       0
Bank Sta=4996.9,5002.9
Exp/Cntr=0.3,0.1

Type RM Length L Ch R = 1,4953,650,650,650
BEGIN DESCRIPTION:
CLEVELAND BRANCH 10.0
END DESCRIPTION:
XS GIS Cut Line= 4
      2948712.49     10116981.23      2947896.55     10116338.89
      2947492.90     10116338.89      2946452.33     10116494.97
#Sta/Elev= 30
  3823.0 1074.89  3959.1 1070.41  4114.1 1066.66  4190.8 1064.65  4235.6 1063.69
  4358.0 1060.65  4542.8 1055.11  4693.6 1052.76  4749.7 1051.05  4799.4 1048.00
  4843.3 1046.99  4949.5 1045.40  4979.5 1041.82  5006.5 1041.11  5009.3 1040.61
  5012.5 1041.11  5029.5 1045.12  5039.5 1045.67  5109.5 1044.96  5136.0 1045.56
  5189.5 1047.08  5209.5 1046.46  5390.9 1049.04  5668.8 1055.50  5732.8 1056.05
  5846.0 1060.10  5935.0 1061.75  6202.6 1071.15  6225.5 1072.27  6317.3 1073.96
#Mann=11,-1,0
  3823.0     0.1       0  4114.1    0.05       0  4190.8     0.1       0
  4235.6    0.16       0  4358.0    0.05       0  4843.3    0.16       0
  5006.5    0.07       0  5012.5    0.16       0  5136.0    0.05       0
  6202.6     0.1       0  6225.5    0.05       0
Bank Sta=5006.5,5012.5
Exp/Cntr=0.3,0.1

Type RM Length L Ch R = 1,4303,360,360,360
BEGIN DESCRIPTION:
CLEVELAND BRANCH 9.0
END DESCRIPTION:
XS GIS Cut Line= 4
      2948599.68     10116586.29      2948261.13     10116243.40
      2947944.29     10115640.10      2947275.90     10115349.31
#Sta/Elev= 30
  4086.9 1061.62  4124.9 1061.27  4322.9 1054.69  4563.4 1049.74  4645.8 1045.94
  4668.7 1045.79  4782.3 1042.65  4866.3 1040.54  4895.9 1038.76  4963.7 1038.35
  4976.5 1037.83  4989.9 1035.72  4992.7 1035.22  4995.9 1035.72  5008.9 1036.30
  5020.6 1038.54  5037.0 1039.73  5064.4 1039.34  5191.4 1038.07  5235.1 1036.56
  5281.3 1036.65  5555.4 1046.12  5568.7 1047.48  5616.4 1050.21  5658.2 1050.60
  5725.0 1051.38  5800.7 1054.44  5845.4 1054.80  5947.0 1059.14  5979.1 1060.13
#Mann=11,-1,0
  4086.9    0.05       0  4668.7     0.1       0  4782.3    0.05       0
  4895.9     0.1       0  4989.9    0.07       0  4995.9     0.1       0
  5064.4    0.05       0  5235.1     0.1       0  5568.7    0.05       0
  5658.2     0.1       0  5947.0    0.05       0
Bank Sta=4989.9,4995.9
Exp/Cntr=0.3,0.1

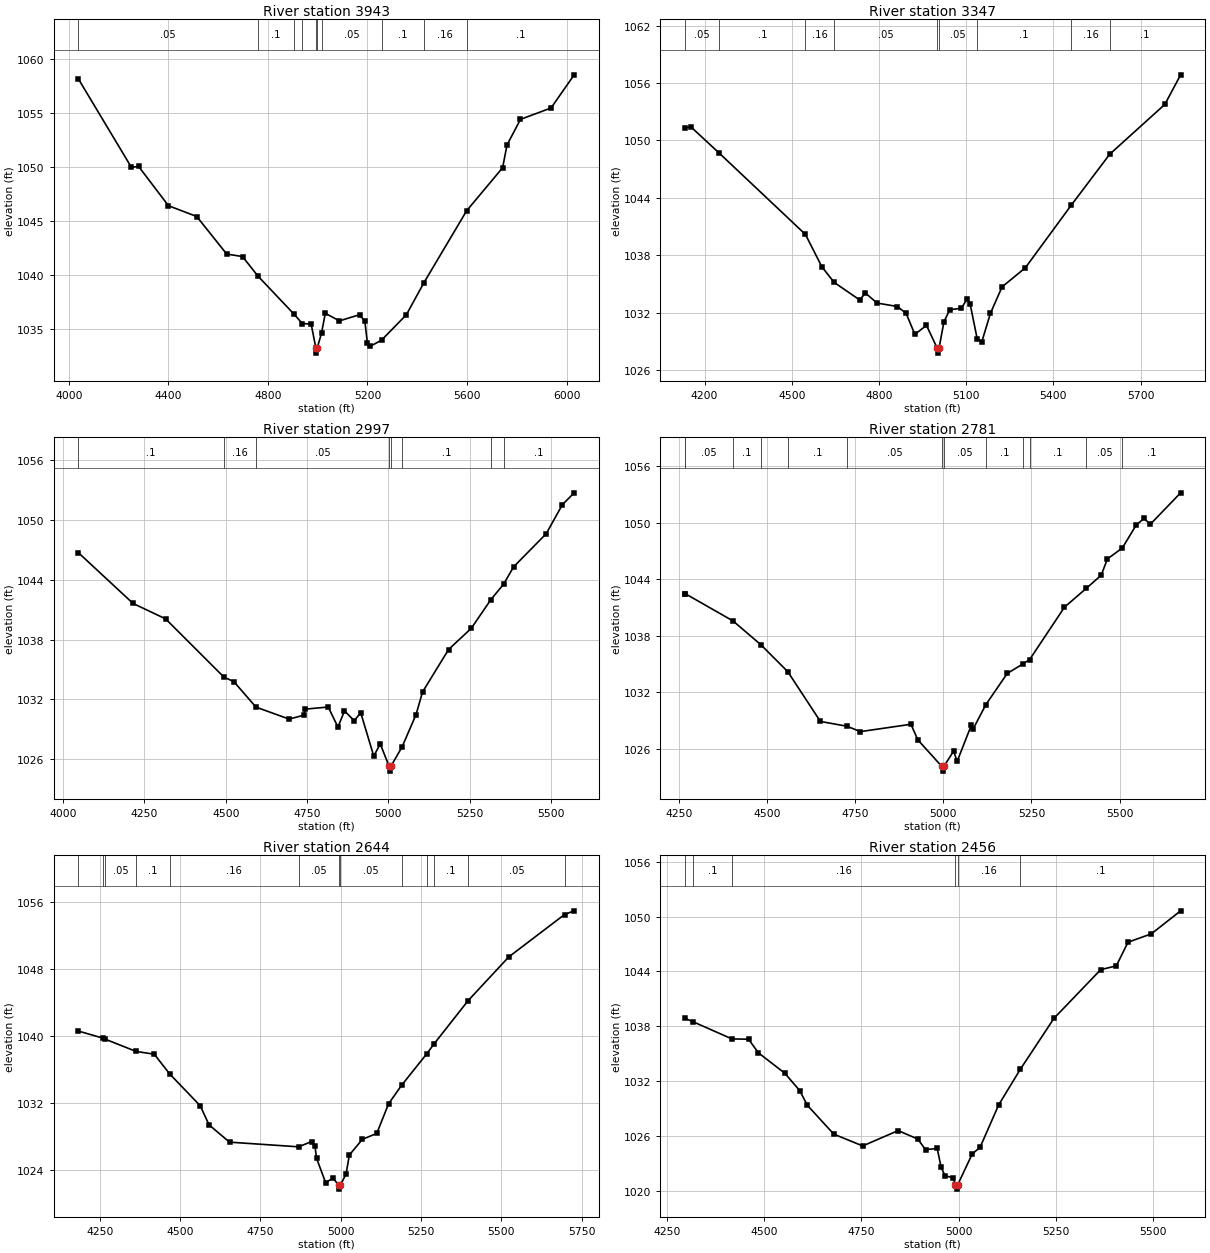
Type RM Length L Ch R = 1,3943,596,596,596
BEGIN DESCRIPTION:
CLEVELAND BRANCH 8.0
END DESCRIPTION:
XS GIS Cut Line= 3
      2948925.21     10116308.53      2948174.33     10115470.83
      2947327.98     10115279.86
#Sta/Elev= 30
  4038.1 1058.19  4251.6 1049.98  4280.0 1050.08  4400.4 1046.43  4514.0 1045.43
  4634.4 1041.95  4697.9 1041.72  4759.5 1039.92  4905.0 1036.38  4938.6 1035.50
  4973.7 1035.48  4992.4 1033.27  4995.2 1032.77  4998.4 1033.27  5015.4 1034.62
  5030.6 1036.46  5087.4 1035.76  5168.3 1036.33  5189.6 1035.71  5199.8 1033.70
  5210.1 1033.39  5256.5 1033.97  5356.5 1036.33  5427.3 1039.31  5598.8 1045.97
  5743.2 1049.95  5760.9 1052.06  5814.9 1054.43  5937.9 1055.49  6030.7 1058.56
#Mann=10,-1,0
  4038.1    0.05       0  4759.5     0.1       0  4905.0    0.05       0
  4938.6     0.1       0  4992.4    0.07       0  4998.4     0.1       0
  5015.4    0.05       0  5256.5     0.1       0  5427.3    0.16       0
  5598.8     0.1       0
Bank Sta=4992.4,4998.4
Exp/Cntr=0.3,0.1

Type RM Length L Ch R = 1,3347,350,350,350
BEGIN DESCRIPTION:
CLEVELAND BRANCH 7.0
END DESCRIPTION:
XS GIS Cut Line= 2
      2949169.96     10115066.46      2947464.16     10115066.46
#Sta/Elev= 30
  4131.8 1051.34  4153.3 1051.40  4250.7 1048.66  4546.8 1040.18  4603.3 1036.80
  4645.5 1035.17  4733.3 1033.34  4753.3 1034.05  4793.3 1033.01  4863.3 1032.65
  4893.3 1031.93  4923.3 1029.74  4963.3 1030.68  5000.3 1028.28  5003.0 1027.78
  5006.3 1028.28  5023.3 1031.04  5043.3 1032.32  5083.3 1032.46  5103.3 1033.46
  5113.3 1032.93  5138.1 1029.22  5153.3 1028.93  5183.3 1031.94  5223.3 1034.70
  5303.3 1036.69  5461.0 1043.22  5593.8 1048.56  5783.3 1053.76  5837.6 1056.85
#Mann=9,-1,0
  4131.8    0.05       0  4250.7     0.1       0  4546.8    0.16       0
  4645.5    0.05       0  5000.3   0.035       0  5006.3    0.05       0
  5138.1     0.1       0  5461.0    0.16       0  5593.8     0.1       0
Bank Sta=5000.3,5006.3
Exp/Cntr=0.3,0.1

Type RM Length L Ch R = 1,2997,216,216,216
BEGIN DESCRIPTION:
Mapping XS f504e1f5
END DESCRIPTION:
XS GIS Cut Line= 2
      2949216.77     10114735.62      2947692.34     10114720.44
#Sta/Elev= 30
  4046.8 1046.70  4215.1 1041.61  4315.1 1040.07  4494.3 1034.24  4525.1 1033.78
  4593.0 1031.23  4695.1 1030.03  4739.4 1030.42  4745.1 1031.03  4815.1 1031.24
  4845.1 1029.23  4865.1 1030.85  4895.1 1029.87  4915.1 1030.67  4955.1 1026.32
  4975.1 1027.55  5002.1 1025.32  5004.9 1024.82  5008.1 1025.32  5042.6 1027.27
  5085.2 1030.49  5105.2 1032.75  5185.2 1037.00  5255.2 1039.13  5315.3 1042.00
  5354.1 1043.53  5385.2 1045.28  5485.2 1048.59  5535.2 1051.51  5571.3 1052.69
#Mann=8,-1,0
  4046.8     0.1       0  4494.3    0.16       0  4593.0    0.05       0
  5002.1   0.035       0  5008.1    0.05       0  5042.6     0.1       0
  5315.3    0.05       0  5354.1     0.1       0
Bank Sta=5002.1,5008.1
Exp/Cntr=0.3,0.1

Type RM Length L Ch R = 1,2781,137,137,137
BEGIN DESCRIPTION:
CLEVELAND BRANCH 6.0
END DESCRIPTION:
XS GIS Cut Line= 3
      2949081.47     10114383.15      2948568.42     10114510.76
      2947703.82     10114656.60
#Sta/Elev= 30
  4267.5 1042.45  4268.9 1042.45  4404.6 1039.55  4483.6 1037.02  4559.4 1034.18
  4651.9 1028.90  4727.5 1028.39  4765.2 1027.82  4908.5 1028.60  4928.0 1026.95
  4996.0 1024.13  4998.7 1023.63  5002.0 1024.13  5029.5 1025.76  5039.5 1024.66
  5079.8 1028.51  5084.9 1028.11  5121.0 1030.69  5181.5 1033.99  5227.2 1035.03
  5244.9 1035.46  5343.8 1041.02  5406.0 1043.03  5447.8 1044.41  5465.5 1046.14
  5507.6 1047.29  5546.6 1049.70  5568.8 1050.43  5587.2 1049.82  5673.0 1053.15
#Mann=13,-1,0
  4267.5     0.1       0  4268.9    0.05       0  4404.6     0.1       0
  4483.6    0.05       0  4559.4     0.1       0  4727.5    0.05       0
  4996.0   0.035       0  5002.0    0.05       0  5121.0     0.1       0
  5227.2    0.05       0  5244.9     0.1       0  5406.0    0.05       0
  5507.6     0.1       0
Bank Sta=4996,5002
Exp/Cntr=0.3,0.1

Type RM Length L Ch R = 1,2644,188,188,188
BEGIN DESCRIPTION:
CLEVELAND BRANCH 4.0
END DESCRIPTION:
XS GIS Cut Line= 3
      2949159.57     10114200.86      2948453.84     10114411.80
      2947661.51     10114567.67
#Sta/Elev= 30
  4182.9 1040.62  4258.7 1039.78  4267.5 1039.63  4363.0 1038.18  4419.4 1037.85
  4467.4 1035.49  4562.3 1031.69  4590.2 1029.39  4653.7 1027.33  4868.9 1026.77
  4909.1 1027.40  4919.5 1026.90  4925.0 1025.38  4952.9 1022.49  4975.9 1023.02
  4993.3 1022.21  4996.1 1021.71  4999.3 1022.21  5016.7 1023.53  5026.9 1025.79
  5067.6 1027.67  5112.2 1028.37  5149.2 1031.93  5190.0 1034.15  5268.2 1037.91
  5289.4 1039.02  5396.8 1044.26  5523.2 1049.48  5697.1 1054.56  5727.0 1055.00
#Mann=13,-1,0
  4182.9    0.05       0  4258.7     0.1       0  4267.5    0.05       0
  4363.0     0.1       0  4467.4    0.16       0  4868.9    0.05       0
  4993.3   0.035       0  4999.3    0.05       0  5190.0     0.1       0
  5268.2    0.05       0  5289.4     0.1       0  5396.8    0.05       0
  5697.1     0.1       0
Bank Sta=4993.3,4999.3
Exp/Cntr=0.3,0.1

Type RM Length L Ch R = 1,2456,328,328,328
BEGIN DESCRIPTION:
Mapping XS a2ba2950
END DESCRIPTION:
XS GIS Cut Line= 3
      2949110.43     10114149.69      2948537.54     10114238.66
      2947843.26     10114269.03
#Sta/Elev= 30
  4296.3 1038.87  4317.0 1038.50  4417.6 1036.61  4460.2 1036.58  4485.5 1035.09
  4553.5 1032.85  4591.8 1030.95  4611.4 1029.34  4679.4 1026.18  4753.7 1024.89
  4844.8 1026.57  4895.1 1025.65  4915.2 1024.49  4945.2 1024.61  4955.2 1022.57
  4965.2 1021.62  4985.2 1021.42  4992.2 1020.66  4995.0 1020.16  4998.2 1020.66
  5035.3 1024.02  5055.3 1024.73  5103.4 1029.40  5159.1 1033.30  5245.5 1038.87
  5365.6 1044.20  5405.6 1044.61  5435.7 1047.20  5495.7 1048.12  5571.0 1050.64
#Mann=6,-1,0
  4296.3    0.05       0  4317.0     0.1       0  4417.6    0.16       0
  4992.2    0.07       0  4998.2    0.16       0  5159.1     0.1       0
Bank Sta=4992.2,4998.2
Exp/Cntr=0.3,0.1

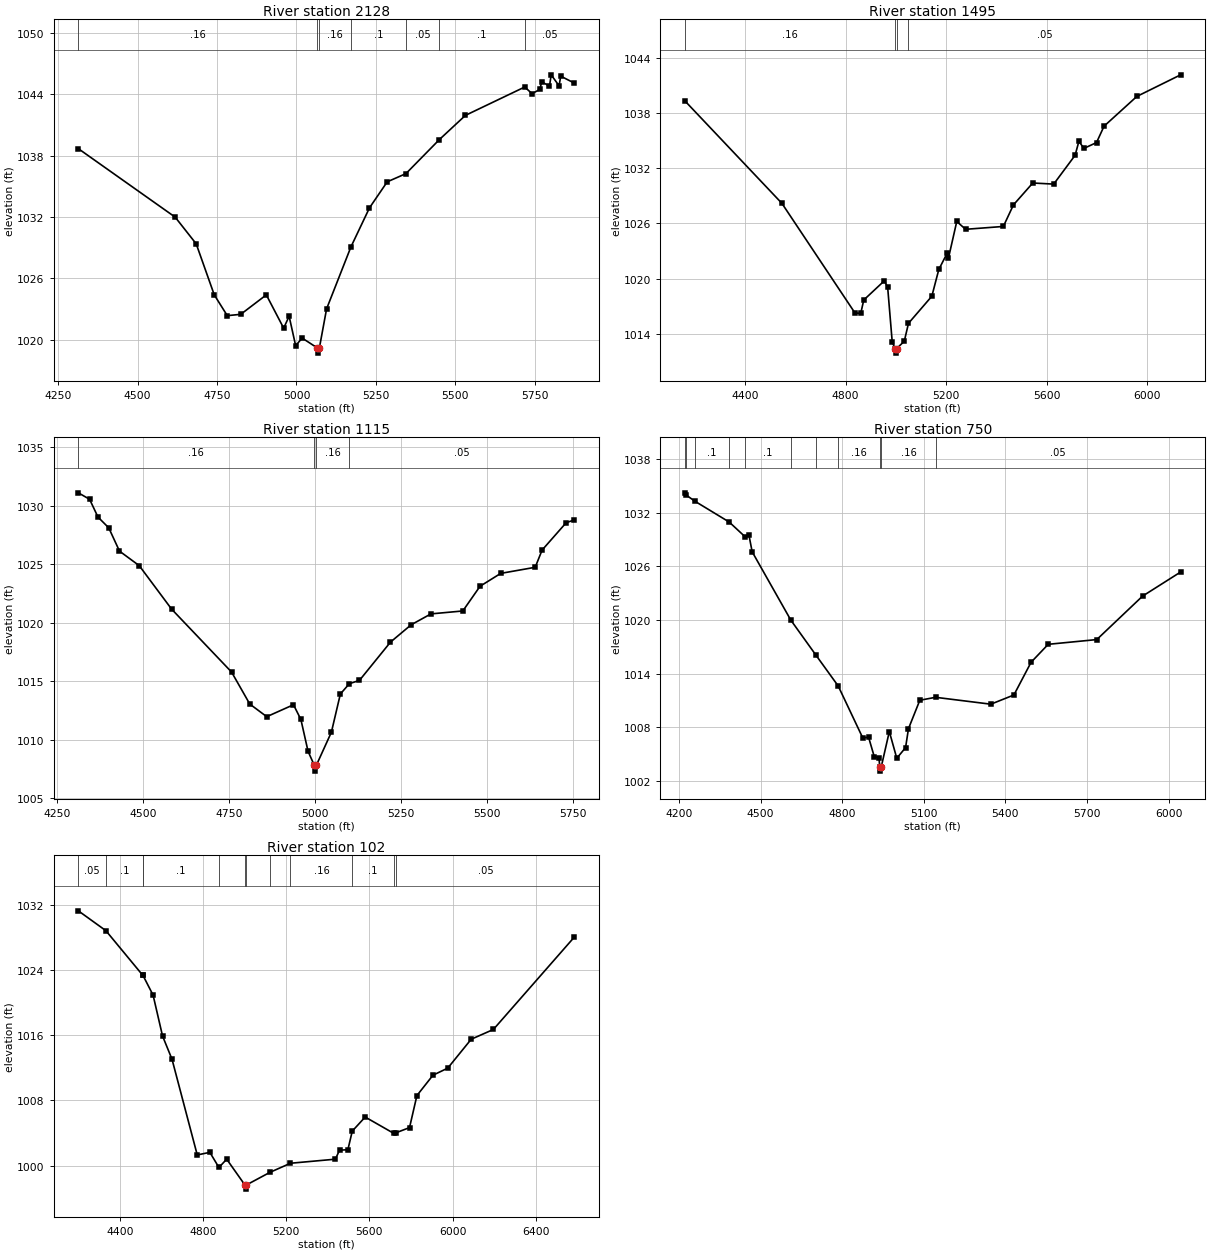
Type RM Length L Ch R = 1,2128,633,633,633
BEGIN DESCRIPTION:
CLEVELAND BRANCH 5.0
END DESCRIPTION:
XS GIS Cut Line= 3
      2949195.95     10114089.89      2948279.31     10113884.17
      2947698.60     10114105.52
#Sta/Elev= 30
  4313.3 1038.68  4618.2 1031.99  4684.4 1029.38  4741.2 1024.40  4782.2 1022.37
  4824.6 1022.50  4905.1 1024.40  4959.7 1021.15  4976.9 1022.31  4997.4 1019.44
  5017.9 1020.18  5066.1 1019.21  5068.9 1018.71  5072.1 1019.21  5094.8 1023.03
  5171.4 1029.08  5229.9 1032.90  5285.7 1035.44  5344.6 1036.24  5450.0 1039.57
  5531.9 1041.93  5718.6 1044.70  5741.7 1044.05  5766.4 1044.47  5771.8 1045.21
  5796.5 1044.79  5801.9 1045.89  5826.6 1044.82  5832.0 1045.76  5874.2 1045.09
#Mann=7,-1,0
  4313.3    0.16       0  5066.1    0.07       0  5072.1    0.16       0
  5171.4     0.1       0  5344.6    0.05       0  5450.0     0.1       0
  5718.6    0.05       0
Bank Sta=5066.1,5072.1
Exp/Cntr=0.3,0.1

Type RM Length L Ch R = 1,1495,380,380,380
BEGIN DESCRIPTION:
CLEVELAND BRANCH 3.0
END DESCRIPTION:
XS GIS Cut Line= 4
      2949253.33     10114086.30      2948883.53     10113461.28
      2948518.94     10113351.91      2947654.37     10113403.99
#Sta/Elev= 30
  4160.3 1039.31  4546.7 1028.17  4837.2 1016.27  4860.4 1016.21  4872.4 1017.67
  4954.4 1019.76  4967.6 1019.03  4985.8 1013.07  4997.6 1012.40  5000.4 1011.90
  5003.6 1012.40  5033.7 1013.20  5050.4 1015.14  5143.3 1018.08  5171.1 1020.99
  5204.2 1022.75  5209.4 1022.21  5242.5 1026.20  5277.7 1025.35  5427.9 1025.66
  5468.0 1028.00  5545.0 1030.38  5628.3 1030.26  5713.4 1033.39  5728.5 1034.91
  5748.5 1034.14  5798.6 1034.77  5828.6 1036.55  5958.9 1039.78  6133.3 1042.13
#Mann=4,-1,0
  4160.3    0.16       0  4997.6    0.07       0  5003.6    0.16       0
  5050.4    0.05       0
Bank Sta=4997.6,5003.6
Exp/Cntr=0.3,0.1

Type RM Length L Ch R = 1,1115,365,365,365
BEGIN DESCRIPTION:
CLEVELAND BRANCH 2.0
END DESCRIPTION:
XS GIS Cut Line= 3
      2949201.24     10113794.63      2948940.82     10113034.20
      2948305.40     10113018.57
#Sta/Elev= 30
  4313.0 1031.10  4345.7 1030.55  4370.0 1029.03  4401.3 1028.11  4432.5 1026.12
  4489.8 1024.88  4583.7 1021.17  4757.9 1015.79  4810.7 1013.06  4860.0 1011.98
  4937.6 1013.00  4959.1 1011.74  4979.9 1009.02  4998.0 1007.83  5000.8 1007.33
  5004.0 1007.83  5047.7 1010.66  5073.7 1013.92  5099.9 1014.80  5129.1 1015.08
  5219.2 1018.35  5279.2 1019.83  5336.7 1020.76  5429.2 1021.01  5479.2 1023.12
  5539.3 1024.22  5639.3 1024.74  5659.3 1026.21  5729.3 1028.55  5752.4 1028.78
#Mann=4,-1,0
  4313.0    0.16       0  4998.0    0.07       0  5004.0    0.16       0
  5099.9    0.05       0
Bank Sta=4998,5004
Exp/Cntr=0.3,0.1

Type RM Length L Ch R = 1,750,648,648,648
BEGIN DESCRIPTION:
Mapping XS f97bcae4
END DESCRIPTION:
XS GIS Cut Line= 4
      2949505.81     10113688.83      2949244.42     10112846.96
      2948996.60     10112721.35      2948365.19     10112925.04
#Sta/Elev= 30
  4221.7 1034.23  4225.8 1034.00  4259.4 1033.28  4385.0 1030.96  4444.2 1029.29
  4457.4 1029.51  4469.4 1027.63  4611.4 1019.99  4704.7 1016.03  4785.6 1012.62
  4876.2 1006.79  4897.2 1006.90  4918.1 1004.72  4935.8 1004.55  4938.1 1003.59
  4940.8 1003.09  4944.1 1003.59  4973.6 1007.52  5001.0 1004.53  5033.3 1005.72
  5044.0 1007.84  5085.7 1011.02  5143.6 1011.35  5346.8 1010.58  5431.6 1011.61
  5494.7 1015.27  5557.7 1017.28  5736.3 1017.81  5904.5 1022.67  6044.5 1025.37
#Mann=11,-1,0
  4221.7    0.05       0  4225.8    0.16       0  4259.4     0.1       0
  4385.0    0.16       0  4444.2     0.1       0  4611.4    0.05       0
  4704.7     0.1       0  4785.6    0.16       0  4938.1    0.07       0
  4944.1    0.16       0  5143.6    0.05       0
Bank Sta=4938.1,4944.1
Exp/Cntr=0.3,0.1

Type RM Length L Ch R = 1,102,0,0,0
BEGIN DESCRIPTION:
CLEVELAND BRANCH 1.0
END DESCRIPTION:
XS GIS Cut Line= 4
      2949852.08     10113349.37      2949729.87     10112514.27
      2949064.50     10112544.83      2948256.57     10112877.50
#Sta/Elev= 30
  4201.0 1031.30  4333.5 1028.86  4511.0 1023.37  4511.9 1023.36  4560.4 1020.94
  4605.8 1015.92  4651.4 1013.06  4772.7 1001.30  4833.3 1001.62  4876.9  999.76
  4914.2 1000.78  5002.1  997.60  5004.9  997.10  5008.1  997.60  5122.0  999.16
  5221.0 1000.28  5436.8 1000.78  5456.8 1001.89  5496.9 1001.94  5518.0 1004.23
  5580.1 1005.96  5716.4 1003.97  5730.6 1004.05  5793.3 1004.66  5828.8 1008.60
  5906.0 1011.10  5977.1 1011.97  6089.8 1015.52  6196.4 1016.72  6584.8 1028.05
#Mann=12,-1,0
  4201.0    0.05       0  4333.5     0.1       0  4511.0    0.05       0
  4511.9     0.1       0  4876.9    0.16       0  5002.1    0.07       0
  5008.1    0.16       0  5122.0     0.1       0  5221.0    0.16       0
  5518.0     0.1       0  5716.4    0.16       0  5730.6    0.05       0
Bank Sta=5002.1,5008.1
Exp/Cntr=0.3,0.1

Chan Stop Cuts=-1