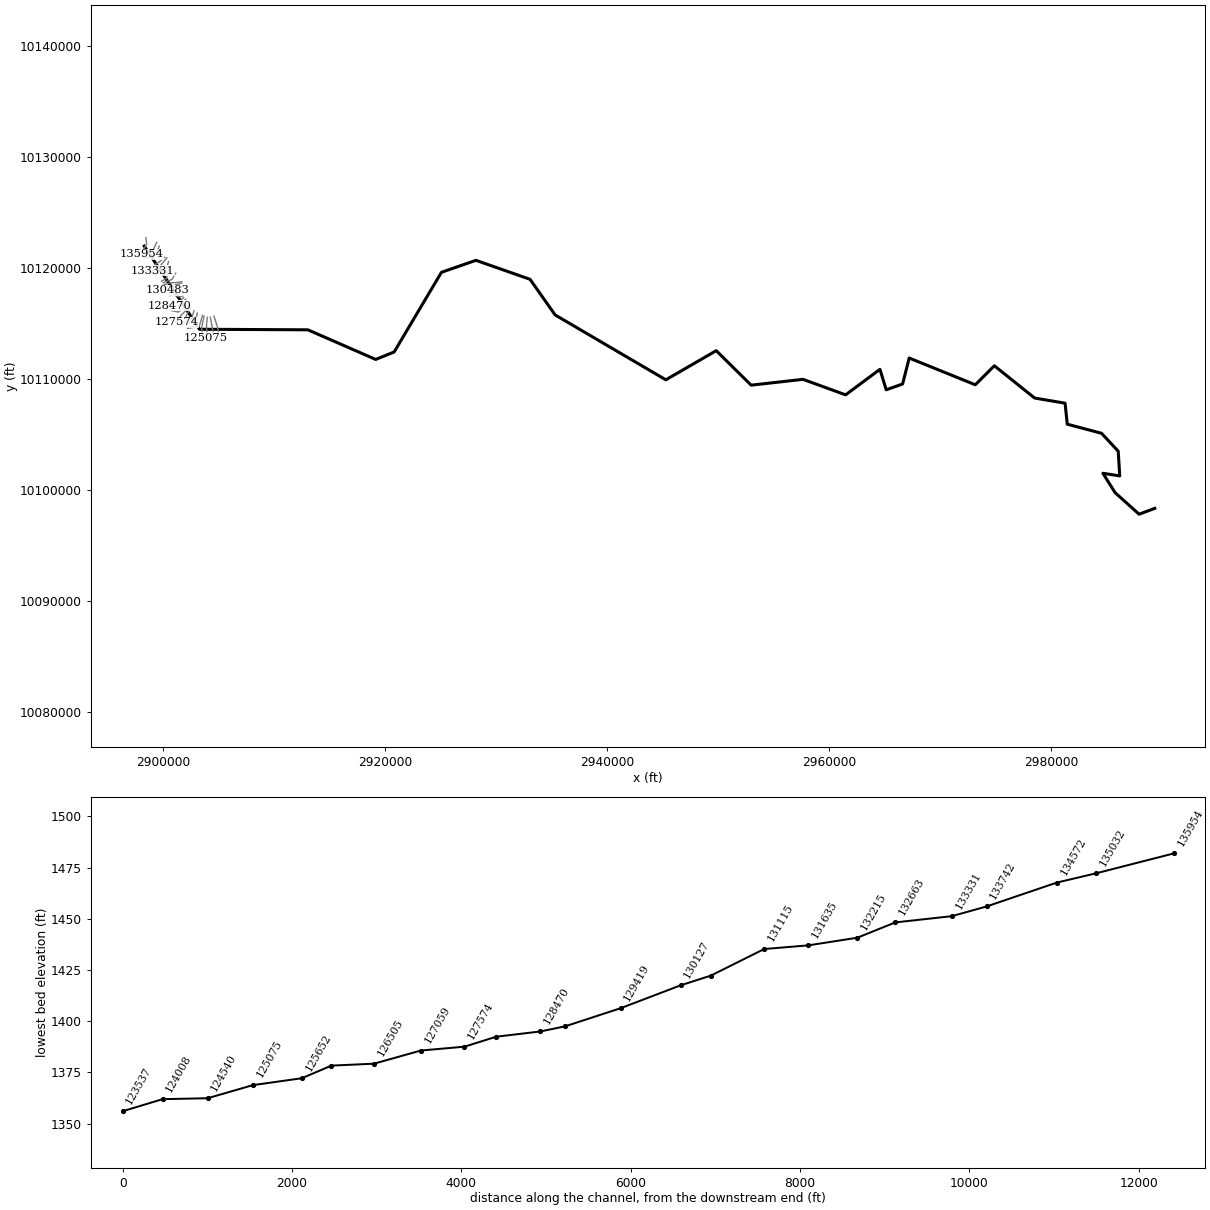
--- CYPRESS CREEK.prj (project) ---

Proj Title=CYPRESS CREEK Base Level Engineering
Current Plan=p01
Default Exp/Contr=0.3,0.1
English Units
Geom File=g01
Flow File=f01
Plan File=p01
Y Axis Title=Elevation
X Axis Title(PF)=Main Channel Distance
X Axis Title(XS)=Station
BEGIN DESCRIPTION:
CYPRESS CREEK
END DESCRIPTION:
DSS Export Rating Curves= 0
DSS Export Rating Curve Sorted= 0
DSS Export Volume Flow Curves= 0
DXF OffsetX= 0
DXF OffsetY= 0
DXF ScaleX= 1
DXF ScaleY= 10

--- CYPRESS CREEK.p01 (plan) ---

Plan Title=Multiple Run
Short Identifier=Multiple
Geom File=g01
Flow File=f01
Subcritical Flow
K Sum by GR= 0
Std Step Tol= 0.01
Critical Tol= 0.01
Num of Std Step Trials= 20
Max Error Tol= 0.3
Flow Tol Ratio= 0.001
Split Flow NTrial= 30
Split Flow Tol= 0.02
Split Flow Ratio= 0.02
Log Output Level= 0
Friction Slope Method= 1
Unsteady Friction Slope Method= 2
Unsteady Bridges Friction Slope Method= 1
Parabolic Critical Depth
Global Vel Dist=  1 , 1 , 1
Global Log Level= 0
CheckData=True
Encroach Param= -1, 0, 0, 0
BEGIN DESCRIPTION:
Multiple Run
END DESCRIPTION:

--- CYPRESS CREEK.f01 (steady flow) ---

Flow Title=Multiple
Program Version=4.10
Number of Profiles= 7
Profile Names=10-year,25-year,50-year,1pct_min,100-year,1pct_plu,500-year
River Rch & RM=CYPRESS CREEK,Reach-1         ,135954
     982    1442    1846    1731    2341    3166    3780
River Rch & RM=CYPRESS CREEK,Reach-1         ,135032
    1468    2190    2832    2676    3619    4895    5939
River Rch & RM=CYPRESS CREEK,Reach-1         ,127574
    2325    3543    4649    4450    6018    8138   10138
River Rch & RM=CYPRESS CREEK,Reach-1         ,127059
    2325    3543    4649    4450    6018    8138   10138
River Rch & RM=CYPRESS CREEK,Reach-1         ,125075
    2881    4418    5822    5592    7562   10227   12826
River Rch & RM=CYPRESS CREEK,Reach-1         ,119989
    3368    5187    6853    6596    8921   12064   15198
River Rch & RM=CYPRESS CREEK,Reach-1         ,116422
    3530    5435    7180    6909    9343   12636   15905
River Rch & RM=CYPRESS CREEK,Reach-1         ,112876
    3610    5553    7330    7046    9529   12887   16188
River Rch & RM=CYPRESS CREEK,Reach-1         ,108870
    4462    6911    9167    8848   11967   16183   20499
River Rch & RM=CYPRESS CREEK,Reach-1         ,108028
    4462    6911    9167    8848   11967   16183   20499
River Rch & RM=CYPRESS CREEK,Reach-1         ,105350
    4663    7226    9585    9253   12514   16924   21438
River Rch & RM=CYPRESS CREEK,Reach-1         ,101213
    4793    7428    9856    9514   12867   17401   22043
River Rch & RM=CYPRESS CREEK,Reach-1         ,98325
    4949    7674   10187    9838   13305   17993   22809
River Rch & RM=CYPRESS CREEK,Reach-1         ,95231
    5278    8204   10907   10549   14266   19293   24528
River Rch & RM=CYPRESS CREEK,Reach-1         ,93759
    7096   11128   14886   14477   19578   26477   34029
River Rch & RM=CYPRESS CREEK,Reach-1         ,87011
    7654   12020   16096   15667   21188   28654   36886
River Rch & RM=CYPRESS CREEK,Reach-1         ,82232
    8150   12822   17192   16753   22656   30639   39530
River Rch & RM=CYPRESS CREEK,Reach-1         ,81748
    8284   13026   17458   17005   22997   31101   40088
River Rch & RM=CYPRESS CREEK,Reach-1         ,77633
    8386   13183   17666   17203   23265   31464   40538
River Rch & RM=CYPRESS CREEK,Reach-1         ,74439
    8934   14056   18846   18360   24830   33579   43294
River Rch & RM=CYPRESS CREEK,Reach-1         ,73826
    8934   14056   18846   18360   24830   33579   43294
River Rch & RM=CYPRESS CREEK,Reach-1         ,70022
    9107   14317   19187   18682   25265   34168   44003
River Rch & RM=CYPRESS CREEK,Reach-1         ,69302
    9107   14317   19187   18682   25265   34168   44003
River Rch & RM=CYPRESS CREEK,Reach-1         ,64360
    9681   15241   20446   19926   26948   36443   47013
River Rch & RM=CYPRESS CREEK,Reach-1         ,63844
    9681   15241   20446   19926   26948   36443   47013
River Rch & RM=CYPRESS CREEK,Reach-1         ,60332
    9873   15545   20856   20326   27488   37175   47959
River Rch & RM=CYPRESS CREEK,Reach-1         ,58004
   10178   16030   21511   20968   28357   38350   49490
River Rch & RM=CYPRESS CREEK,Reach-1         ,56818
   10178   16030   21511   20968   28357   38350   49490
River Rch & RM=CYPRESS CREEK,Reach-1         ,49093
   10297   16214   21757   21205   28678   38783   50035
River Rch & RM=CYPRESS CREEK,Reach-1         ,46253
   11267   17773   23879   23301   31512   42616   55100
River Rch & RM=CYPRESS CREEK,Reach-1         ,45624
   11267   17773   23879   23301   31512   42616   55100
River Rch & RM=CYPRESS CREEK,Reach-1         ,45050
   11382   17923   24051   23438   31698   42867   55276
River Rch & RM=CYPRESS CREEK,Reach-1         ,32688
   11988   18886   25353   24713   33422   45199   58309
River Rch & RM=CYPRESS CREEK,Reach-1         ,28838
   12537   19752   26520   25852   34962   47282   60995
River Rch & RM=CYPRESS CREEK,Reach-1         ,28278
   12537   19752   26520   25852   34962   47282   60995
River Rch & RM=CYPRESS CREEK,Reach-1         ,23319
   12676   19974   26819   26145   35358   47818   61693
River Rch & RM=CYPRESS CREEK,Reach-1         ,19565
   12718   20023   26870   26180   35406   47882   61702
River Rch & RM=CYPRESS CREEK,Reach-1         ,14239
   12814   20176   27077   26382   35679   48251   62180
River Rch & RM=CYPRESS CREEK,Reach-1         ,8580
   12805   20143   27016   26305   35575   48111   61917
Boundary for River Rch & Prof#=CYPRESS CREEK,Reach-1         , 1
Up Type= 0
Dn Type= 3
Dn Slope=0.004
Boundary for River Rch & Prof#=CYPRESS CREEK,Reach-1         , 2
Up Type= 0
Dn Type= 3
Dn Slope=0.004
Boundary for River Rch & Prof#=CYPRESS CREEK,Reach-1         , 3
Up Type= 0
Dn Type= 3
Dn Slope=0.004
Boundary for River Rch & Prof#=CYPRESS CREEK,Reach-1         , 4
Up Type= 0
Dn Type= 3
Dn Slope=0.004
Boundary for River Rch & Prof#=CYPRESS CREEK,Reach-1         , 5
Up Type= 0
Dn Type= 3
Dn Slope=0.004
Boundary for River Rch & Prof#=CYPRESS CREEK,Reach-1         , 6
Up Type= 0
Dn Type= 3
Dn Slope=0.004
Boundary for River Rch & Prof#=CYPRESS CREEK,Reach-1         , 7
Up Type= 0
Dn Type= 3
Dn Slope=0.004
DSS Import GetInterval= 0
DSS Import GetPeak= 0
DSS Import FillOption= 0

--- CYPRESS CREEK.g01 (geometry) ---

Geom Title=Existing Conditions
Program Version=4.10

River Reach=CYPRESS CREEK   ,Reach-1
Reach XY= 30
      2898308.47     10121943.73      2903289.69     10114452.83
        2913048.     10114402.69      2919159.46     10111733.62
      2920818.66     10112404.68       2925077.5     10119583.08
       2928181.4     10120663.78      2933058.47     10118953.73
      2935318.47     10115743.73        2945290.     10109897.55
      2949828.47     10112523.73      2952974.15     10109415.79
      2957647.32     10109940.54      2961480.47     10108542.96
      2964574.01     10110841.54      2965138.32     10108999.63
       2966614.9     10109521.74      2967209.14     10111860.03
      2973162.49     10109450.42      2974879.24     10111163.68
       2978505.4     10108256.79      2981248.81     10107792.57
      2981446.03      10105899.6      2984532.37     10105079.66
      2986035.32     10103467.86      2986171.64     10101240.52
      2984658.37     10101478.34      2985753.52     10099731.25
      2987915.62     10097790.16      2989327.79     10098315.64

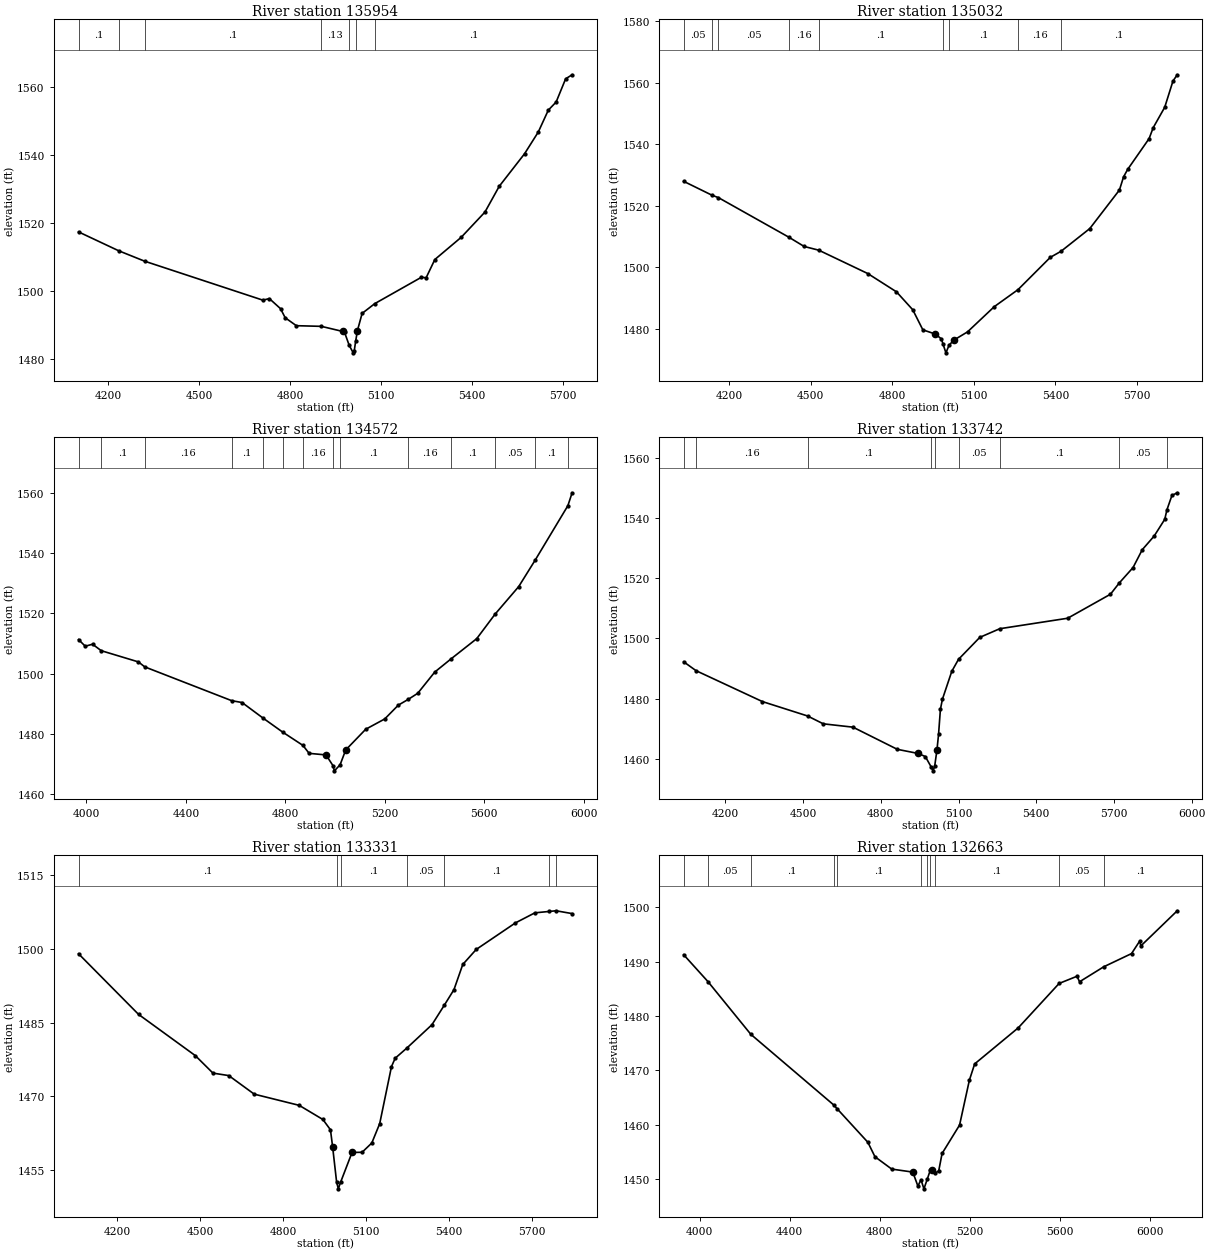
Type RM Length L Ch R = 1 ,135954  ,922,922,922
BEGIN DESCRIPTION:
CYPRESS CREEK 231.0
END DESCRIPTION:
XS GIS Cut Line= 4
      2898455.69     10122718.91      2898533.81      10122135.6
      2898210.89     10121604.35      2898091.09     10121203.27
#Sta/Elev= 30
  4101.5 1517.38  4233.9 1511.85  4319.6 1508.79  4709.8 1497.36  4731.2 1497.82
    4768 1494.87  4783.5  1492.2  4820.3 1489.87  4902.7 1489.68  4973.1 1488.19
  4979.2 1487.96  4994.7  1484.1  5007.9 1481.91  5011.2 1482.41    5016 1485.31
  5021.8 1488.42  5037.3 1493.48  5079.2 1496.35  5233.1 1504.08  5248.5 1503.92
  5277.3 1509.28  5364.5 1515.81  5442.6 1523.19  5489.8 1530.76  5573.3 1540.29
  5618.7 1546.68  5651.8  1553.1  5677.6 1555.47  5708.9 1562.28  5730.3 1563.46
#Mann= 7 ,-1 , 0
  4101.5      .1       0  4233.9     .05       0  4319.6      .1       0
  4902.7     .13       0  4994.7     .07       0    5016     .13       0
  5079.2      .1       0
Bank Sta=4973.1,5021.8
XS Rating Curve= 0 ,0
Exp/Cntr=0.3,0.1

Type RM Length L Ch R = 1 ,135032  ,460,460,460
BEGIN DESCRIPTION:
CYPRESS CREEK 229.0
END DESCRIPTION:
XS GIS Cut Line= 4
      2899440.04     10122291.82      2899096.31     10121557.47
      2898695.27     10121364.76      2898226.52     10121062.68
#Sta/Elev= 30
    4034 1527.96  4138.5 1523.42  4161.6 1522.66  4420.7 1509.77  4476.6 1506.77
  4530.5 1505.55  4710.5 1497.95  4815.8 1492.01  4875.7 1486.17  4912.8 1479.64
  4958.1 1478.29  4980.8 1476.71  4986.6 1475.09  4997.5 1472.16    5009 1474.62
    5026 1476.27  5076.9 1478.98  5175.3 1487.19  5262.4 1492.72  5381.1 1503.23
  5420.5  1505.2  5526.1 1512.59    5635 1525.13  5650.2 1529.42  5665.4 1531.86
  5743.9 1541.84  5759.1 1545.41  5801.4 1552.05  5831.7 1560.59  5847.4 1562.62
#Mann= 9 ,-1 , 0
    4034     .05       0  4138.5      .1       0  4161.6     .05       0
  4420.7     .16       0  4530.5      .1       0  4986.6     .07       0
    5009      .1       0  5262.4     .16       0  5420.5      .1       0
Bank Sta=4958.1,5026
XS Rating Curve= 0 ,0
Exp/Cntr=0.3,0.1

Type RM Length L Ch R = 1 ,134572  ,830,830,830
BEGIN DESCRIPTION:
CYPRESS CREEK 228.0
END DESCRIPTION:
XS GIS Cut Line= 4
      2899664.01     10121942.86      2899361.93     10121203.31
      2898929.64     10120974.14      2898248.38     10120828.53
#Sta/Elev= 30
  3968.2  1511.3  3995.2 1509.09  4024.6 1509.75  4059.5  1507.6    4209 1503.87
  4234.5 1502.22  4583.9 1490.99  4625.8 1490.37    4708 1485.33  4788.6 1480.57
  4870.6 1476.12  4895.5 1473.48  4963.4 1472.96    4991 1469.44  4997.1 1467.67
    5020 1469.68  5042.6 1474.61    5123 1481.49  5199.6 1484.92  5254.2 1489.51
  5294.8 1491.46  5332.2 1493.44  5400.7  1500.5  5465.6 1504.84  5569.4  1511.6
  5643.5 1519.77  5738.2  1528.9    5805 1537.77  5935.9 1555.78    5953 1560.08
#Mann= 14 ,-1 , 0
  3968.2     .05       0  4059.5      .1       0  4234.5     .16       0
  4583.9      .1       0    4708     .16       0  4788.6      .1       0
  4870.6     .16       0    4991     .07       0    5020      .1       0
  5294.8     .16       0  5465.6      .1       0  5643.5     .05       0
    5805      .1       0  5935.9     .05       0
Bank Sta=4963.4,5042.6
XS Rating Curve= 0 ,0
Exp/Cntr=0.3,0.1

Type RM Length L Ch R = 1 ,133742  ,411,411,411
BEGIN DESCRIPTION:
CYPRESS CREEK 226.0
END DESCRIPTION:
XS GIS Cut Line= 4
       2900158.8     10120942.88      2899690.06     10120541.85
      2899158.81     10120187.68      2898528.63     10120026.23
#Sta/Elev= 30
  4038.6 1492.21  4086.7 1489.25  4342.8    1479  4516.8 1474.23  4577.7 1471.62
  4692.3 1470.51  4863.6 1463.15  4944.7 1461.77  4971.7 1460.76  4993.9 1457.37
  5001.5 1456.01  5007.8 1457.51  5016.8 1463.04  5022.8 1468.09    5030 1476.44
  5037.8  1479.8  5073.9 1489.04  5099.9 1493.03  5182.1 1500.32  5259.2 1503.19
  5521.4 1506.67  5686.6 1514.64  5721.1 1518.43  5773.8 1523.49  5809.4 1529.42
  5855.4 1533.96  5896.2  1539.5  5904.8  1542.7    5924 1547.44  5944.5 1548.32
#Mann= 9 ,-1 , 0
  4038.6      .1       0  4086.7     .16       0  4516.8      .1       0
  4993.9     .07       0  5007.8      .1       0  5099.9     .05       0
  5259.2      .1       0  5721.1     .05       0  5904.8      .1       0
Bank Sta=4944.7,5016.8
XS Rating Curve= 0 ,0
Exp/Cntr=0.3,0.1

Type RM Length L Ch R = 1 ,133331  ,668,668,668
BEGIN DESCRIPTION:
CYPRESS CREEK 225.0
END DESCRIPTION:
XS GIS Cut Line= 3
      2900356.73     10120890.82      2899533.81     10119911.64
      2899054.63     10119744.97
#Sta/Elev= 30
  4059.6 1498.96  4276.8 1486.66  4482.3 1478.29  4546.1 1474.74  4603.3 1474.24
  4695.6 1470.47  4858.3  1468.2    4944 1465.33  4971.4 1463.24  4979.2 1459.79
  4993.5 1452.71  4999.8 1451.26  5007.8 1452.56  5049.5 1458.64  5085.9 1458.68
    5121 1460.56  5149.6 1464.49  5192.2 1476.06  5205.6 1477.76  5247.9 1479.83
  5338.7 1484.56  5383.3 1488.51  5418.4 1491.68  5450.2 1496.78  5498.8 1499.83
  5640.8 1505.22  5711.2 1507.26  5762.1 1507.54  5787.9 1507.68    5846 1507.11
#Mann= 7 ,-1 , 0
  4059.6      .1       0  4993.5     .07       0  5007.8      .1       0
  5247.9     .05       0  5383.3      .1       0  5762.1     .05       0
  5787.9      .1       0
Bank Sta=4979.2,5049.5
XS Rating Curve= 0 ,0
Exp/Cntr=0.3,0.1

Type RM Length L Ch R = 1 ,132663  ,448,448,448
BEGIN DESCRIPTION:
CYPRESS CREEK 224.0
END DESCRIPTION:
XS GIS Cut Line= 4
      2900502.56     10120552.26      2900226.52     10119708.51
      2899908.81     10119489.76       2898997.4     10119354.36
#Sta/Elev= 30
  3928.1 1491.25  4036.1 1486.31  4226.7 1476.62  4595.7 1463.62  4609.5 1462.98
  4747.2 1456.77  4778.8 1454.11  4853.4 1451.84    4947 1451.29  4969.7 1448.72
  4983.5 1449.89  4996.5 1448.21  5011.6 1450.01  5025.4 1451.72  5032.6 1451.73
  5047.1  1451.1  5062.4 1451.53  5077.2 1454.71    5155 1459.93  5198.8 1468.21
  5222.2 1471.18    5416 1477.81  5597.7 1485.97  5677.1 1487.29  5688.6 1486.28
    5796 1489.03  5919.7 1491.46  5956.1 1493.76  5961.2 1492.87    6123 1499.33
#Mann= 11 ,-1 , 0
  3928.1      .1       0  4036.1     .05       0  4226.7      .1       0
  4595.7     .16       0  4609.5      .1       0  4983.5     .07       0
  5011.6      .1       0  5025.4     .16       0  5047.1      .1       0
  5597.7     .05       0    5796      .1       0
Bank Sta=4947,5032.6
XS Rating Curve= 0 ,0
Exp/Cntr=0.3,0.1

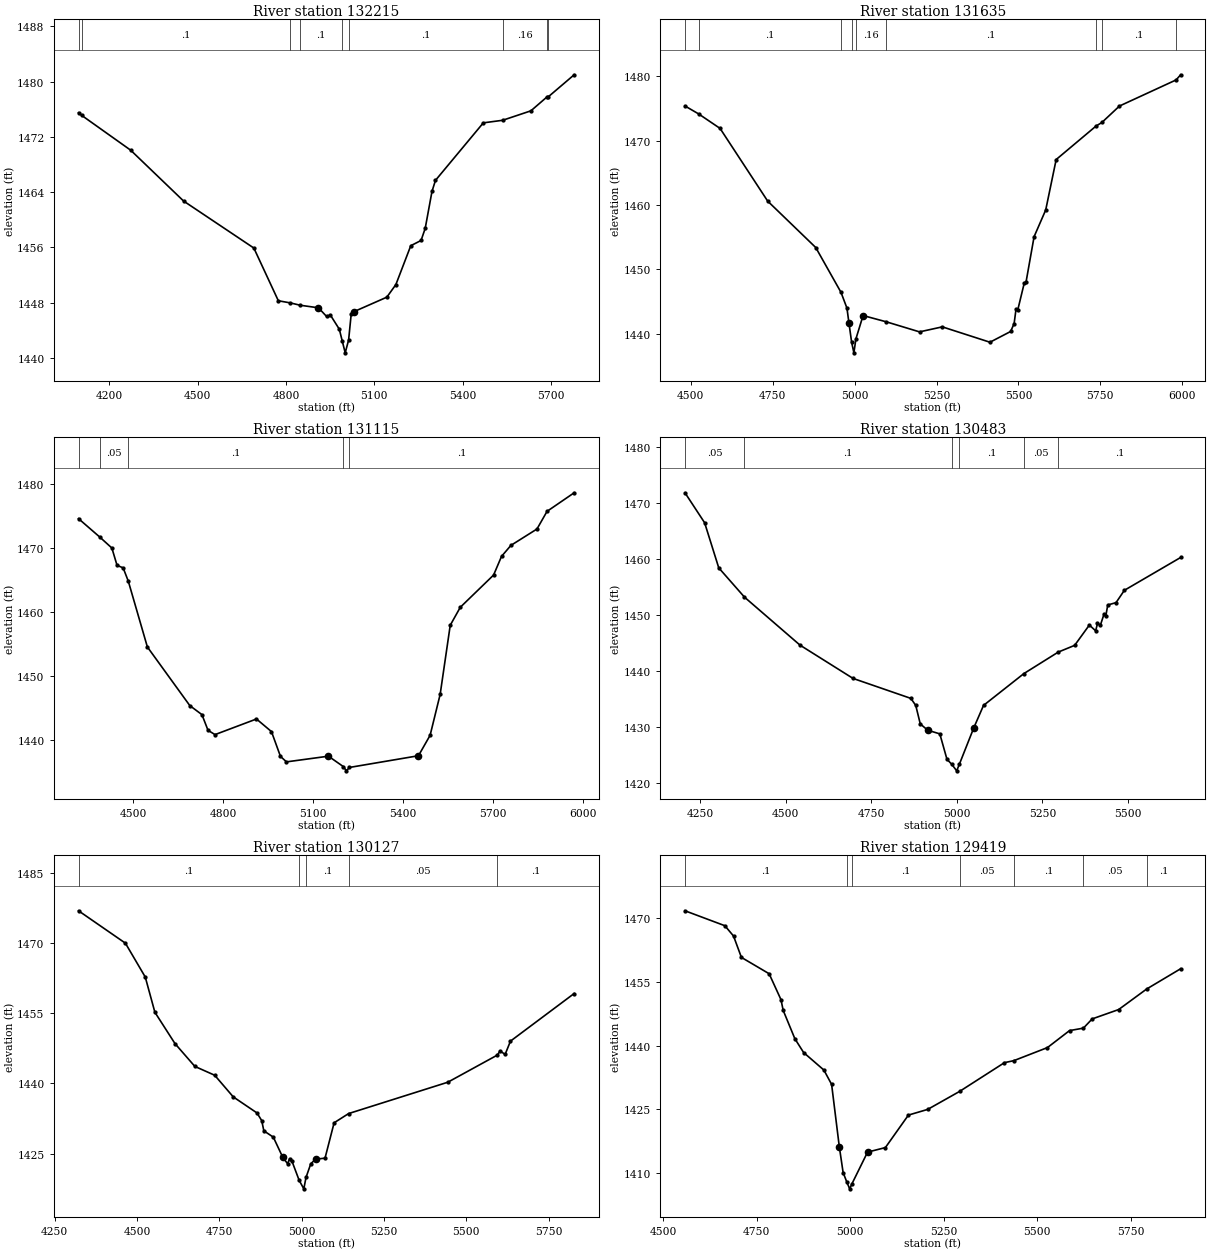
Type RM Length L Ch R = 1 ,132215  ,580,580,580
BEGIN DESCRIPTION:
CYPRESS CREEK 223.0
END DESCRIPTION:
XS GIS Cut Line= 4
      2900658.81     10120135.59      2900393.18     10119479.35
      2900330.68     10119052.26       2899862.7     10118776.67
#Sta/Elev= 30
  4095.8  1475.5    4107 1475.11  4272.9 1470.08  4452.5 1462.72  4691.1 1455.91
  4774.2 1448.28  4814.9 1447.97  4848.7 1447.63  4910.5 1447.26  4937.9 1446.01
  4950.9 1446.21  4981.2 1444.16  4991.4 1442.41  5001.2 1440.74  5012.8  1442.6
  5021.7 1446.42  5031.8 1446.72  5142.5  1448.8  5173.3 1450.63  5223.8 1456.25
  5258.7 1457.01  5272.8 1458.76  5295.8 1464.11  5307.6 1465.71  5470.1 1474.04
  5535.5 1474.41  5631.6 1475.78  5685.6 1477.77  5691.2 1477.83  5778.5    1481
#Mann= 9 ,-1 , 0
  4095.8     .05       0    4107      .1       0  4814.9     .16       0
  4848.7      .1       0  4991.4     .07       0  5012.8      .1       0
  5535.5     .16       0  5685.6      .1       0  5691.2     .05       0
Bank Sta=4910.5,5031.8
XS Rating Curve= 0 ,0
Exp/Cntr=0.3,0.1

Type RM Length L Ch R = 1 ,131635  ,520,520,520
BEGIN DESCRIPTION:
CYPRESS CREEK 221.0
END DESCRIPTION:
XS GIS Cut Line= 3
      2901148.39     10119510.59      2900809.85     10118942.89
      2900013.24     10118640.91
#Sta/Elev= 30
  4482.1 1475.39  4523.9 1474.15  4589.2  1471.9  4734.6 1460.59  4881.2 1453.38
  4958.3 1446.41  4976.5 1443.95  4982.4 1441.71  4990.7 1438.67  4997.7    1437
  5003.8 1439.16  5025.7  1442.8  5096.9 1441.82    5198 1440.26  5267.6 1441.04
    5413 1438.65  5476.1 1440.32  5486.8 1441.56  5492.7 1443.85  5498.1 1443.72
  5517.5 1447.81  5522.9 1447.94  5547.7 1455.06  5583.2 1459.22  5615.1 1467.06
  5737.1 1472.28  5754.6 1472.82  5808.3 1475.38  5981.2 1479.44    5995 1480.24
#Mann= 9 ,-1 , 0
  4482.1     .05       0  4523.9      .1       0  4958.3     .16       0
  4990.7     .07       0  5003.8     .16       0  5096.9      .1       0
  5737.1     .16       0  5754.6      .1       0  5981.2     .05       0
Bank Sta=4982.4,5025.7
XS Rating Curve= 0 ,0
Exp/Cntr=0.3,0.1

Type RM Length L Ch R = 1 ,131115  ,632,632,632
BEGIN DESCRIPTION:
CYPRESS CREEK 220.0
END DESCRIPTION:
XS GIS Cut Line= 4
      2901705.65     10118734.55      2901137.98     10118651.22
      2900731.73     10118651.22       2900085.9     10118463.72
#Sta/Elev= 30
  4317.2 1474.62  4387.4 1471.77  4428.4 1470.03  4445.7 1467.32    4466 1466.93
  4483.2 1464.85  4546.8 1454.57  4688.3 1445.41  4728.7    1444    4749 1441.55
  4772.3 1440.88  4910.5 1443.32  4960.5 1441.35  4990.5 1437.48  5010.5 1436.62
  5150.5 1437.51  5200.5 1435.87  5210.2 1435.22  5220.5 1435.75  5450.6 1437.58
  5489.4 1440.77  5522.9 1447.16  5556.5 1457.96    5590 1460.77  5701.1 1465.81
  5727.5 1468.72  5758.8 1470.44  5845.7    1473  5879.3 1475.76  5969.7 1478.66
#Mann= 5 ,-1 , 0
  4317.2      .1       0  4387.4     .05       0  4483.2      .1       0
  5200.5     .07       0  5220.5      .1       0
Bank Sta=5150.5,5450.6
XS Rating Curve= 0 ,0
Exp/Cntr=0.3,0.1

Type RM Length L Ch R = 1 ,130483  ,356,356,356
BEGIN DESCRIPTION:
CYPRESS CREEK 219.0
END DESCRIPTION:
XS GIS Cut Line= 4
      2901664.02     10118599.14      2901117.14     10118458.51
      2900825.48     10118104.35      2900430.42      10117948.4
#Sta/Elev= 30
  4205.9 1471.76  4263.3 1466.42  4304.6 1458.38  4379.8 1453.16    4542 1444.61
  4696.9 1438.68  4865.9 1435.12  4880.2 1433.86  4893.4 1430.57  4915.4 1429.44
  4950.5  1428.8  4971.3 1424.28  4985.7 1423.35  4999.8 1422.21  5007.9 1423.43
  5049.5 1429.84  5078.2 1433.87  5196.1 1439.54  5296.5 1443.37  5344.4 1444.57
  5387.4 1448.19  5405.8 1447.16  5411.2 1448.47  5419.7 1448.18  5430.2 1450.12
  5435.6 1449.86  5441.2 1451.77  5465.3 1452.18  5489.7 1454.38  5654.1 1460.23
#Mann= 6 ,-1 , 0
  4205.9     .05       0  4379.8      .1       0  4985.7     .07       0
  5007.9      .1       0  5196.1     .05       0  5296.5      .1       0
Bank Sta=4915.4,5049.5
XS Rating Curve= 0 ,0
Exp/Cntr=0.3,0.1

Type RM Length L Ch R = 1 ,130127  ,708,708,708
BEGIN DESCRIPTION:
CYPRESS CREEK 218.0
END DESCRIPTION:
XS GIS Cut Line= 4
      2901820.25      10118260.6      2901372.35     10118218.93
      2901106.73      10117885.6      2900509.35     10117688.21
#Sta/Elev= 30
  4322.7 1476.87  4465.1 1469.95  4525.4 1462.72  4554.6  1455.2  4615.7  1448.5
    4676 1443.63  4736.3 1441.74  4792.6 1437.12  4864.7 1433.69  4879.1 1432.05
  4885.5 1429.87  4914.3 1428.52  4943.1  1424.2  4957.6 1422.85  4963.9 1423.94
    4971 1423.37  4992.8 1419.29  5006.9 1417.48  5013.6 1419.92    5028 1422.82
  5042.4 1423.82  5071.3 1424.03  5098.9 1431.59  5143.1 1433.56  5444.1 1440.25
  5594.9 1446.06  5602.8 1446.94  5618.2 1446.19  5634.5 1449.03  5827.9  1459.2
#Mann= 5 ,-1 , 0
  4322.7      .1       0  4992.8     .07       0  5013.6      .1       0
  5143.1     .05       0  5594.9      .1       0
Bank Sta=4943.1,5042.4
XS Rating Curve= 0 ,0
Exp/Cntr=0.3,0.1

Type RM Length L Ch R = 1 ,129419  ,653,653,653
BEGIN DESCRIPTION:
CYPRESS CREEK 216.0
END DESCRIPTION:
XS GIS Cut Line= 4
      2901841.13     10117484.57      2901539.02     10117380.39
      2900898.39     10117531.43      2900554.68     10117479.35
#Sta/Elev= 30
  4558.3 1471.69  4664.9 1468.18  4688.1 1465.76  4709.2 1460.73  4783.3 1456.89
    4815  1450.8  4820.9 1448.28  4852.1 1441.62  4875.5 1438.37  4929.8 1434.24
  4950.4 1430.88  4970.9 1416.27  4981.2 1410.14  4991.5 1407.82  4998.7 1406.32
  5004.1 1407.38  5046.5 1414.95  5094.2 1416.02  5155.8 1423.66  5207.2 1424.99
  5292.4 1429.21  5412.7 1435.99  5437.5 1436.45  5527.6 1439.53  5586.6 1443.52
  5623.7  1444.1  5647.2 1446.27    5718 1448.47  5792.9  1453.3  5883.7 1458.06
#Mann= 7 ,-1 , 0
  4558.3      .1       0  4991.5     .07       0  5004.1      .1       0
  5292.4     .05       0  5437.5      .1       0  5623.7     .05       0
  5792.9      .1       0
Bank Sta=4970.9,5046.5
XS Rating Curve= 0 ,0
Exp/Cntr=0.3,0.1

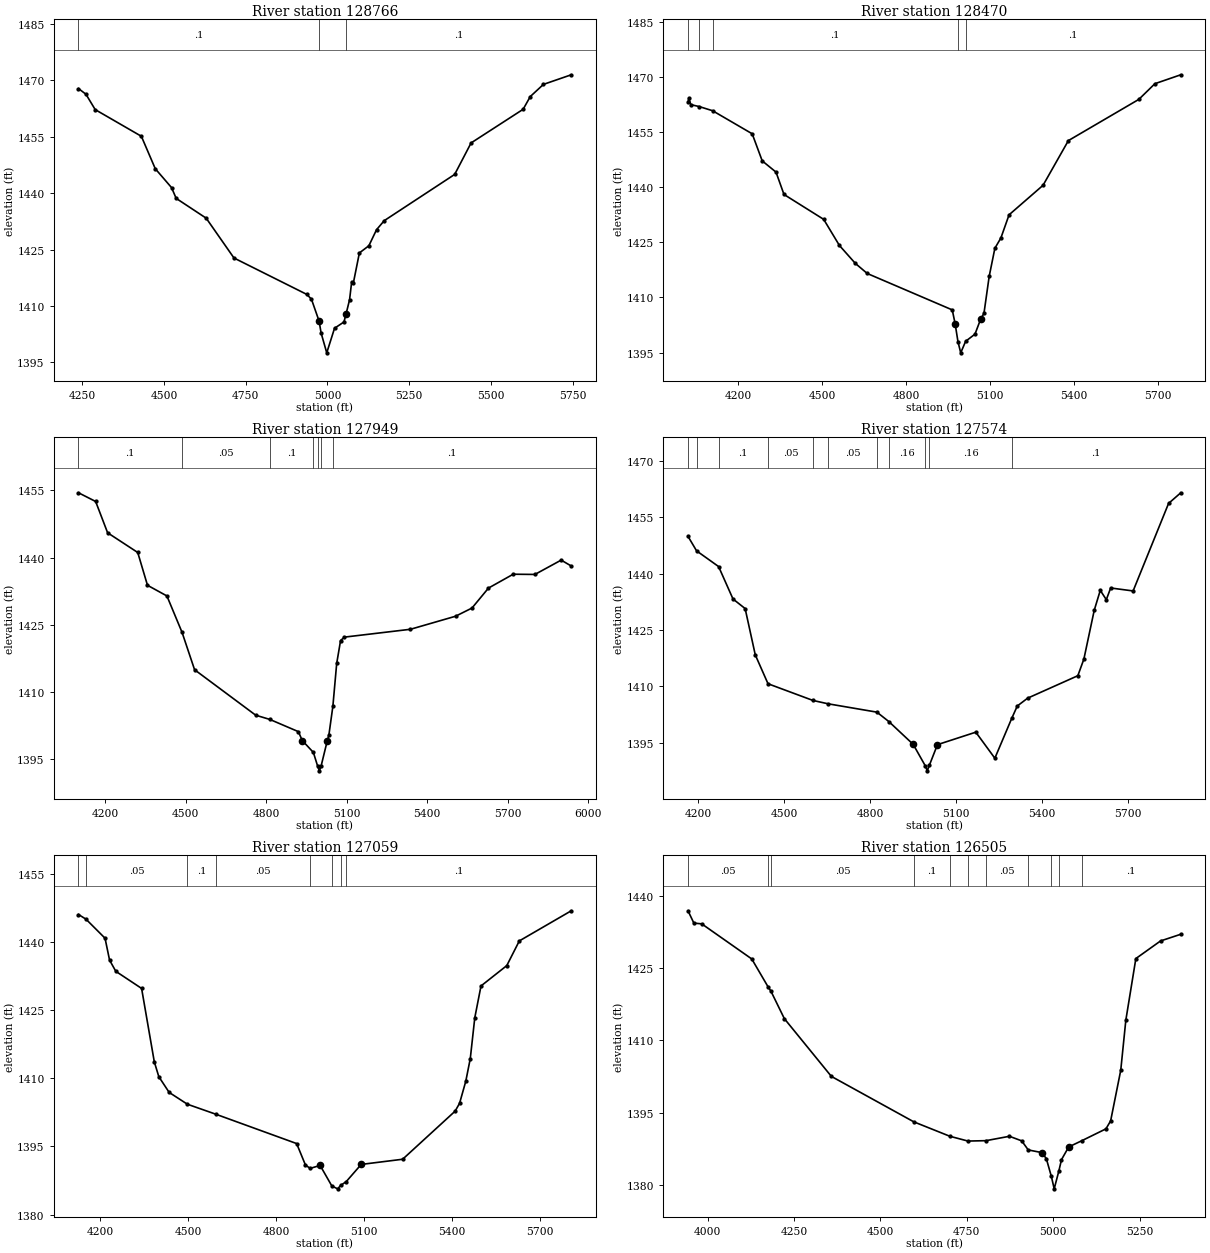
Type RM Length L Ch R = 1 ,128766  ,296,296,296
BEGIN DESCRIPTION:
CYPRESS CREEK 215.0
END DESCRIPTION:
XS GIS Cut Line= 4
      2901856.69     10117307.44      2901455.68     10116932.47
      2901080.68     10116771.01      2900533.77     10116713.72
#Sta/Elev= 30
  4238.4 1467.84  4261.2 1466.33  4289.5 1462.24  4430.7 1455.14  4473.2 1446.51
    4523 1441.48  4537.2 1438.61    4629 1433.34    4714 1422.74  4936.8 1413.05
  4950.9 1411.79  4974.4 1405.92  4980.4  1402.8  4997.7  1397.5  5021.5 1404.04
  5050.4 1405.72  5056.6 1407.78  5067.5 1411.63    5074 1416.45  5079.4 1416.22
  5097.5 1424.09  5126.5    1426    5150 1430.27  5173.5 1432.68    5389 1444.99
  5439.2 1453.37  5598.3 1462.32  5620.2 1465.71  5660.4 1468.95  5745.6 1471.51
#Mann= 3 , 0 , 0
  4238.4      .1       0  4974.4     .07       0  5056.6      .1       0
Bank Sta=4974.4,5056.6
XS Rating Curve= 0 ,0
Exp/Cntr=0.3,0.1

Type RM Length L Ch R = 1 ,128470  ,521,521,521
BEGIN DESCRIPTION:
CYPRESS CREEK 214.0
END DESCRIPTION:
XS GIS Cut Line= 4
      2902044.23     10117172.06      2901518.18     10116593.93
      2901085.89     10116521.01      2900549.48      10116578.3
#Sta/Elev= 30
  4021.1 1463.04  4023.9 1464.17  4031.3 1462.41  4061.2 1461.89  4108.9 1460.76
  4250.3 1454.49  4286.1 1447.13  4335.4 1444.07  4363.8    1438  4505.6 1431.23
  4561.8 1424.13  4618.5 1419.27  4661.1 1416.52  4964.7 1406.62  4974.9 1402.86
    4985    1398  4994.9 1394.95  5012.4 1398.09  5045.8 1400.03  5066.1 1404.13
  5077.9  1405.7  5096.5 1415.73  5116.8 1423.37  5138.4 1426.19  5167.5 1432.47
  5288.8 1440.49  5379.3 1452.64  5630.8 1463.84  5688.3 1468.11  5780.6 1470.53
#Mann= 5 ,-1 , 0
  4021.1      .1       0  4061.2     .05       0  4108.9      .1       0
    4985     .07       0  5012.4      .1       0
Bank Sta=4974.9,5066.1
XS Rating Curve= 0 ,0
Exp/Cntr=0.3,0.1

Type RM Length L Ch R = 1 ,127949  ,375,375,375
BEGIN DESCRIPTION:
CYPRESS CREEK 213.0
END DESCRIPTION:
XS GIS Cut Line= 4
      2902273.36     10116557.45      2901643.18     10116208.51
      2901377.56     10116000.18      2900617.12     10116166.85
#Sta/Elev= 30
  4100.4 1454.46  4164.3 1452.52  4208.9 1445.53  4321.2 1441.13  4357.5 1433.81
  4429.9 1431.43  4486.4 1423.29    4533 1414.96  4760.8 1404.81  4813.3 1403.87
  4919.8 1401.14  4934.3 1399.16  4975.7  1396.5  4991.9 1393.39  4998.2 1392.39
  5004.8 1393.53  5027.4 1399.08  5033.7 1400.46  5048.4 1406.81  5062.6 1416.36
  5077.1 1421.48  5091.6 1422.24  5337.5 1423.99  5505.5  1426.9  5566.8 1428.73
  5628.3 1433.19  5720.4 1436.28  5801.3 1436.23  5899.2 1439.43  5936.8 1438.11
#Mann= 7 ,-1 , 0
  4100.4      .1       0  4486.4     .05       0  4813.3      .1       0
  4975.7     .16       0  4991.9     .07       0  5004.8     .16       0
  5048.4      .1       0
Bank Sta=4934.3,5027.4
XS Rating Curve= 0 ,0
Exp/Cntr=0.3,0.1

Type RM Length L Ch R = 1 ,127574  ,515,515,515
BEGIN DESCRIPTION:
CYPRESS CREEK 212.0
END DESCRIPTION:
XS GIS Cut Line= 3
      2902299.41     10116375.16      2901606.73     10115687.68
      2901200.45     10115062.64
#Sta/Elev= 30
  4164.3 1449.93  4194.3 1446.07  4271.2 1441.89  4321.5 1433.26  4363.9 1430.71
  4399.3 1418.39  4443.8  1410.7  4600.6 1406.26  4653.1 1405.37  4824.2 1403.14
    4866 1400.63  4950.9 1394.57  4993.3 1388.84  5000.1 1387.52  5007.4 1388.99
  5035.7 1394.49  5169.7 1397.81  5236.2 1390.88  5295.1 1401.47  5314.6 1404.78
  5350.9 1406.87  5526.1 1412.84  5547.2 1417.26  5583.4 1430.26  5604.5 1435.56
  5625.6 1433.08  5640.8 1436.19  5719.2  1435.4  5843.1  1458.7  5885.7 1461.53
#Mann= 11 ,-1 , 0
  4164.3      .1       0  4194.3     .05       0  4271.2      .1       0
  4443.8     .05       0  4600.6      .1       0  4653.1     .05       0
  4824.2      .1       0    4866     .16       0  4993.3     .07       0
  5007.4     .16       0  5295.1      .1       0
#XS Ineff= 2 , 0
                         5168.18         1397.68
Permanent Ineff=
       T       T
Bank Sta=4950.9,5035.7
XS Rating Curve= 0 ,0
Exp/Cntr=0.3,0.1

Type RM Length L Ch R = 1 ,127059  ,554,554,554
BEGIN DESCRIPTION:
CYPRESS CREEK 211.0
END DESCRIPTION:
XS GIS Cut Line= 4
      2902450.49     10116286.67      2902096.31     10115713.72
      2902101.52     10115291.85      2901789.55      10114797.9
#Sta/Elev= 30
  4126.8    1446  4152.4 1444.97  4217.3 1440.78  4232.7 1435.97    4254  1433.5
  4341.9 1429.74  4385.2 1413.59  4400.6 1410.32  4435.9 1406.86  4498.1 1404.26
  4593.9 1402.09  4870.4 1395.61  4900.4 1390.89  4916.4 1390.15  4950.4  1390.8
  4990.4 1386.28  5010.1 1385.65  5020.4  1386.4  5039.7 1387.26  5090.4 1391.02
  5231.7 1392.16  5410.6 1402.74  5425.8 1404.47    5447 1409.34  5462.3 1414.32
  5477.6 1423.28  5498.8 1430.28  5586.7 1434.76  5629.4 1440.19  5806.5 1446.82
#Mann= 8 ,-1 , 0
  4126.8      .1       0  4152.4     .05       0  4498.1      .1       0
  4593.9     .05       0  4916.4     .16       0  4990.4     .07       0
  5020.4     .16       0  5039.7      .1       0
Bank Sta=4950.4,5090.4
XS Rating Curve= 0 ,0
Exp/Cntr=0.3,0.1

Type RM Length L Ch R = 1 ,126505  ,502,502,502
BEGIN DESCRIPTION:
CYPRESS CREEK 210.0
END DESCRIPTION:
XS GIS Cut Line= 3
      2902794.22     10116119.95      2902533.81     10115281.43
      2902210.88     10114838.71
#Sta/Elev= 30
  3943.2 1436.89  3960.2 1434.33  3982.9 1434.18  4127.7  1426.9  4175.5 1421.04
  4183.3  1420.2    4222 1414.52  4358.1 1402.54  4596.8 1393.11  4701.1 1390.12
  4753.3 1389.13  4805.5 1389.21  4873.4 1390.12  4908.9 1389.17  4927.8 1387.29
  4966.9 1386.74    4980 1385.51  4994.7  1381.8  5002.9 1379.22  5016.4 1382.93
    5024 1385.27  5044.9 1387.91  5082.2 1389.18  5152.6 1391.66  5166.2 1393.31
  5195.5 1403.82  5210.2  1414.2  5239.2 1426.98  5310.6 1430.63  5369.2 1432.02
#Mann= 11 ,-1 , 0
  3943.2     .05       0  4175.5      .1       0  4183.3     .05       0
  4596.8      .1       0  4701.1     .05       0  4753.3      .1       0
  4805.5     .05       0  4927.8     .16       0  4994.7     .07       0
  5016.4     .16       0  5082.2      .1       0
Bank Sta=4966.9,5044.9
XS Rating Curve= 0 ,0
Exp/Cntr=0.3,0.1

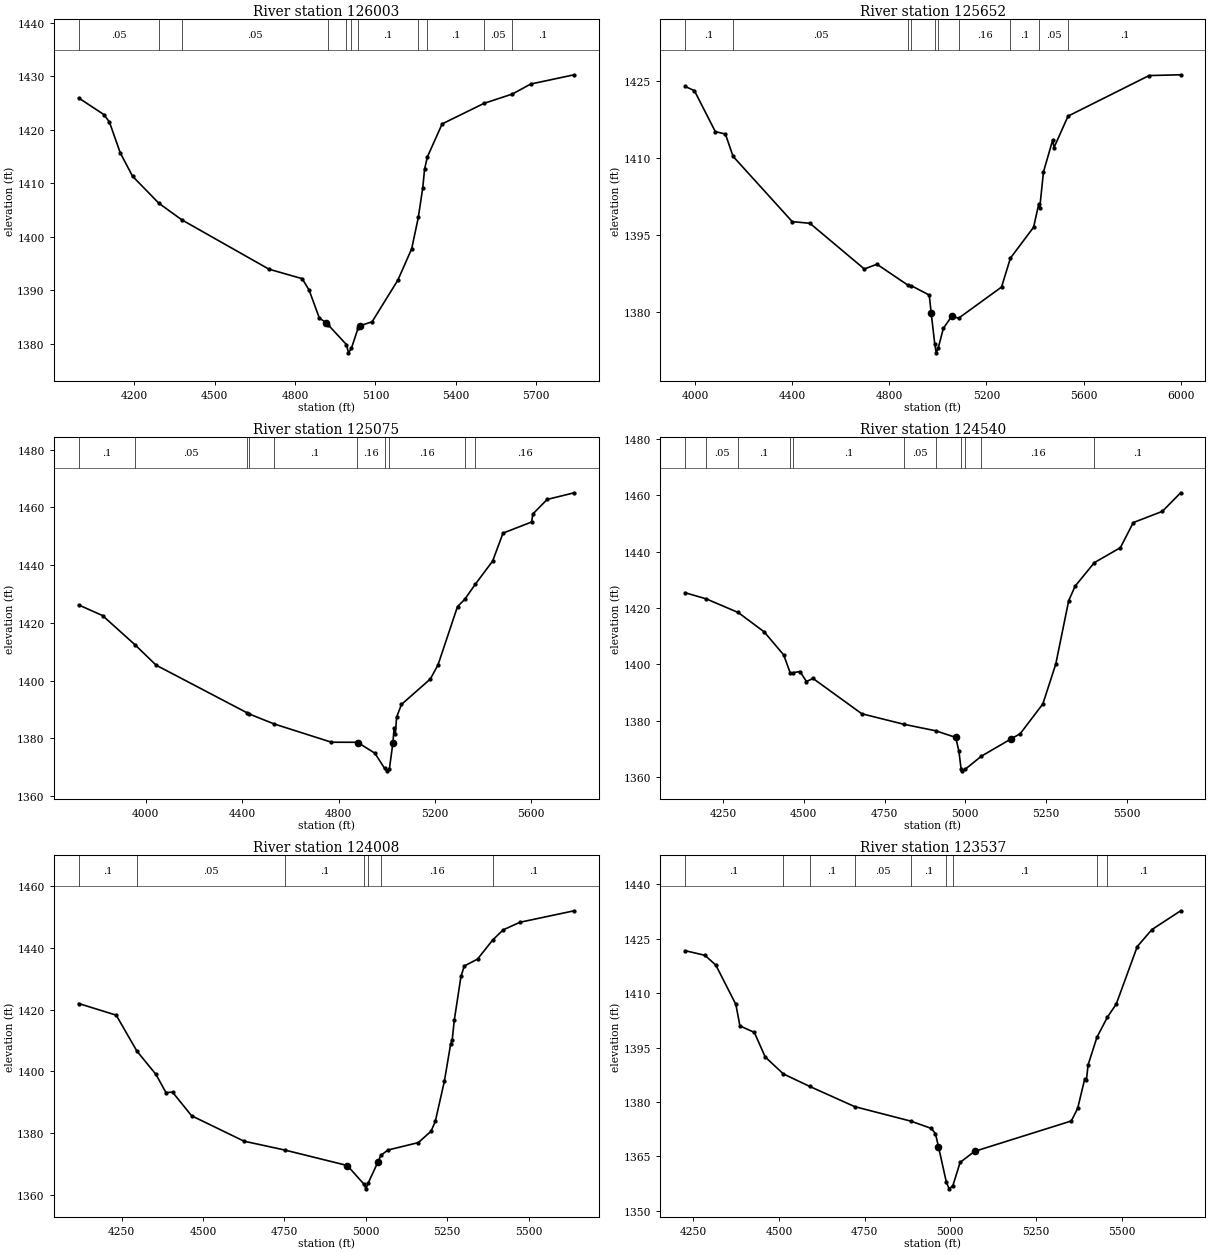
Type RM Length L Ch R = 1 ,126003  ,351,351,351
BEGIN DESCRIPTION:
CYPRESS CREEK 209.0
END DESCRIPTION:
XS GIS Cut Line= 4
       2903085.9     10115916.89      2902971.31     10115213.72
      2902825.48     10114765.81      2902181.57     10114599.64
#Sta/Elev= 30
    3993 1425.96  4087.4 1422.84  4107.7 1421.47  4148.2  1415.7  4194.2 1411.31
  4292.3 1406.26  4377.5 1403.17  4702.9 1393.93    4827 1392.15  4852.7 1390.02
  4890.9 1384.79  4915.8 1383.93  4922.8 1383.57  4991.9 1379.83  4999.6 1378.28
  5010.4 1379.11  5035.4 1382.89    5042 1383.34  5087.7 1384.09  5183.7 1391.87
  5235.4 1397.75  5260.1 1403.61  5276.7 1409.15  5283.4 1412.62    5294 1414.94
    5349  1421.1    5505 1424.94    5611 1426.69  5679.5 1428.56  5841.5 1430.29
#Mann= 11 ,-1 , 0
    3993     .05       0  4292.3      .1       0  4377.5     .05       0
  4922.8     .16       0  4991.9     .07       0  5010.4     .16       0
  5035.4      .1       0  5260.1     .05       0    5294      .1       0
    5505     .05       0    5611      .1       0
Bank Sta=4915.8,5042
XS Rating Curve= 0 ,0
Exp/Cntr=0.3,0.1

Type RM Length L Ch R = 1 ,125652  ,577,577,577
BEGIN DESCRIPTION:
CYPRESS CREEK 208.0
END DESCRIPTION:
XS GIS Cut Line= 4
      2903554.65     10115703.32      2903315.06     10114864.76
      2903065.06     10114677.26      2902222.37     10114526.41
#Sta/Elev= 30
  3958.8 1423.95  3997.1 1423.13  4083.2 1415.16  4124.8 1414.69  4156.2 1410.35
  4400.1 1397.64  4472.9 1397.32  4696.8 1388.43  4748.8 1389.35  4878.3 1385.22
    4891 1385.16  4964.2 1383.35  4972.4  1379.8  4986.9 1373.85  4992.9 1372.11
  5001.5 1373.11  5022.4 1376.88  5057.8 1379.29  5084.9 1378.84  5261.9 1384.91
  5298.6 1390.55  5393.9 1396.55  5415.6 1401.16  5419.1 1400.25  5434.6 1407.31
  5472.9 1413.57  5477.9 1412.04  5535.8 1418.17  5869.6 1426.07  5999.5 1426.22
#Mann= 10 ,-1 , 0
  3958.8      .1       0  4156.2     .05       0  4878.3      .1       0
    4891     .05       0  4986.9    .035       0  5001.5     .05       0
  5084.9     .16       0  5298.6      .1       0  5415.6     .05       0
  5535.8      .1       0
Bank Sta=4972.4,5057.8
XS Rating Curve= 0 ,0
Exp/Cntr=0.3,0.1

Type RM Length L Ch R = 1 ,125075  ,535,535,535
BEGIN DESCRIPTION:
CYPRESS CREEK 206.0
END DESCRIPTION:
XS GIS Cut Line= 4
      2903700.47     10115640.79      2903486.93     10114630.39
      2903512.98     10114187.68      2903799.45     10113682.44
#Sta/Elev= 30
  3720.9 1426.21  3820.1 1422.53  3955.3 1412.38  4042.4 1405.36  4420.4 1388.83
  4428.9 1388.45    4532    1385  4770.3 1378.66  4874.6 1378.64  4880.5 1378.53
  4950.6 1374.86  4990.7 1369.64  5000.4 1368.75  5010.7 1369.32 5025.35 1378.37
  5030.4 1383.55  5035.5 1381.34  5040.8 1387.34  5060.8 1391.73    5181 1400.57
  5212.9 1405.49  5293.6 1425.64  5323.5 1428.12    5367 1433.32  5439.3 1441.38
  5482.6 1451.08  5600.9 1454.92  5606.6 1457.73  5665.8 1462.74  5777.9 1465.05
#Mann= 10 ,-1 , 0
  3720.9      .1       0  3955.3     .05       0  4420.4      .1       0
  4428.9     .05       0    4532      .1       0  4874.6     .16       0
  4990.7     .07       0  5010.7     .16       0  5323.5      .1       0
    5367     .16       0
Bank Sta=4880.5,5025.35
XS Rating Curve= 0 ,0
Exp/Cntr=0.3,0.1

Type RM Length L Ch R = 1 ,124540  ,532,532,532
BEGIN DESCRIPTION:
CYPRESS CREEK 205.0
END DESCRIPTION:
XS GIS Cut Line= 3
      2903997.35     10115536.66      2903919.23     10114916.85
      2903940.02      10114007.1
#Sta/Elev= 30
  4132.2  1425.4  4197.2 1423.25  4296.6 1418.41    4377 1411.56  4437.5  1403.4
  4458.4 1396.83    4466 1397.08    4488 1397.51  4508.1 1393.95  4528.2 1395.07
  4679.4 1382.56  4810.1 1378.82  4908.3 1376.53  4970.1 1374.19  4980.1 1369.38
  4987.1 1362.85  4989.8 1362.35  5000.1 1362.95  5049.7 1367.53  5140.1 1373.55
  5170.1  1375.5  5240.2 1386.04  5280.2 1400.15  5320.2  1422.6  5340.2 1427.75
  5399.6 1436.05  5480.2 1441.35  5520.2 1450.24  5610.3 1454.21  5666.9 1460.79
#Mann= 11 ,-1 , 0
  4132.2      .1       0  4197.2     .05       0  4296.6      .1       0
  4458.4     .05       0    4466      .1       0  4810.1     .05       0
  4908.3      .1       0  4987.1     .07       0  5000.1      .1       0
  5049.7     .16       0  5399.6      .1       0
Bank Sta=4970.1,5140.1
XS Rating Curve= 0 ,0
Exp/Cntr=0.3,0.1

Type RM Length L Ch R = 1 ,124008  ,471,471,471
BEGIN DESCRIPTION:
CYPRESS CREEK 204.0
END DESCRIPTION:
XS GIS Cut Line= 2
      2904257.76     10115547.09      2904544.22     10114052.29
#Sta/Elev= 30
  4117.9 1421.98  4233.3  1418.2  4297.1 1406.51  4355.5 1398.98  4386.1 1393.12
  4406.4 1393.24  4464.7  1385.6  4625.9 1377.35  4751.9 1374.46  4943.1 1369.46
  4995.1 1363.31  4999.9  1361.9  5007.2 1363.75  5037.7 1370.72  5045.9 1372.73
  5068.2 1374.49  5161.3 1376.89  5200.6  1380.6  5213.4 1383.79  5241.3 1396.81
  5260.3 1408.74  5265.4 1410.29  5271.9 1416.73  5292.2 1430.77  5302.4 1434.14
  5343.2 1436.38  5389.4 1442.53  5421.4 1445.83  5473.5 1448.32  5639.9 1452.04
#Mann= 7 ,-1 , 0
  4117.9      .1       0  4297.1     .05       0  4751.9      .1       0
  4995.1     .07       0  5007.2      .1       0  5045.9     .16       0
  5389.4      .1       0
Bank Sta=4943.1,5037.7
XS Rating Curve= 0 ,0
Exp/Cntr=0.3,0.1

Type RM Length L Ch R = 1 ,123537  ,447,447,447
BEGIN DESCRIPTION:
CYPRESS CREEK 203.0
END DESCRIPTION:
XS GIS Cut Line= 3
      2904585.88     10115635.62      2904893.18     10114703.31
      2904992.15     10114250.14
#Sta/Elev= 30
  4226.3 1421.72  4284.3 1420.44  4316.1 1417.71  4374.4 1406.89  4386.2 1400.96
  4428.3 1399.17  4459.9  1392.4  4512.8 1387.72    4590 1384.25  4721.2 1378.68
  4884.5 1374.69  4944.3 1372.68  4956.7 1371.22  4965.3 1367.66  4988.5 1357.79
  4996.7    1356  5007.5 1356.91  5028.5 1363.29  5070.6 1366.34  5352.9 1374.73
  5371.3 1378.17  5391.7 1386.18  5396.8 1385.94    5402 1390.25  5427.7 1397.84
  5458.3  1403.4  5483.9 1406.97  5545.3 1422.86  5587.8 1427.53  5671.8 1432.73
#Mann= 9 ,-1 , 0
  4226.3      .1       0  4512.8     .05       0    4590      .1       0
  4721.2     .05       0  4884.5      .1       0  4988.5     .07       0
  5007.5      .1       0  5427.7     .16       0  5458.3      .1       0
Bank Sta=4965.3,5070.6
XS Rating Curve= 0 ,0
Exp/Cntr=0.3,0.1