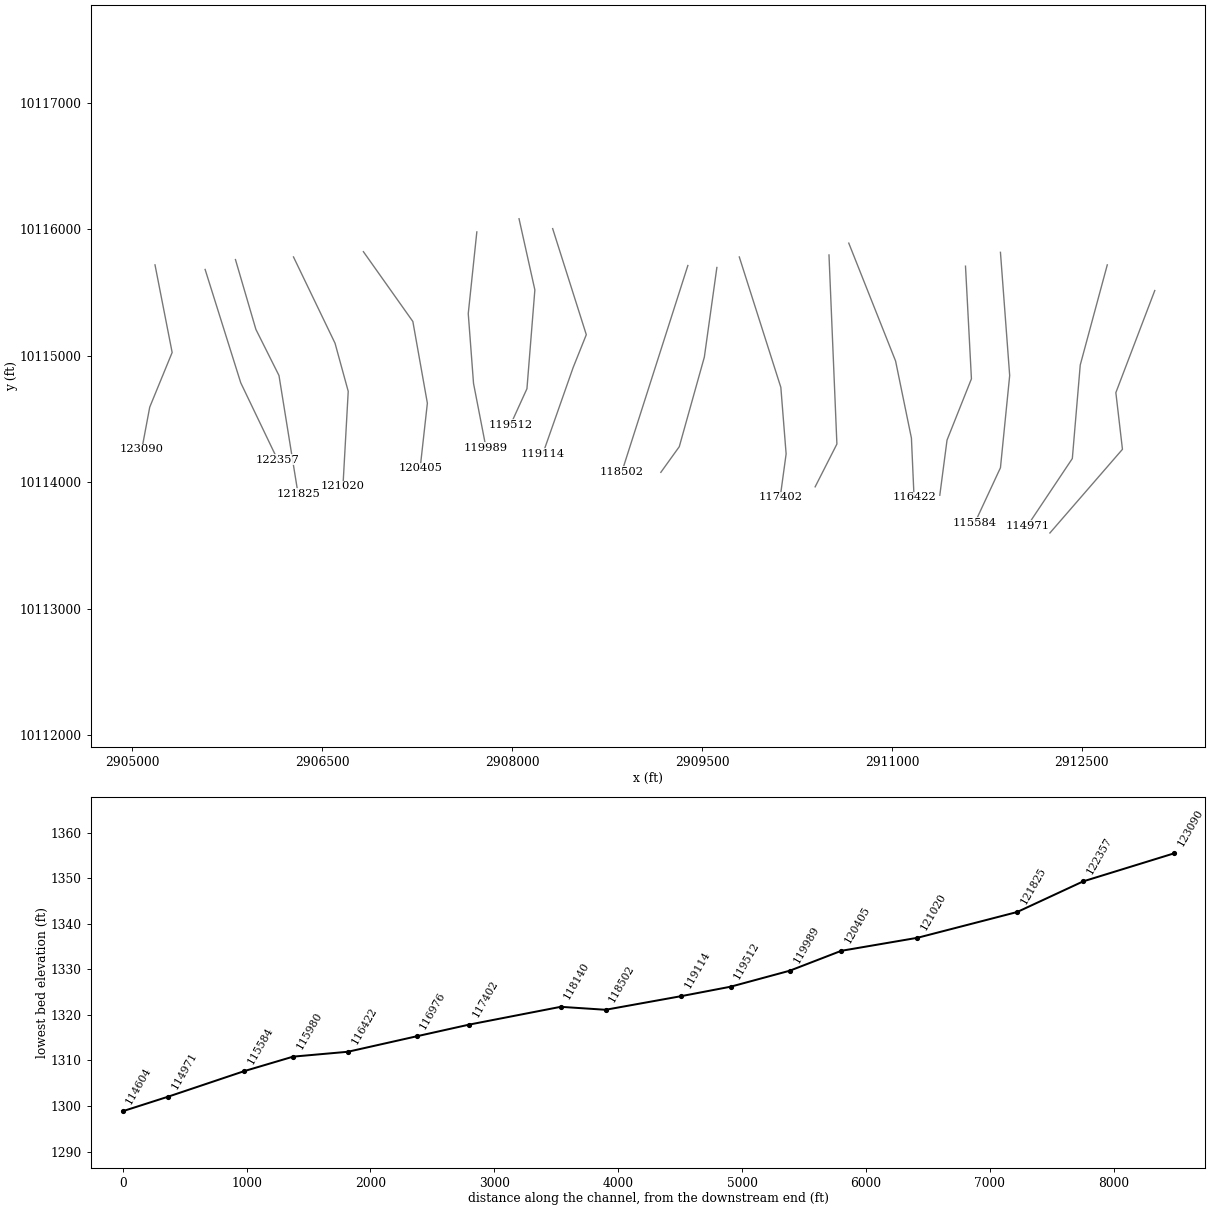
HEC-RAS study CYPRESS CREEK.prj: CYPRESS CREEK Base Level Engineering

--- CYPRESS CREEK.g01 (geometry) --- (continued)

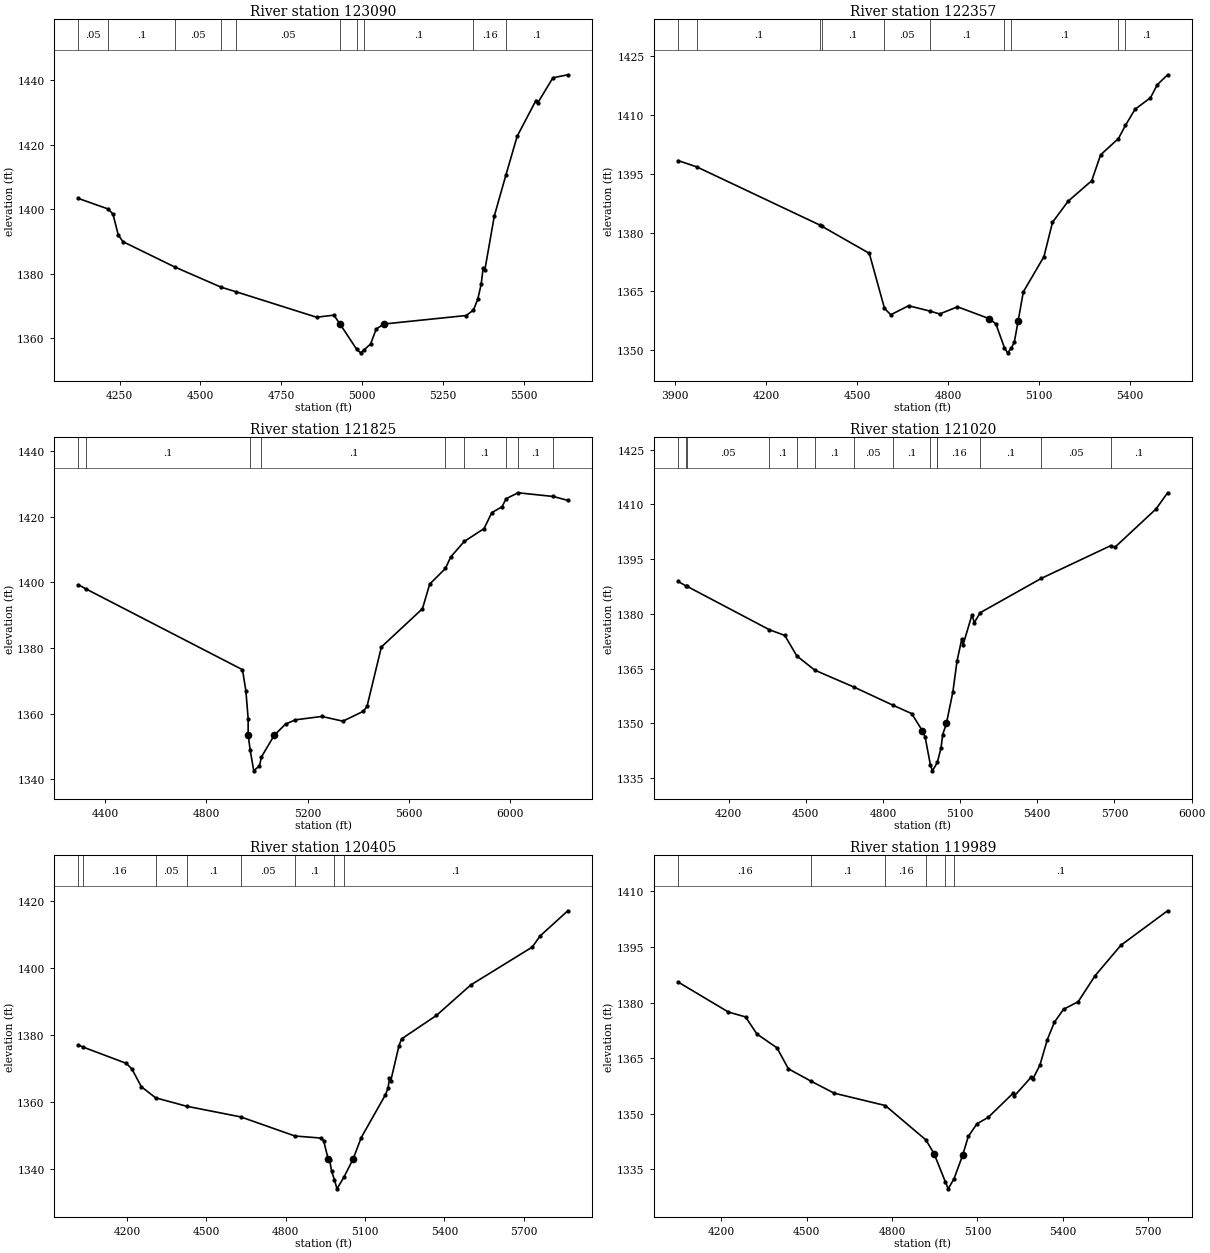
Type RM Length L Ch R = 1 ,123090  ,733,733,733
BEGIN DESCRIPTION:
CYPRESS CREEK 202.0
END DESCRIPTION:
XS GIS Cut Line= 4
      2905179.64     10115718.94      2905315.06     10115026.22
      2905137.98     10114593.93      2905075.48     10114260.62
#Sta/Elev= 30
  4122.7 1403.34  4215.2 1400.05  4229.9 1398.43    4246 1392.01  4260.5 1389.93
  4420.3  1382.1  4563.9 1375.81  4608.6 1374.45  4858.7 1366.51  4912.1 1367.15
  4931.7 1364.31  4982.5 1356.58  4994.6 1355.47  5004.1 1356.28  5025.7 1358.22
  5042.9 1362.86  5066.9 1364.41  5320.7 1367.04  5343.3 1368.71  5356.9 1372.21
  5367.1 1376.71  5373.3 1381.66  5378.4 1381.09  5407.8 1397.92  5443.6  1410.6
  5478.4 1422.61  5536.1 1433.67  5541.2 1432.82  5588.7 1440.73  5634.8 1441.67
#Mann= 10 ,-1 , 0
  4122.7     .05       0  4215.2      .1       0  4420.3     .05       0
  4563.9      .1       0  4608.6     .05       0  4931.7      .1       0
  4982.5     .07       0  5004.1      .1       0  5343.3     .16       0
  5443.6      .1       0
Bank Sta=4931.7,5066.9
XS Rating Curve= 0 ,0
Exp/Cntr=0.3,0.1

Type RM Length L Ch R = 1 ,122357  ,532,532,532
BEGIN DESCRIPTION:
CYPRESS CREEK 200.0
END DESCRIPTION:
XS GIS Cut Line= 3
      2905575.47     10115682.48      2905856.73     10114786.64
      2906148.03     10114178.01
#Sta/Elev= 30
  3910.5 1398.39  3972.6 1396.76  4379.4 1381.87  4383.4 1381.67  4540.7 1374.72
  4590.8 1360.68  4611.4 1359.04  4670.4 1361.34  4741.4 1359.96  4772.8 1359.24
  4831.5 1361.07  4935.2 1358.07  4957.9 1356.73  4986.1 1350.66  4996.5 1349.32
  5008.7 1350.45    5019 1352.11  5031.4 1357.44  5048.5 1364.88  5116.5 1373.87
  5144.7 1382.64  5196.4 1388.03    5274 1393.25  5303.4 1399.86  5362.1 1404.02
  5385.2 1407.37  5416.8 1411.49  5467.6 1414.41  5490.3 1417.77  5524.2 1420.29
#Mann= 10 ,-1 , 0
  3910.5     .05       0  3972.6      .1       0  4379.4     .05       0
  4383.4      .1       0  4590.8     .05       0  4741.4      .1       0
  4986.1     .07       0  5008.7      .1       0  5362.1     .05       0
  5385.2      .1       0
Bank Sta=4935.2,5031.4
XS Rating Curve= 0 ,0
Exp/Cntr=0.3,0.1

Type RM Length L Ch R = 1 ,121825  ,805,805,805
BEGIN DESCRIPTION:
CYPRESS CREEK 199.0
END DESCRIPTION:
XS GIS Cut Line= 4
      2905815.06     10115760.58      2905976.52     10115208.51
      2906158.81     10114843.93      2906309.66     10113907.61
#Sta/Elev= 30
  4295.4 1399.29  4325.9    1398    4943 1373.41  4956.5 1366.96  4965.4 1358.52
 4965.44 1353.61  4973.3 1348.96  4987.5  1342.6  5010.1 1344.15    5018 1346.85
  5068.3 1353.42    5113 1356.85  5152.2 1358.14  5256.1 1359.17  5339.2 1357.73
  5420.2 1360.74  5434.3  1362.2  5491.1 1380.33  5653.2 1391.99  5681.6 1399.47
  5743.8 1404.25  5764.6 1407.75    5818 1412.47  5896.3  1416.4  5926.7 1421.26
  5967.2 1423.05  5983.1 1425.49  6030.4  1427.3  6169.3 1426.17  6226.6 1424.98
#Mann= 9 ,-1 , 0
  4295.4     .05       0  4325.9      .1       0  4973.3     .07       0
    5018      .1       0  5743.8     .05       0    5818      .1       0
  5983.1     .05       0  6030.4      .1       0  6169.3     .05       0
Bank Sta=4965.44,5068.3
XS Rating Curve= 0 ,0
Exp/Cntr=0.3,0.1

Type RM Length L Ch R = 1 ,121020  ,615,615,615
BEGIN DESCRIPTION:
CYPRESS CREEK 197.0
END DESCRIPTION:
XS GIS Cut Line= 4
      2906273.38     10115781.45      2906601.52     10115099.14
      2906705.68     10114718.93      2906664.02     10113968.92
#Sta/Elev= 30
    4004 1388.89  4035.4 1387.61  4037.7 1387.58  4358.4 1375.65  4418.5 1374.08
  4465.4 1368.44  4535.3 1364.55  4686.9 1359.93  4838.4 1354.96  4911.9 1352.63
  4952.9 1347.98  4963.7 1346.33  4984.5 1338.58  4992.3 1336.94  5011.5 1339.24
  5025.9 1343.26  5032.3 1346.89  5046.7 1349.93  5071.9  1358.6  5088.1  1367.1
  5106.4 1373.07  5111.6 1371.54  5146.1 1379.71  5155.3 1377.57  5177.6 1380.29
  5415.3 1389.71  5686.1 1398.72  5701.4 1398.24  5861.6 1408.77  5906.5  1413.2
#Mann= 14 ,-1 , 0
    4004     .05       0  4035.4      .1       0  4037.7     .05       0
  4358.4      .1       0  4465.4     .05       0  4535.3      .1       0
  4686.9     .05       0  4838.4      .1       0  4984.5     .07       0
  5011.5      .1       0  5011.5     .16       0  5177.6      .1       0
  5415.3     .05       0  5686.1      .1       0
Bank Sta=4952.9,5046.7
XS Rating Curve= 0 ,0
Exp/Cntr=0.3,0.1

Type RM Length L Ch R = 1 ,120405  ,416,416,416
BEGIN DESCRIPTION:
CYPRESS CREEK 196.0
END DESCRIPTION:
XS GIS Cut Line= 4
      2906825.46     10115823.12       2907216.1     10115271.01
      2907330.68     10114625.18      2907273.43      10114109.9
#Sta/Elev= 30
  4015.9 1376.95  4032.7 1376.36  4197.8 1371.46  4218.7 1369.75  4254.4 1364.49
  4308.2  1361.2  4425.1  1358.7  4630.3 1355.51  4835.1 1349.82  4933.2 1349.21
  4943.4 1348.42    4961 1342.83  4966.1 1342.64  4973.8 1339.25    4984 1336.83
  4993.9 1334.08  5020.1 1337.56  5055.1 1343.02  5085.6 1349.36    5177  1362.1
  5187.1 1364.13  5192.3 1367.07  5197.3 1366.31  5227.7 1376.56  5237.9 1378.75
  5369.7 1385.74  5499.8 1394.84  5731.9 1406.11  5762.1 1409.45  5866.6 1416.94
#Mann= 8 ,-1 , 0
  4015.9      .1       0  4032.7     .16       0  4308.2     .05       0
  4425.1      .1       0  4630.3     .05       0  4835.1      .1       0
    4984     .07       0  5020.1      .1       0
Bank Sta=4961,5055.1
XS Rating Curve= 0 ,0
Exp/Cntr=0.3,0.1

Type RM Length L Ch R = 1 ,119989  ,477,477,477
BEGIN DESCRIPTION:
CYPRESS CREEK 195.0
END DESCRIPTION:
XS GIS Cut Line= 4
      2907721.31     10115979.33       2907653.6     10115333.51
      2907695.27     10114781.43      2907793.84     10114273.01
#Sta/Elev= 30
  4047.8 1385.53  4224.4 1377.44  4284.7 1376.12  4324.9  1371.5  4395.3 1367.77
  4435.5 1362.11  4514.6 1358.79  4596.4 1355.53  4776.1  1352.2  4919.1  1342.9
  4947.6  1339.2  4987.8 1331.51  4997.5 1329.71  5017.8 1332.44  5047.9 1338.73
    5068 1343.87  5098.5 1347.27  5138.2 1349.02  5225.2  1355.5  5230.2 1354.82
    5289 1359.85  5294.1 1359.23  5319.8 1363.13  5345.8 1369.99  5370.7 1374.69
  5402.7 1378.17  5454.4 1380.23  5513.3  1387.2  5604.5 1395.47  5768.7 1404.77
#Mann= 6 ,-1 , 0
  4047.8     .16       0  4514.6      .1       0  4776.1     .16       0
  4919.1      .1       0  4987.8     .07       0  5017.8      .1       0
Bank Sta=4947.6,5047.9
XS Rating Curve= 0 ,0
Exp/Cntr=0.3,0.1

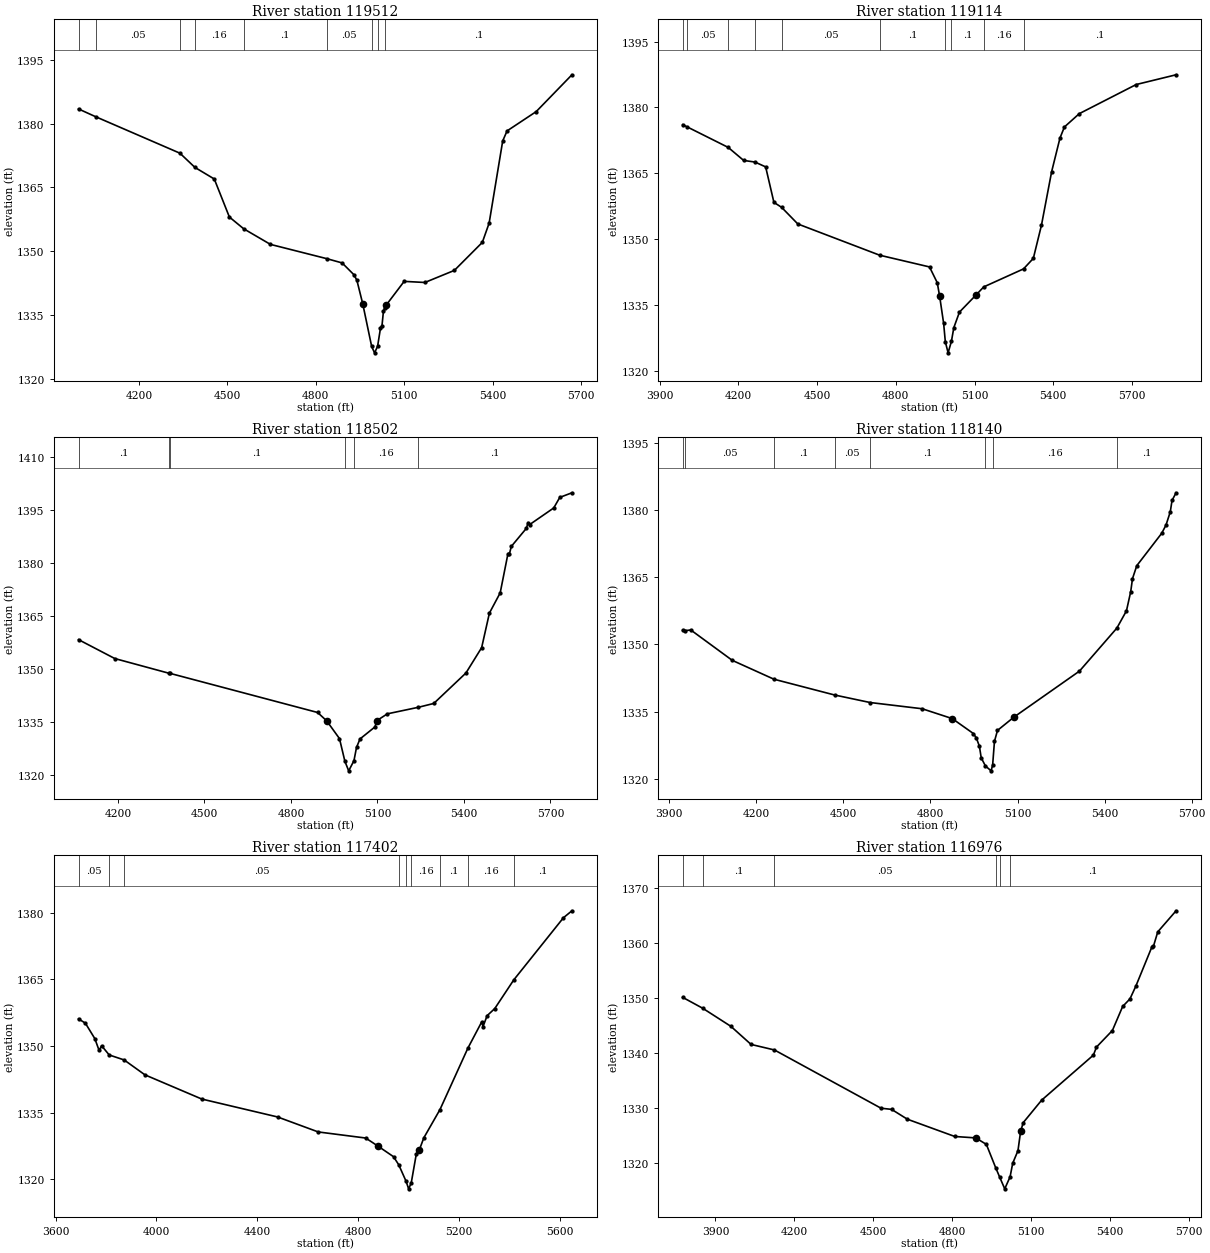
Type RM Length L Ch R = 1 ,119512  ,398,398,398
BEGIN DESCRIPTION:
CYPRESS CREEK 194.0
END DESCRIPTION:
XS GIS Cut Line= 4
      2908054.63     10116083.56      2908179.64     10115521.01
      2908117.14     10114739.76      2907986.93     10114453.29
#Sta/Elev= 30
  3994.7 1383.43  4053.1  1381.6  4338.8 1373.05  4389.8 1369.71  4455.5 1366.99
  4506.7 1358.07  4555.1 1355.32    4646 1351.65  4837.3  1348.3  4889.3  1347.3
  4929.4 1344.53  4939.4 1343.25  4959.5 1337.66  4989.6  1327.7  4999.4  1326.2
  5009.7  1327.7  5019.6 1332.02  5024.7 1332.59  5029.7 1336.05  5034.8 1336.77
  5039.7 1337.47  5099.9 1342.97  5170.2 1342.71  5270.4 1345.55  5365.2 1352.12
  5388.3 1356.63  5434.4 1375.93  5449.2 1378.28  5548.1 1382.81  5669.4 1391.45
#Mann= 9 ,-1 , 0
  3994.7      .1       0  4053.1     .05       0  4338.8      .1       0
  4389.8     .16       0  4555.1      .1       0  4837.3     .05       0
  4989.6    .035       0  5009.7     .05       0  5034.8      .1       0
Bank Sta=4959.5,5039.7
XS Rating Curve= 0 ,0
Exp/Cntr=0.3,0.1

Type RM Length L Ch R = 1 ,119114  ,612,612,612
BEGIN DESCRIPTION:
CYPRESS CREEK 193.0
END DESCRIPTION:
XS GIS Cut Line= 4
      2908320.27      10116005.4      2908585.89     10115166.85
      2908481.73     10114906.43      2908242.81     10114226.05
#Sta/Elev= 30
  3987.2 1376.07  4003.2 1375.61  4160.9  1370.9  4219.7 1367.94  4262.7 1367.57
  4303.6 1366.47  4335.1 1358.39  4364.4 1357.26  4426.3 1353.47  4738.3 1346.36
  4928.3 1343.69  4957.9 1340.09  4967.1 1336.96  4982.2 1330.83  4988.6 1326.66
  4999.2 1324.13  5011.8 1326.73    5021 1329.86  5042.5 1333.41  5107.1 1337.39
    5135 1339.14  5286.7 1343.24  5324.1 1345.63  5355.1 1353.18  5393.9 1365.37
  5425.7 1373.03  5442.7 1375.56  5499.4 1378.59  5716.3 1385.22  5868.4 1387.44
#Mann= 10 ,-1 , 0
  3987.2      .1       0  4003.2     .05       0  4160.9      .1       0
  4262.7     .16       0  4364.4     .05       0  4738.3      .1       0
  4988.6     .07       0  5011.8      .1       0    5135     .16       0
  5286.7      .1       0
Bank Sta=4967.1,5107.1
XS Rating Curve= 0 ,0
Exp/Cntr=0.3,0.1

Type RM Length L Ch R = 1 ,118502  ,362,362,362
BEGIN DESCRIPTION:
CYPRESS CREEK 192.0
END DESCRIPTION:
XS GIS Cut Line= 2
      2909387.98     10115713.74      2908867.14     10114083.52
#Sta/Elev= 30
  4063.2 1358.28  4189.2 1352.92    4378 1348.74  4379.1 1348.76  4892.5 1337.65
    4924 1335.28  4968.3 1330.26    4987 1323.86  5000.2 1321.13  5018.5    1324
  5027.4 1327.76  5039.5 1330.16  5091.7 1333.59    5097  1335.3  5134.4 1337.27
  5242.2 1339.13  5295.3 1340.21  5406.9 1348.83  5461.4 1356.01  5488.3 1365.79
  5525.7 1371.52  5552.7 1382.63  5557.9 1382.63  5564.4 1384.68  5616.9 1389.83
  5622.3 1391.44  5627.5 1390.83  5711.4 1395.56  5732.4 1398.55  5774.6 1399.86
#Mann= 6 ,-1 , 0
  4063.2      .1       0    4378     .16       0  4379.1      .1       0
    4987     .07       0  5018.5     .16       0  5242.2      .1       0
Bank Sta=4924,5097
XS Rating Curve= 0 ,0
Exp/Cntr=0.3,0.1

Type RM Length L Ch R = 1 ,118140  ,738,738,738
BEGIN DESCRIPTION:
CYPRESS CREEK 191.0
END DESCRIPTION:
XS GIS Cut Line= 4
      2909617.14     10115698.07      2909518.18     10114989.76
      2909320.27     10114281.43      2909174.61     10114078.55
#Sta/Elev= 30
    3946 1353.19  3954.1 1353.08  3974.1 1353.22    4117 1346.44  4260.7 1342.23
  4469.6 1338.71    4592 1337.03  4771.3 1335.64  4875.1 1333.44  4947.8 1330.11
  4958.2  1329.1  4968.6 1327.27  4974.9 1324.68  4989.3 1322.88  5008.8 1321.78
  5014.2 1323.05  5020.5 1328.36  5030.9  1330.8  5087.7 1333.78  5313.4 1344.04
  5442.3 1353.64  5475.4  1357.5  5490.1  1361.8  5496.2 1364.69    5511 1367.58
  5596.9 1374.81  5611.7 1376.65  5626.4  1379.6  5632.5 1382.15  5646.4 1383.85
#Mann= 8 ,-1 , 0
    3946      .1       0  3954.1     .05       0  4260.7      .1       0
  4469.6     .05       0    4592      .1       0  4989.3     .07       0
  5014.2     .16       0  5442.3      .1       0
Bank Sta=4875.1,5087.7
XS Rating Curve= 0 ,0
Exp/Cntr=0.3,0.1

Type RM Length L Ch R = 1 ,117402  ,426,426,426
BEGIN DESCRIPTION:
CYPRESS CREEK 189.0
END DESCRIPTION:
XS GIS Cut Line= 4
      2909794.22     10115781.44      2910122.35     10114750.18
      2910164.02     10114224.14      2910117.14     10113880.41
#Sta/Elev= 30
  3691.3 1356.12  3718.5 1355.15  3755.9 1351.68  3772.8 1349.04  3782.9 1350.07
    3813    1348  3872.2 1346.88  3954.6 1343.53  4180.2 1338.08  4480.8 1334.05
  4641.9 1330.68  4830.1 1329.31  4880.3 1327.44  4940.5 1325.11  4961.1  1323.3
  4990.6 1319.54  5000.4 1317.88  5010.7 1319.19  5030.8 1325.69  5043.4 1326.73
  5060.8 1329.37  5124.7 1335.71  5235.7 1349.57  5290.4 1355.45  5295.4 1354.38
  5311.7 1356.84    5342 1358.44  5417.5  1364.9  5614.5 1378.88  5648.1 1380.44
#Mann= 9 ,-1 , 0
  3691.3     .05       0    3813      .1       0  3872.2     .05       0
  4961.1     .16       0  4990.6     .07       0  5010.7     .16       0
  5124.7      .1       0  5235.7     .16       0  5417.5      .1       0
Bank Sta=4880.3,5043.4
XS Rating Curve= 0 ,0
Exp/Cntr=0.3,0.1

Type RM Length L Ch R = 1 ,116976  ,554,554,554
BEGIN DESCRIPTION:
CYPRESS CREEK 188.0
END DESCRIPTION:
XS GIS Cut Line= 3
      2910502.56     10115797.11      2910565.06     10114302.26
      2910393.33     10113964.01
#Sta/Elev= 30
  3775.3 1350.12  3851.7 1348.13  3958.8 1344.84  4035.2 1341.56  4124.2 1340.55
  4529.3 1329.96  4569.4 1329.75  4629.4 1327.96  4809.6 1324.82  4889.6 1324.56
  4929.7 1323.38  4965.7 1319.07  4979.7  1317.5  4999.5  1315.3  5019.8 1317.48
  5029.8 1319.95  5049.8 1322.24  5059.8 1325.73  5069.8 1327.34  5139.9 1331.43
  5336.4 1339.61  5348.3 1341.08  5408.7 1344.09  5447.7 1348.46  5475.5 1349.84
  5497.8 1352.15    5559 1359.31  5564.6 1359.38  5581.2 1362.03  5650.8 1365.86
#Mann= 6 ,-1 , 0
  3775.3     .05       0  3851.7      .1       0  4124.2     .05       0
  4965.7      .1       0  4979.7     .07       0  5019.8      .1       0
Bank Sta=4889.6,5059.8
XS Rating Curve= 0 ,0
Exp/Cntr=0.3,0.1

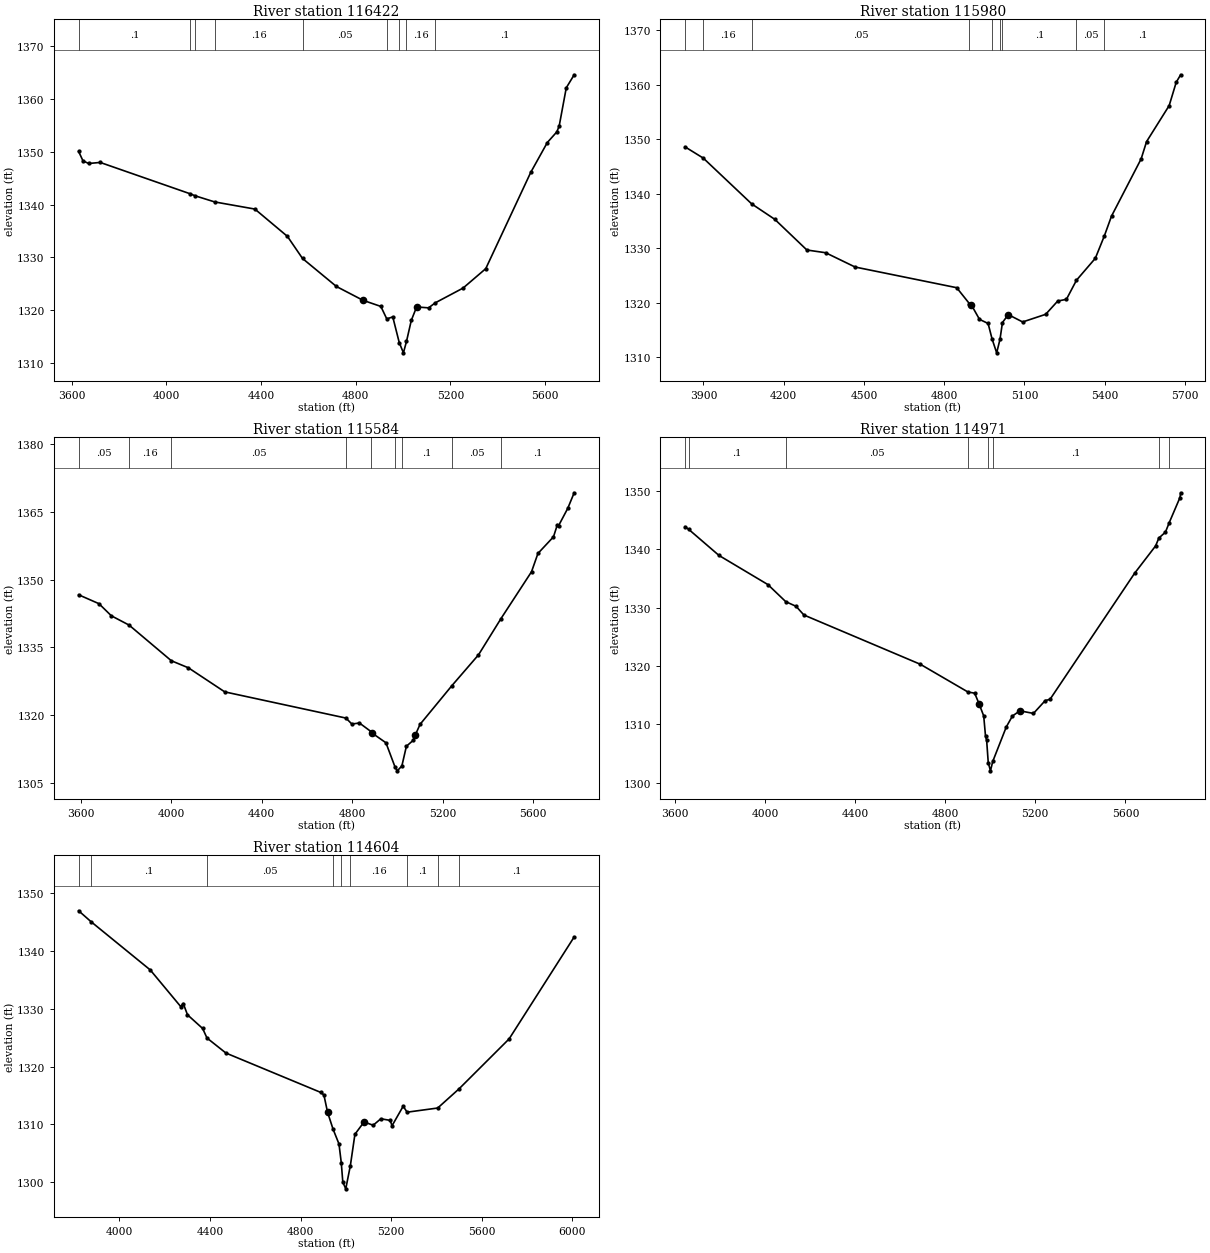
Type RM Length L Ch R = 1 ,116422  ,442,442,442
BEGIN DESCRIPTION:
CYPRESS CREEK 187.0
END DESCRIPTION:
XS GIS Cut Line= 4
      2910658.81     10115890.79       2911028.6     10114958.51
       2911153.6     10114349.14      2911174.43      10113880.4
#Sta/Elev= 30
    3629 1350.09  3647.4 1348.31  3671.5 1347.81  3720.1 1348.01  4100.1 1342.07
  4122.3 1341.67  4204.2 1340.52  4373.7 1339.17  4511.4 1333.99  4575.2  1329.8
  4718.5 1324.49  4830.8 1321.87  4906.2 1320.71  4931.2 1318.35  4956.6 1318.72
  4983.9 1313.86  5001.6 1311.91  5014.5 1314.06  5034.9 1318.07  5057.4 1320.61
  5107.8 1320.44  5136.1 1321.39  5253.7 1324.19  5349.5 1327.87  5539.7 1346.13
  5609.8 1351.79  5649.8  1353.8  5659.8  1354.9  5689.8 1362.16  5723.2 1364.63
#Mann= 9 ,-1 , 0
    3629      .1       0  4100.1     .16       0  4122.3      .1       0
  4204.2     .16       0  4575.2     .05       0  4931.2      .1       0
  4983.9     .07       0  5014.5     .16       0  5136.1      .1       0
Bank Sta=4830.8,5057.4
XS Rating Curve= 0 ,0
Exp/Cntr=0.3,0.1

Type RM Length L Ch R = 1 ,115980  ,396,396,396
BEGIN DESCRIPTION:
CYPRESS CREEK 186.0
END DESCRIPTION:
XS GIS Cut Line= 4
      2911580.68     10115708.51      2911627.56     10114817.89
      2911434.85     10114333.51      2911377.74     10113897.39
#Sta/Elev= 30
  3831.2 1348.59  3899.3 1346.53  4080.3 1338.14  4166.4 1335.32  4286.6 1329.69
  4356.7 1329.19  4466.9 1326.57  4846.8 1322.78  4894.3 1319.86  4900.8  1319.7
    4932 1316.98  4964.3 1316.22    4979  1313.4  4996.3 1310.84  5008.7 1313.32
  5017.9 1316.39  5039.6 1317.85  5093.4  1316.5  5179.5  1317.9  5224.5 1320.33
  5257.1 1320.65  5294.7 1324.15  5365.2 1328.17  5398.9 1332.27  5425.7  1335.9
  5536.6  1346.4  5556.8 1349.56  5641.3 1356.16  5667.7 1360.44  5684.2 1361.81
#Mann= 9 ,-1 , 0
  3831.2      .1       0  3899.3     .16       0  4080.3     .05       0
  4894.3     .16       0    4979     .07       0  5008.7     .16       0
  5017.9      .1       0  5294.7     .05       0  5398.9      .1       0
Bank Sta=4900.8,5039.6
XS Rating Curve= 0 ,0
Exp/Cntr=0.3,0.1

Type RM Length L Ch R = 1 ,115584  ,613,613,613
BEGIN DESCRIPTION:
CYPRESS CREEK 185.0
END DESCRIPTION:
XS GIS Cut Line= 4
      2911856.72     10115817.93      2911929.64     10114843.93
      2911856.73     10114114.76      2911653.93     10113677.98
#Sta/Elev= 30
  3590.3 1346.62  3680.2 1344.65  3734.9 1341.97  3813.4 1339.91  4000.2 1332.02
  4075.9 1330.45  4236.3 1325.13  4772.3 1319.33  4798.4 1318.01  4831.8 1318.24
  4883.9 1316.31  4888.8 1315.98  4949.1 1313.86  4989.3  1308.5  4999.1 1307.65
  5019.5 1308.72  5039.6  1313.1  5069.7  1314.4  5079.8 1315.68  5099.9 1317.94
  5240.8 1326.51  5358.3 1333.32  5457.9 1341.36  5592.8 1351.72  5621.2 1355.77
  5689.9 1359.45  5707.3 1362.16  5712.8 1361.95    5753 1365.75  5781.4  1369.2
#Mann= 9 ,-1 , 0
  3590.3     .05       0  3813.4     .16       0  4000.2     .05       0
  4772.3     .16       0  4883.9      .1       0  4989.3     .07       0
  5019.5      .1       0  5240.8     .05       0  5457.9      .1       0
Bank Sta=4888.8,5079.8
XS Rating Curve= 0 ,0
Exp/Cntr=0.3,0.1

Type RM Length L Ch R = 1 ,114971  ,367,367,367
BEGIN DESCRIPTION:
CYPRESS CREEK 184.0
END DESCRIPTION:
XS GIS Cut Line= 4
      2912700.48     10115718.95      2912486.93     10114927.26
      2912424.43     10114187.68      2912071.03     10113657.58
#Sta/Elev= 30
  3645.7 1343.88  3661.4 1343.45  3796.1 1338.97  4013.3 1333.97  4092.4 1331.05
  4138.2 1330.25    4173 1328.76    4690 1320.31  4900.7 1315.57  4930.9 1315.36
  4950.9 1313.49    4971 1311.46    4979    1308    4984 1307.29  4991.1 1303.47
  5000.9 1302.05  5011.2 1303.67  5071.4 1309.59  5098.5 1311.45  5131.6 1312.34
  5191.8 1311.89  5244.2  1314.1  5265.2  1314.3  5640.8 1335.92    5734 1340.61
  5748.3 1341.95  5777.5 1342.96  5794.5  1344.6  5842.1  1348.9    5845 1349.71
#Mann= 8 ,-1 , 0
  3645.7     .05       0  3661.4      .1       0  4092.4     .05       0
  4900.7      .1       0  4991.1     .07       0  5011.2      .1       0
  5748.3     .05       0  5794.5      .1       0
Bank Sta=4950.9,5131.6
XS Rating Curve= 0 ,0
Exp/Cntr=0.3,0.1

Type RM Length L Ch R = 1 ,114604  ,418,418,418
BEGIN DESCRIPTION:
CYPRESS CREEK 183.0
END DESCRIPTION:
XS GIS Cut Line= 4
      2913075.49     10115515.85      2912768.18     10114708.51
      2912820.27      10114260.6      2912247.32     10113599.11
#Sta/Elev= 30
  3819.4 1346.95  3874.6 1345.05  4135.8 1336.72  4270.3 1330.39  4281.8 1330.91
  4300.4 1328.96  4367.4 1326.59  4386.6 1324.94  4470.3 1322.34  4889.4 1315.53
  4903.3 1315.09  4919.6 1312.08  4943.7 1309.18  4969.9 1306.62    4980 1303.39
  4986.9 1300.01  4999.9 1298.85  5020.3 1302.88  5040.4 1308.29  5080.7 1310.42
    5121 1309.85  5154.9 1310.97  5196.6 1310.69  5204.2 1309.75  5253.6 1313.14
  5271.1 1312.11  5406.2 1312.83  5500.6 1316.15  5721.9 1324.79  6009.3 1342.42
#Mann= 9 ,-1 , 0
  3819.4     .05       0  3874.6      .1       0  4386.6     .05       0
  4943.7     .16       0    4980     .07       0  5020.3     .16       0
  5271.1      .1       0  5406.2     .05       0  5500.6      .1       0
Bank Sta=4919.6,5080.7
XS Rating Curve= 0 ,0
Exp/Cntr=0.3,0.1