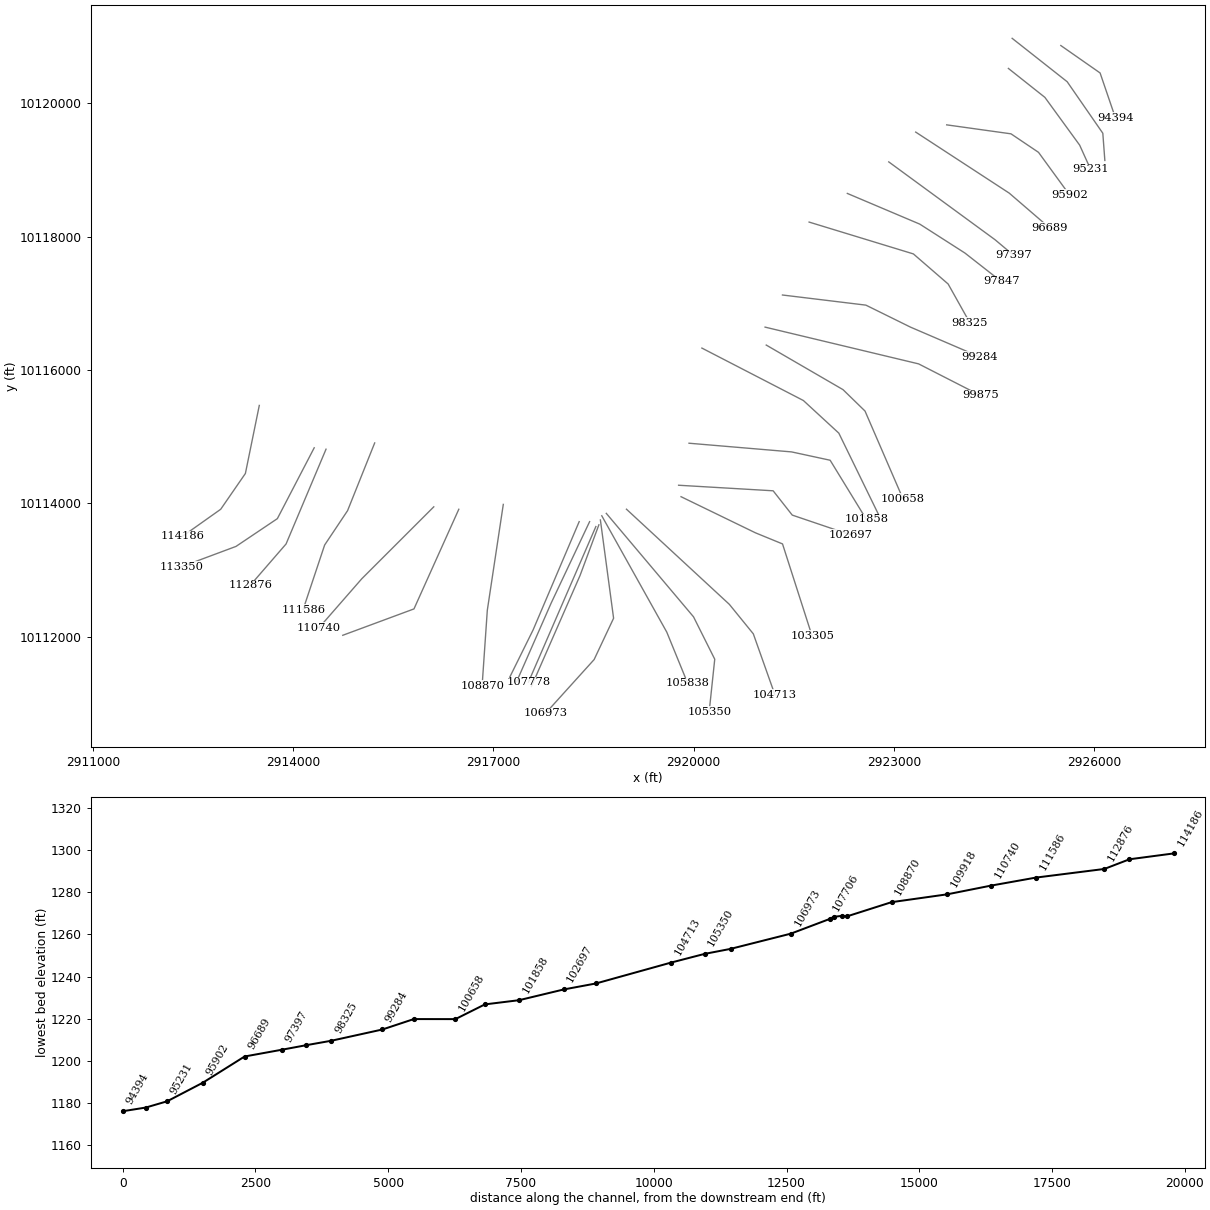
HEC-RAS study CYPRESS CREEK.prj: CYPRESS CREEK Base Level Engineering

--- CYPRESS CREEK.g01 (geometry) --- (continued)

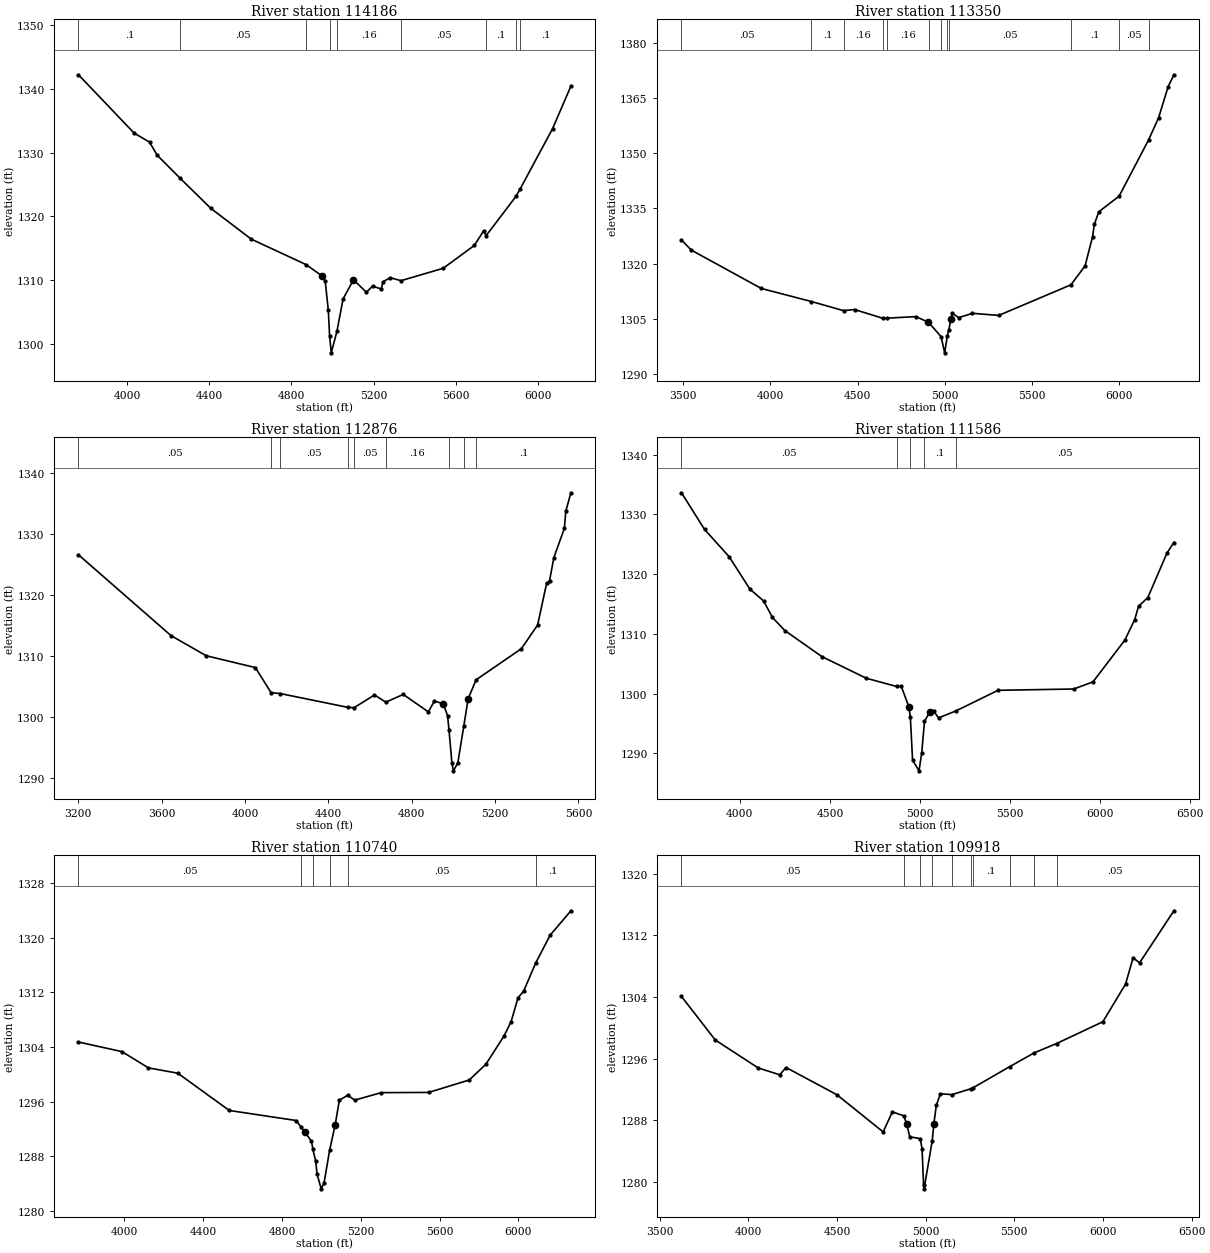
Type RM Length L Ch R = 1 ,114186  ,836,836,836
BEGIN DESCRIPTION:
CYPRESS CREEK 182.0
END DESCRIPTION:
XS GIS Cut Line= 4
      2913492.15     10115468.95      2913283.81      10114448.1
      2912914.02     10113911.64      2912342.32     10113506.25
#Sta/Elev= 30
  3764.4 1342.22  4035.1 1333.06  4109.8 1331.65  4147.4 1329.58  4259.1 1325.96
  4407.8 1321.25  4604.7 1316.41    4872  1312.4  4949.6 1310.62  4964.4 1309.77
  4979.3 1305.21  4985.4 1301.27  4993.5 1298.56  5021.2 1301.94    5051 1307.03
  5101.7 1310.03  5164.6 1308.07  5194.4 1309.04  5236.7 1308.58  5245.1 1309.73
  5280.9 1310.35  5332.9 1309.89  5538.2 1311.84  5689.5 1315.43  5733.9 1317.69
  5746.8 1316.97  5892.1 1323.14  5911.3 1324.25  6069.7 1333.76  6158.7 1340.43
#Mann= 9 ,-1 , 0
  3764.4      .1       0  4259.1     .05       0    4872     .16       0
  4985.4     .07       0  5021.2     .16       0  5332.9     .05       0
  5746.8      .1       0  5892.1     .05       0  5911.3      .1       0
Bank Sta=4949.6,5101.7
XS Rating Curve= 0 ,0
Exp/Cntr=0.3,0.1

Type RM Length L Ch R = 1 ,113350  ,474,474,474
BEGIN DESCRIPTION:
CYPRESS CREEK 181.0
END DESCRIPTION:
XS GIS Cut Line= 4
      2914315.04     10114833.47      2913762.98     10113771.01
      2913143.18     10113354.35      2912321.84     10113047.64
#Sta/Elev= 30
  3491.3 1326.42  3547.4 1323.67  3948.8 1313.25    4235 1309.71  4419.7 1307.23
  4482.7 1307.53  4646.4 1305.13  4666.9 1305.19  4834.4  1305.6  4906.4 1304.08
  4907.1 1304.03  4978.4 1300.18  4999.1 1295.77  5014.4 1300.47  5022.7 1301.95
  5035.4 1305.08  5043.5  1306.5  5079.7 1305.34  5158.4  1306.5  5308.6 1305.93
  5722.3 1314.24  5803.4 1319.39  5846.1 1327.27  5856.9 1330.73  5881.9 1334.07
  5998.5 1338.32  6167.3  1353.6  6224.2 1359.55  6279.5 1368.07  6312.2 1371.28
#Mann= 12 ,-1 , 0
  3491.3     .05       0    4235      .1       0  4419.7     .16       0
  4646.4      .1       0  4666.9     .16       0  4907.1      .1       0
  4978.4     .07       0  5014.4     .16       0  5022.7     .05       0
  5722.3      .1       0  5998.5     .05       0  6167.3      .1       0
Bank Sta=4906.4,5035.4
XS Rating Curve= 0 ,0
Exp/Cntr=0.3,0.1

Type RM Length L Ch R = 1 ,112876  ,1290,1290,1290
BEGIN DESCRIPTION:
CYPRESS CREEK 180.0
END DESCRIPTION:
XS GIS Cut Line= 3
      2914492.14     10114812.68      2913893.18     10113390.81
      2913356.72     10112771.01
#Sta/Elev= 30
  3201.1 1326.54  3644.8 1313.31  3814.5    1310  4049.8 1308.07  4125.3 1303.96
  4168.6 1303.82  4494.5 1301.55  4523.5  1301.5  4621.4 1303.58    4676 1302.41
  4759.4 1303.67    4880 1300.81  4908.5 1302.58  4951.3 1302.15  4972.1 1300.19
  4978.8 1297.87    4993  1292.4  5000.4 1291.16  5021.5 1292.49    5050 1298.52
  5070.9 1302.98    5109 1306.07  5326.4 1311.16  5404.3 1315.05  5447.1 1321.85
  5461.3 1322.28  5482.2 1326.09  5532.6 1330.87  5539.2 1333.64  5563.7 1336.69
#Mann= 9 ,-1 , 0
  3201.1     .05       0  4125.3      .1       0  4168.6     .05       0
  4494.5     .16       0  4523.5     .05       0    4676     .16       0
  4978.8     .07       0    5050     .16       0    5109      .1       0
Bank Sta=4951.3,5070.9
XS Rating Curve= 0 ,0
Exp/Cntr=0.3,0.1

Type RM Length L Ch R = 1 ,111586  ,846,846,846
BEGIN DESCRIPTION:
CYPRESS CREEK 179.0
END DESCRIPTION:
XS GIS Cut Line= 4
      2915221.31     10114906.43      2914815.06     10113890.81
      2914471.31     10113375.18      2914148.78     10112407.58
#Sta/Elev= 30
    3676 1333.63  3803.8  1327.5  3941.1  1322.9  4055.9 1317.49  4132.3  1315.5
  4180.8 1312.75  4249.7 1310.55  4455.4 1306.19  4702.1 1302.56  4870.5 1301.18
  4895.7 1301.25  4937.8  1297.8  4946.6 1296.02  4958.8 1288.86  4994.6 1287.05
  5009.9  1290.1  5024.9 1295.34  5054.8 1296.95    5076 1297.05  5103.1 1295.92
    5199 1297.08  5433.3 1300.54  5853.4 1300.76  5960.3 1301.95    6138 1308.98
  6192.2  1312.4  6213.3 1314.63  6264.4 1316.05  6371.4 1323.55  6409.5  1325.3
#Mann= 5 ,-1 , 0
    3676     .05       0  4870.5      .1       0  4946.6     .07       0
  5024.9      .1       0    5199     .05       0
Bank Sta=4937.8,5054.8
XS Rating Curve= 0 ,0
Exp/Cntr=0.3,0.1

Type RM Length L Ch R = 1 ,110740  ,822,822,822
BEGIN DESCRIPTION:
CYPRESS CREEK 178.0
END DESCRIPTION:
XS GIS Cut Line= 3
      2916106.73      10113948.1       2915028.6     10112869.97
        2914388.     10112135.62
#Sta/Elev= 30
  3766.8 1304.72  3987.9 1303.31  4122.2 1300.93  4270.7 1300.16  4532.3  1294.7
  4871.7 1293.23  4896.4 1292.27  4914.2 1291.59  4949.5  1290.2  4956.6 1289.01
  4970.7 1287.29  4977.8 1285.38  4998.8 1283.23  5013.2 1284.09  5041.5 1288.88
  5069.7  1292.6  5090.9  1296.2    5134 1296.94  5168.7 1296.21  5302.9 1297.31
    5544 1297.34    5750 1299.16  5834.5 1301.46  5926.6  1305.6  5962.7 1307.71
  5997.8  1311.2  6026.3 1312.16  6086.7 1316.25  6161.1 1320.37    6266 1323.93
#Mann= 6 ,-1 , 0
  3766.8     .05       0  4896.4     .16       0  4956.6     .07       0
  5041.5     .16       0    5134     .05       0  6086.7      .1       0
Bank Sta=4914.2,5069.7
XS Rating Curve= 0 ,0
Exp/Cntr=0.3,0.1

Type RM Length L Ch R = 1 ,109918  ,1048,1048,1048
BEGIN DESCRIPTION:
CYPRESS CREEK 177.0
END DESCRIPTION:
XS GIS Cut Line= 3
      2916481.71      10113911.6      2915809.85     10112416.85
      2914742.82     10112021.27
#Sta/Elev= 30
    3623 1304.08  3813.2 1298.43  4055.8 1294.79    4177 1293.91  4212.7 1294.85
    4500 1291.31  4760.3 1286.49  4812.1 1289.09  4875.6 1288.59  4892.5 1287.58
  4910.2 1285.86  4969.2 1285.61  4979.7 1284.33  4988.1  1279.6  4990.9  1279.1
    5037 1285.32  5045.9 1287.48  5060.1 1289.94  5083.3 1291.44  5148.5 1291.33
  5258.4 1292.12  5266.3 1292.21  5473.6 1294.96  5612.4 1296.76  5737.9 1297.96
  5999.1 1300.79  6127.2 1305.68  6169.8  1309.1  6206.4 1308.44  6399.8  1315.2
#Mann= 10 ,-1 , 0
    3623     .05       0  4875.6     .16       0  4969.2     .07       0
    5037     .16       0  5148.5      .1       0  5258.4     .05       0
  5266.3      .1       0  5473.6     .05       0  5612.4      .1       0
  5737.9     .05       0
Bank Sta=4892.5,5045.9
XS Rating Curve= 0 ,0
Exp/Cntr=0.3,0.1

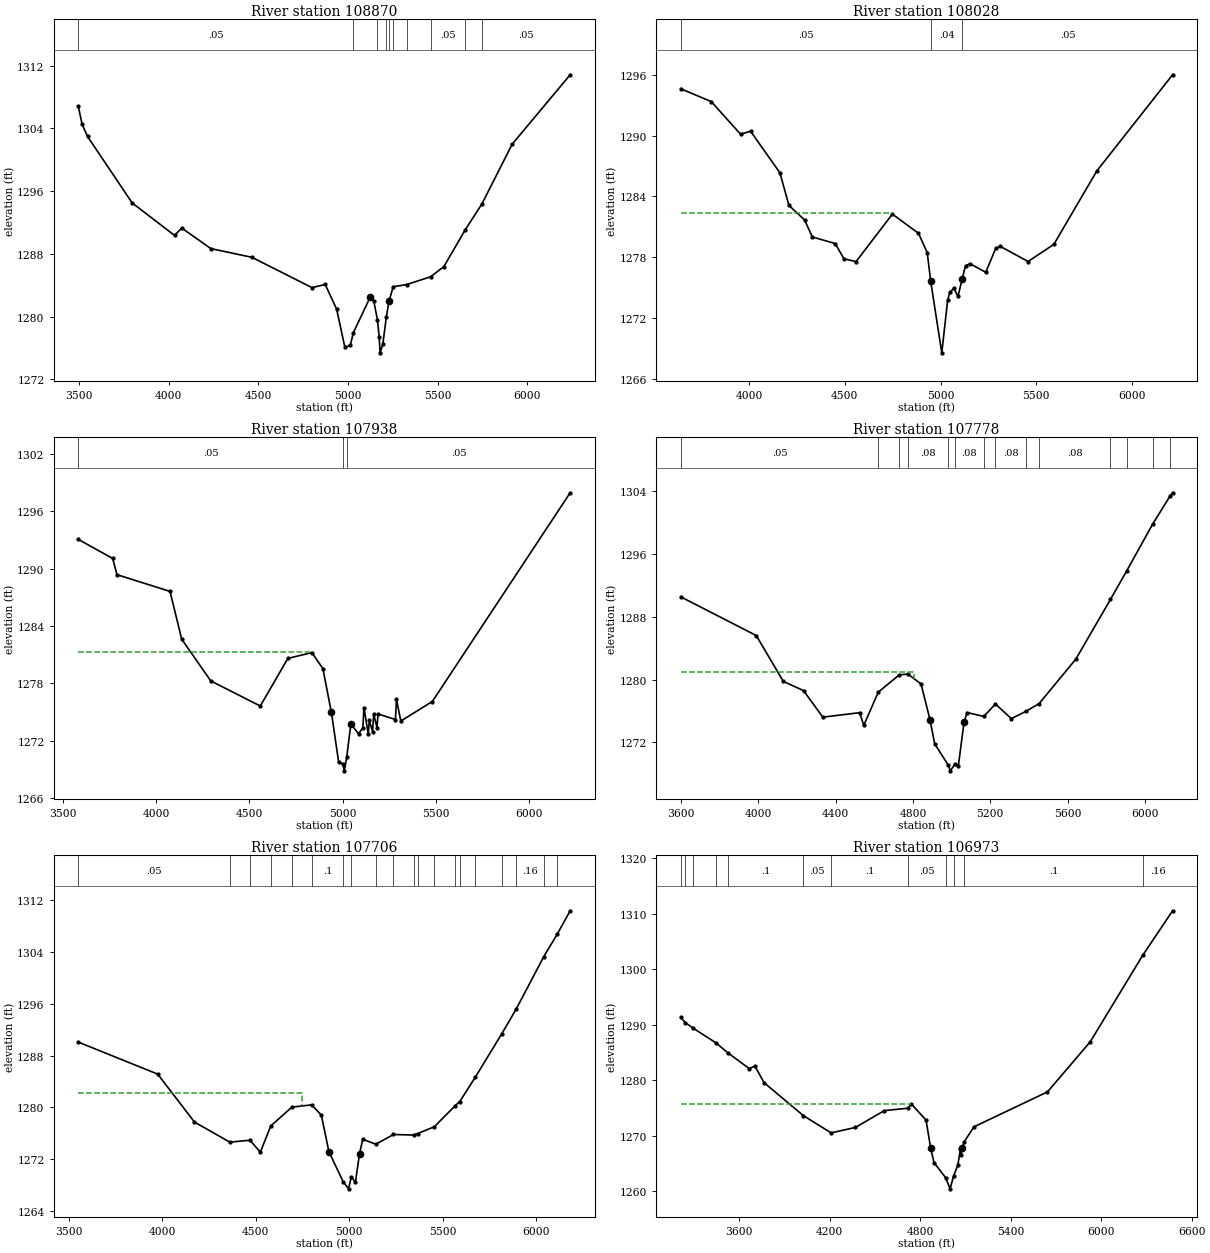
Type RM Length L Ch R = 1 ,108870  ,842,842,842
BEGIN DESCRIPTION:
CYPRESS CREEK 176.0
END DESCRIPTION:
XS GIS Cut Line= 3
      2917148.39     10113984.56      2916908.81     10112396.01
      2916830.68     10111260.61
#Sta/Elev= 30
  3495.1  1306.8  3516.2 1304.52  3546.5 1302.97  3795.3  1294.5  4031.9 1290.35
  4072.4 1291.29  4234.2 1288.67  4464.3 1287.55  4798.8 1283.69  4872.8 1284.09
  4936.7 1280.93  4982.6 1276.06  5012.9 1276.33  5029.7 1277.94  5123.9 1282.48
    5144 1281.96    5164 1279.61  5174.1 1277.41    5179 1275.37  5194.1 1276.46
  5214.2 1279.99  5228.3 1281.93  5252.3  1283.8  5327.2 1284.08  5460.5 1285.07
  5534.9 1286.37  5652.7 1291.01  5747.3 1294.37  5915.8 1301.98  6239.7 1310.84
#Mann= 10 ,-1 , 0
  3495.1     .05       0  5029.7     .16       0    5164    .035       0
  5214.2     .16       0  5228.3     .05       0  5252.3     .16       0
  5327.2      .1       0  5460.5     .05       0  5652.7      .1       0
  5747.3     .05       0
Bank Sta=5123.9,5228.3
XS Rating Curve= 0 ,0
Exp/Cntr=0.3,0.1

Type RM Length L Ch R = 1 ,108028  ,90,90,90
BEGIN DESCRIPTION:
CYPRESS CREEK 175.0
END DESCRIPTION:
XS GIS Cut Line= 3
      2918285.54     10113725.87      2917595.44     10112102.61
      2917239.52     10111382.09
#Sta/Elev= 30
  3643.9 1294.61  3803.2 1293.35  3955.9 1290.14  4008.6 1290.42  4161.4 1286.34
  4208.7 1283.12  4290.5 1281.68  4330.8 1280.01  4450.3 1279.36  4495.9 1277.86
    4559 1277.58  4748.7 1282.26    4885 1280.37  4930.5 1278.47  4948.7 1275.65
  5006.6 1268.59  5037.1 1273.76    5048 1274.54  5069.7 1274.94  5091.4 1274.15
  5113.2  1275.9  5130.6 1277.17  5154.2 1277.37    5236 1276.53  5288.7 1278.91
  5312.4 1279.08    5457 1277.59  5591.7 1279.28  5816.1 1286.52  6211.4 1295.99
#Mann= 3 , 0 , 0
  3643.9     .05       0  4948.7     .04       0  5113.2     .05       0
#XS Ineff= 2 , 0
         4747.73 1282.35
Permanent Ineff=
       T       T
Bank Sta=4948.7,5113.2
XS Rating Curve= 0 ,0
Exp/Cntr=0.3,0.1

Type RM Length L Ch R = 1 ,107938  ,160,160,160
BEGIN DESCRIPTION:
CYPRESS CREEK 174.0
END DESCRIPTION:
XS GIS Cut Line= 3
      2918441.81     10113725.91      2917864.54     10112501.92
      2917348.69     10111327.18
#Sta/Elev= 30
  3583.2 1293.04  3767.5 1291.05  3790.2 1289.36  4074.6 1287.61  4137.4 1282.62
  4293.2 1278.26  4558.5 1275.64  4706.2 1280.61    4835 1281.22    4894 1279.55
  4939.6 1274.98  4978.2 1269.83    5000 1269.59  5009.4 1268.87  5021.9 1270.32
  5043.9 1273.76  5085.2 1272.75  5108.5 1273.37    5114 1275.47  5137.3 1272.72
  5142.8 1274.14  5160.7 1272.97  5166.2 1274.79  5184.1 1273.39  5189.5 1274.81
    5283 1274.23  5288.4 1276.33  5311.8 1274.07  5480.6 1276.11  6219.5 1297.91
#Mann= 3 ,-1 , 0
  3583.2     .05       0    5000     .04       0  5021.9     .05       0
#XS Ineff= 2 , 0
         4834.66  1281.3
Permanent Ineff=
       T       T
Bank Sta=4939.6,5043.9
XS Rating Curve= 0 ,0
Exp/Cntr=0.3,0.1

Type RM Length L Ch R = 1 ,107778  ,72,72,72
BEGIN DESCRIPTION:
CYPRESS CREEK 172.0
END DESCRIPTION:
XS GIS Cut Line= 2
      2918535.55     10113652.11      2917525.14     10111318.79
#Sta/Elev= 30
  3599.8 1290.55  3990.3 1285.62    4130 1279.78  4234.9  1278.6  4334.2 1275.22
  4524.3 1275.79  4546.1 1274.18  4620.8  1278.4    4730 1280.62  4774.5  1280.7
    4842 1279.46  4888.9 1274.85  4912.4 1271.83    4982 1269.14  4993.5 1268.38
  5017.2 1269.24  5035.2 1269.05  5064.2 1274.56  5080.1 1275.81  5166.6 1275.31
  5226.6  1276.9  5308.9 1275.03  5384.9 1275.97  5452.7 1276.95  5642.4 1282.62
  5821.5 1290.23  5904.8 1293.84  6039.8 1299.83  6130.9 1303.46  6142.5 1303.81
#Mann= 14 ,-1 , 0
  3599.8     .05       0  4620.8     .08       0    4730     .05       0
  4774.5     .08       0    4982     .07       0  5017.2     .08       0
  5166.6     .05       0  5226.6     .08       0  5384.9     .05       0
  5452.7     .08       0  5821.5     .05       0  5904.8     .08       0
  6039.8     .05       0  6130.9     .08       0
#XS Ineff= 2 , 0
         4807.39 1280.92
Permanent Ineff=
       T       T
Bank Sta=4888.9,5064.2
XS Rating Curve= 0 ,0
Exp/Cntr=0.3,0.1

Type RM Length L Ch R = 1 ,107706  ,733,733,733
BEGIN DESCRIPTION:
CYPRESS CREEK 173.0
END DESCRIPTION:
XS GIS Cut Line= 3
      2918580.69     10113678.14      2918298.57     10112918.58
      2917569.38     10111251.87
#Sta/Elev= 30
  3551.8 1290.07  3976.2 1285.12  4172.8 1277.71  4361.6 1274.61  4469.2  1274.9
  4525.1 1273.06  4580.3  1277.1  4693.5 1280.02    4799 1280.37  4850.9  1278.8
  4891.3 1273.15  4967.7 1268.49  4996.5 1267.39  5011.4 1269.24  5033.2 1268.41
    5055  1272.8  5072.4 1275.06  5142.2 1274.28  5236.5 1275.79  5345.8  1275.7
  5366.5 1275.94  5455.2 1276.99  5564.5 1280.18  5590.8 1280.88  5673.9 1284.64
  5815.2 1291.34  5892.6 1295.17  6039.5 1303.25  6111.3 1306.72  6181.3 1310.37
#Mann= 20 ,-1 , 0
  3551.8     .05       0  4361.6      .1       0  4469.2     .05       0
  4580.3      .1       0  4693.5     .05       0    4799      .1       0
  4967.7     .07       0  5011.4      .1       0  5142.2     .05       0
  5236.5     .16       0  5345.8      .1       0  5366.5     .05       0
  5455.2      .1       0  5564.5     .16       0  5590.8     .08       0
  5673.9      .1       0  5815.2     .05       0  5892.6     .16       0
  6039.5     .05       0  6111.3     .16       0
#XS Ineff= 2 , 0
         4746.02 1282.15
Permanent Ineff=
       T       T
Bank Sta=4891.3,5055
XS Rating Curve= 0 ,0
Exp/Cntr=0.3,0.1

Type RM Length L Ch R = 1 ,106973  ,1135,1135,1135
BEGIN DESCRIPTION:
CYPRESS CREEK 171.0
END DESCRIPTION:
XS GIS Cut Line= 4
      2918603.25     10113751.06      2918801.17     10112277.09
       2918509.5      10111657.3      2917780.36     10110850.03
#Sta/Elev= 30
  3213.6 1291.31  3244.4 1290.35  3295.5 1289.37  3449.1 1286.68  3524.5 1284.94
    3668 1282.07  3705.3 1282.52  3765.8 1279.54  4025.7 1273.61  4210.5 1270.48
  4371.2 1271.46  4562.8 1274.49  4719.3 1274.93  4742.8 1275.66  4839.5 1272.79
  4870.3  1267.7  4892.4 1265.13  4969.8 1262.39  4998.8 1260.39  5021.8 1262.68
  5050.2 1264.67  5067.4 1267.54    5073 1266.49  5080.3 1267.84  5091.6 1268.85
  5157.6 1271.58  5644.2 1277.87  5927.4 1286.89  6274.9 1302.47  6473.6 1310.53
#Mann= 12 ,-1 , 0
  3213.6     .08       0  3244.4     .05       0  3295.5      .1       0
  3449.1     .05       0  3524.5      .1       0  4025.7     .05       0
  4210.5      .1       0  4719.3     .05       0  4969.8    .035       0
  5021.8     .05       0  5091.6      .1       0  6274.9     .16       0
#XS Ineff= 2 , 0
         4742.05 1275.69
Permanent Ineff=
       T       T
Bank Sta=4870.3,5080.3
XS Rating Curve= 0 ,0
Exp/Cntr=0.3,0.1

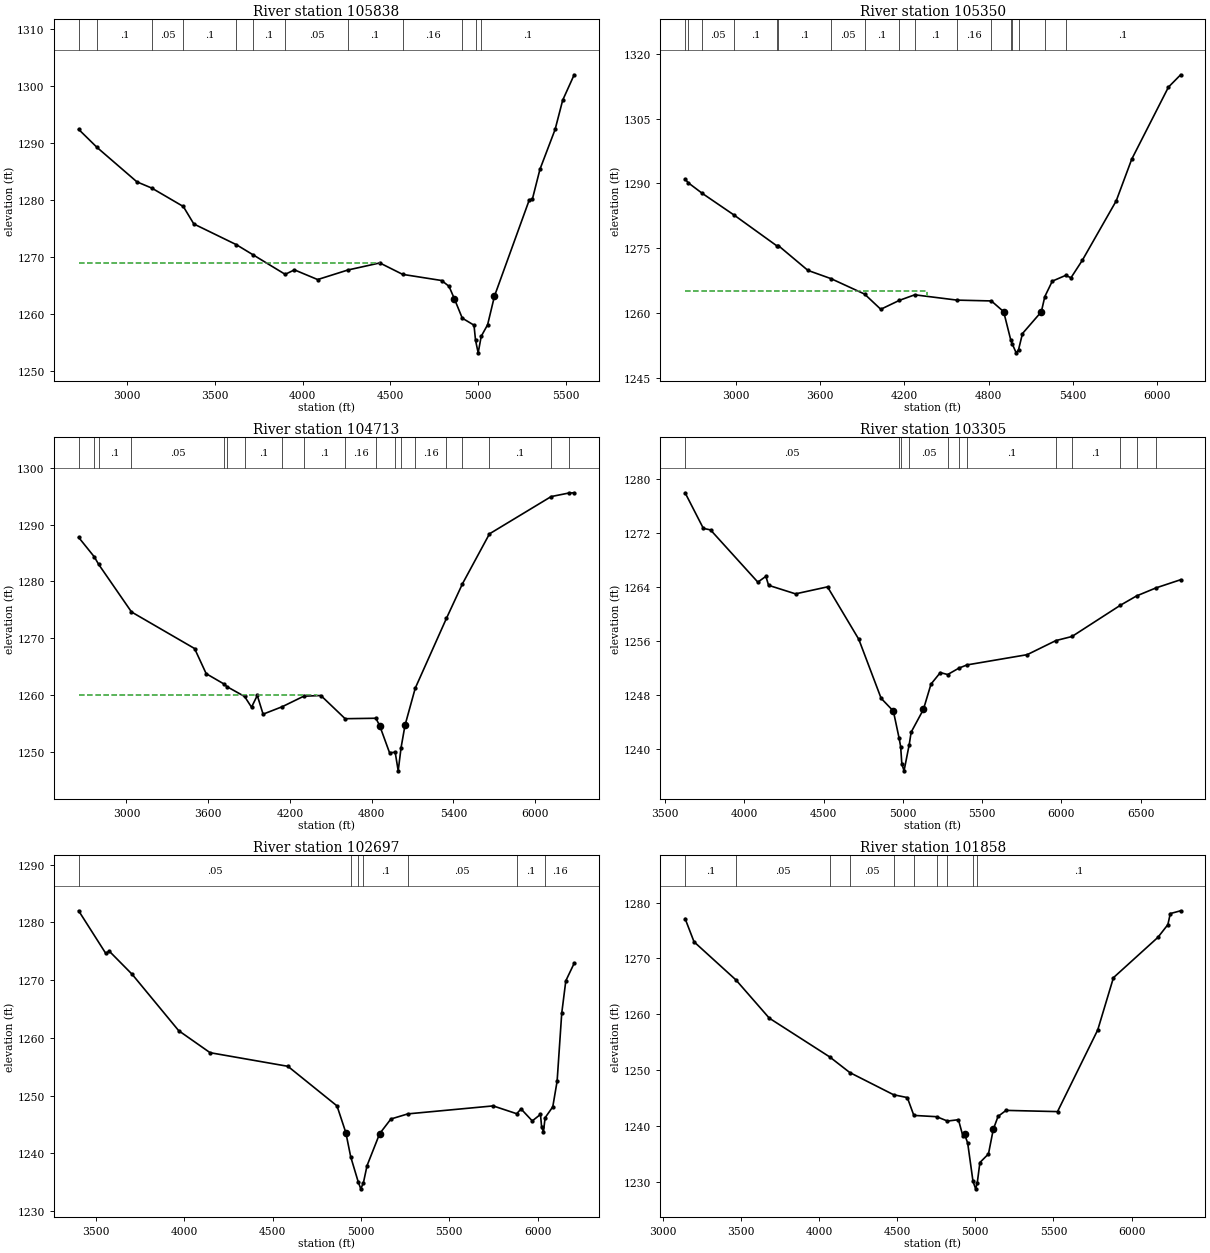
Type RM Length L Ch R = 1 ,105838  ,488,488,488
BEGIN DESCRIPTION:
CYPRESS CREEK 169.0
END DESCRIPTION:
XS GIS Cut Line= 3
      2918624.07     10113813.58      2919598.04     10112068.76
      2919910.54     10111303.14
#Sta/Elev= 30
  2722.3 1292.43  2827.7 1289.24  3054.7  1283.2  3139.1 1282.11  3319.1 1278.87
  3379.1  1275.8  3621.5 1272.16  3717.8 1270.36  3899.8 1266.95  3952.7 1267.73
    4085 1266.03  4257.6 1267.71  4439.4 1268.95  4569.6 1266.94    4792 1265.86
    4834 1264.84  4864.1 1262.68  4909.5 1259.25  4976.4 1258.01  4985.2 1255.34
  5000.2 1253.15  5017.6 1256.06  5053.9 1258.08  5093.2 1263.13  5291.8 1280.05
  5309.2 1280.16  5352.4 1285.41  5438.8 1292.41  5482.1 1297.56  5547.5 1302.02
#Mann= 12 ,-1 , 0
  2722.3     .05       0  2827.7      .1       0  3139.1     .05       0
  3319.1      .1       0  3621.5     .05       0  3717.8      .1       0
  3899.8     .05       0  4257.6      .1       0  4569.6     .16       0
  4909.5      .1       0  4985.2     .07       0  5017.6      .1       0
#XS Ineff= 2 , 0
         4440.91    1269
Permanent Ineff=
       T       T
Bank Sta=4864.1,5093.2
XS Rating Curve= 0 ,0
Exp/Cntr=0.3,0.1

Type RM Length L Ch R = 1 ,105350  ,637,637,637
BEGIN DESCRIPTION:
CYPRESS CREEK 168.0
END DESCRIPTION:
XS GIS Cut Line= 4
      2918691.81     10113849.98      2919999.09     10112297.92
      2920316.79     10111662.51       2920233.6     10110877.37
#Sta/Elev= 30
  2638.5 1290.99  2660.3 1290.14  2761.1 1287.67  2987.6 1282.65  3296.1 1275.43
  3302.6 1275.59  3513.2 1269.85  3677.6 1267.94  3916.7 1264.37  4032.1 1260.85
  4164.9 1262.92  4274.1  1264.2  4575.3 1262.97  4819.6 1262.78  4907.2  1260.3
    4957 1253.85  4968.5 1252.83  4996.4 1250.77  5013.2 1251.49  5041.4 1255.24
  5175.6 1260.27  5200.4 1263.79  5253.6 1267.36  5347.9 1268.68    5387 1268.16
  5467.4 1272.18  5708.8 1285.93  5819.4 1295.59  6080.9 1312.27  6167.7 1315.12
#Mann= 17 ,-1 , 0
  2638.5     .08       0  2660.3      .1       0  2761.1     .05       0
  2987.6      .1       0  3296.1     .05       0  3302.6      .1       0
  3677.6     .05       0  3916.7      .1       0  4164.9     .05       0
  4274.1      .1       0  4575.3     .16       0  4819.6     .05       0
    4957      .1       0  4968.5     .07       0  5013.2      .1       0
  5200.4     .05       0  5347.9      .1       0
#XS Ineff= 2 , 0
         4363.64 1264.98
Permanent Ineff=
       T       T
Bank Sta=4907.2,5175.6
XS Rating Curve= 0 ,0
Exp/Cntr=0.3,0.1

Type RM Length L Ch R = 1 ,104713  ,1408,1408,1408
BEGIN DESCRIPTION:
CYPRESS CREEK 167.0
END DESCRIPTION:
XS GIS Cut Line= 4
      2918993.84     10113912.54      2920535.54     10112485.42
      2920894.92     10112042.72      2921217.83     10111131.27
#Sta/Elev= 30
  2648.6 1287.76  2763.8 1284.32  2795.3 1283.01  3036.7 1274.61  3499.9 1268.16
    3585 1263.73  3712.8 1261.95  3739.1 1261.42    3867 1259.71  3917.8 1257.82
  3960.3 1259.89  4002.8 1256.59  4143.8 1257.91  4301.4 1259.76  4426.9 1259.88
  4605.2 1255.79  4830.9 1255.87  4859.1 1254.55    4931  1249.8  4972.6 1249.87
  4994.7  1246.6  5015.8 1250.69  5044.5 1254.61  5119.8 1261.17  5348.4 1273.46
  5466.6 1279.58  5664.7 1288.38  6117.6 1294.95  6246.2 1295.57  6286.6 1295.62
#Mann= 19 ,-1 , 0
  2648.6      .1       0  2763.8     .05       0  2795.3      .1       0
  3036.7     .05       0  3712.8      .1       0  3739.1     .05       0
    3867      .1       0  4143.8     .16       0  4301.4      .1       0
  4605.2     .16       0  4830.9      .1       0  4972.6     .07       0
  5015.8      .1       0  5119.8     .16       0  5348.4      .1       0
  5466.6     .16       0  5664.7      .1       0  6117.6     .05       0
  6246.2      .1       0
#XS Ineff= 2 , 0
            4400 1260.05
Permanent Ineff=
       T       T
Bank Sta=4859.1,5044.5
XS Rating Curve= 0 ,0
Exp/Cntr=0.3,0.1

Type RM Length L Ch R = 1 ,103305  ,608,608,608
BEGIN DESCRIPTION:
CYPRESS CREEK 165.0
END DESCRIPTION:
XS GIS Cut Line= 4
      2919811.57     10114100.01      2920926.17     10113558.34
      2921332.42     10113391.67      2921775.12     10112011.49
#Sta/Elev= 30
  3625.2    1278  3740.5 1272.71  3785.6 1272.49  4084.4 1264.73  4135.1 1265.59
  4152.1 1264.26  4322.2 1262.99  4524.1 1264.03  4721.6 1256.24  4862.5 1247.48
  4939.8 1245.58  4976.2 1241.54  4985.8  1240.3  4993.2 1237.73  5007.2 1236.71
  5039.9 1240.61    5052 1242.45  5129.3 1245.82  5177.3 1249.59  5236.1  1251.3
  5282.5 1251.01  5354.1 1251.97  5404.8 1252.44  5784.5 1253.96  5965.3 1256.05
  6067.2 1256.66  6372.8  1261.3  6474.6 1262.68    6598 1263.88    6753 1265.09
#Mann= 12 ,-1 , 0
  3625.2     .05       0  4976.2      .1       0  4985.8    .035       0
  5039.9     .05       0  5282.5      .1       0  5354.1     .16       0
  5404.8      .1       0  5965.3     .05       0  6067.2      .1       0
  6372.8     .16       0  6474.6      .1       0    6598     .16       0
Bank Sta=4939.8,5129.3
XS Rating Curve= 0 ,0
Exp/Cntr=0.3,0.1

Type RM Length L Ch R = 1 ,102697  ,839,839,839
BEGIN DESCRIPTION:
CYPRESS CREEK 163.0
END DESCRIPTION:
XS GIS Cut Line= 4
      2919775.17     10114271.88      2921191.79     10114188.55
      2921478.25     10113823.97      2922353.23      10113527.1
#Sta/Elev= 30
  3400.7 1282.03  3554.3 1274.65  3574.3 1275.03  3704.5    1271  3967.6 1261.25
  4145.3 1257.44    4586 1255.08  4864.1 1248.22  4914.1 1243.59  4941.8 1239.39
  4984.6 1235.02  4998.8 1233.85  5013.5 1234.88  5034.3 1237.87  5105.7 1243.41
  5169.3 1245.95  5265.6 1246.84  5748.3 1248.22  5881.6 1246.87  5906.7 1247.69
  5970.1 1245.62  6016.6 1246.75  6022.9 1244.59  6033.4 1243.73  6042.8 1246.17
  6086.2 1248.06  6110.8  1252.5  6136.9 1264.27  6160.1  1269.9  6207.4 1272.93
#Mann= 7 ,-1 , 0
  3400.7     .05       0  4941.8      .1       0  4984.6     .07       0
  5013.5      .1       0  5265.6     .05       0  5881.6      .1       0
  6042.8     .16       0
Bank Sta=4914.1,5105.7
XS Rating Curve= 0 ,0
Exp/Cntr=0.3,0.1

Type RM Length L Ch R = 1 ,101858  ,645,645,645
BEGIN DESCRIPTION:
CYPRESS CREEK 162.0
END DESCRIPTION:
XS GIS Cut Line= 4
      2919931.37     10114902.09      2921467.84     10114771.88
      2922045.96     10114646.88      2922587.62     10113761.48
#Sta/Elev= 30
  3142.5 1277.12  3199.8 1272.96  3467.7 1266.15  3681.5  1259.3  4067.8 1252.37
  4196.6 1249.57  4476.7  1245.6  4564.7 1245.09  4606.5  1241.9  4752.5 1241.67
  4821.7 1240.89  4891.8 1241.13  4920.4 1238.21  4930.7 1238.56  4951.1 1236.94
  4985.1 1230.08    5002 1228.76  5012.5 1229.87  5029.2 1233.47  5084.1 1235.01
  5114.8  1239.4  5145.5 1241.73  5196.7  1242.8    5526 1242.58  5783.2 1257.19
  5883.9 1266.55  6168.3 1273.76  6232.2 1276.04  6247.6 1278.02  6313.9 1278.52
#Mann= 10 ,-1 , 0
  3142.5      .1       0  3467.7     .05       0  4067.8      .1       0
  4196.6     .05       0  4476.7      .1       0  4606.5     .05       0
  4752.5      .1       0  4821.7     .05       0  4985.1    .035       0
  5012.5      .1       0
Bank Sta=4930.7,5114.8
XS Rating Curve= 0 ,0
Exp/Cntr=0.3,0.1

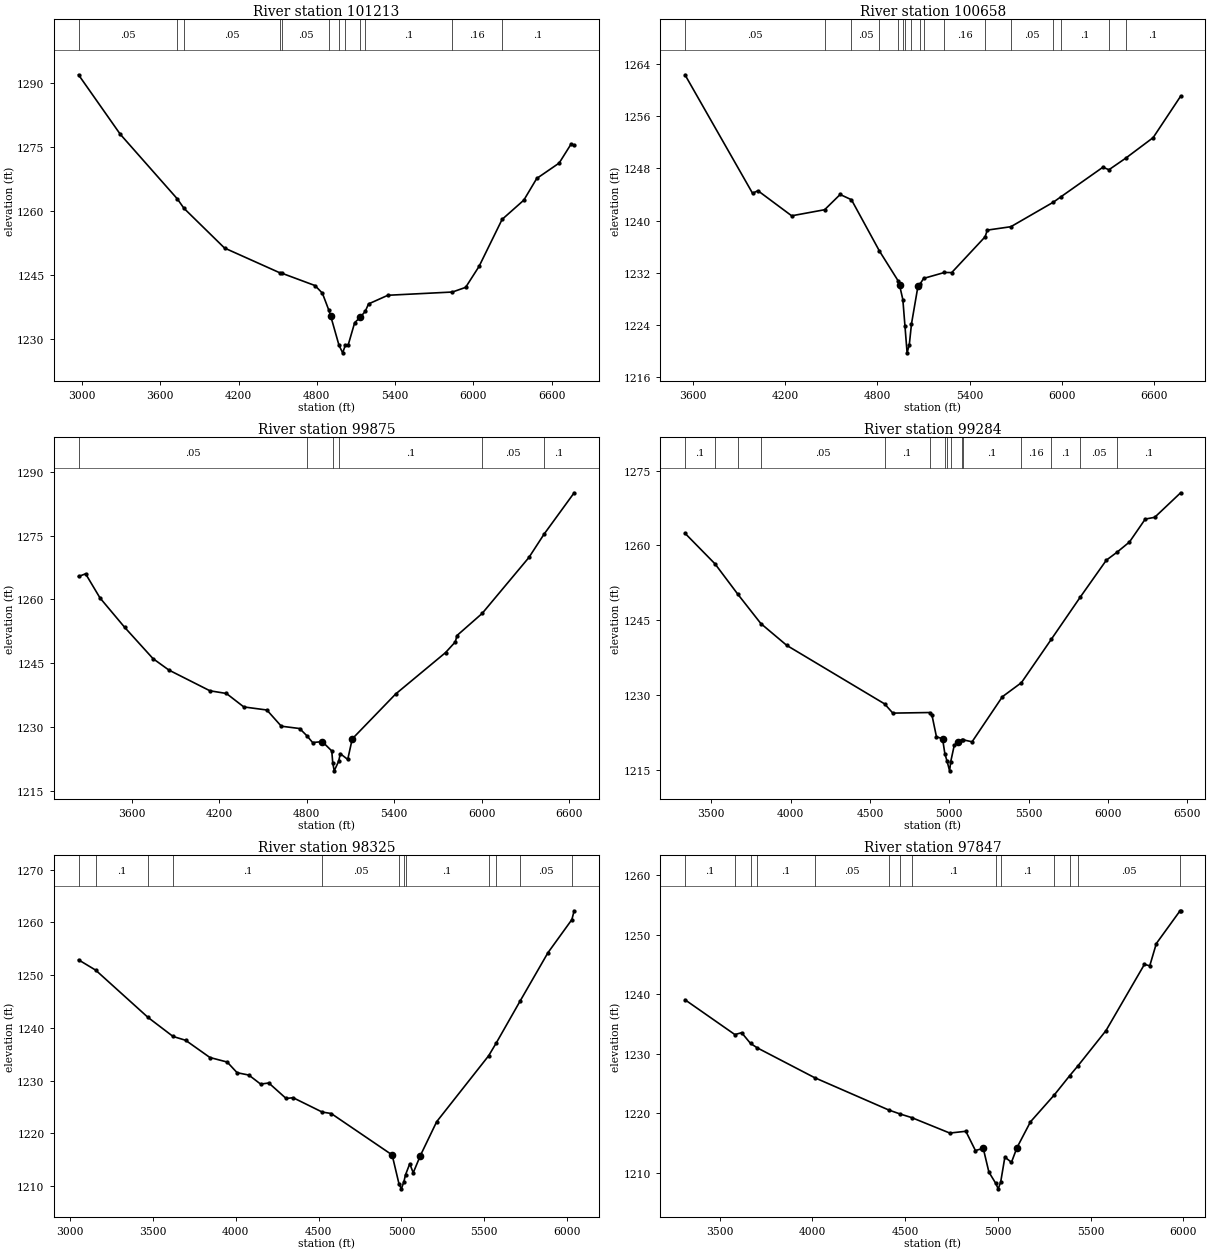
Type RM Length L Ch R = 1 ,101213  ,555,555,555
BEGIN DESCRIPTION:
CYPRESS CREEK 161.0
END DESCRIPTION:
XS GIS Cut Line= 4
      2920124.08     10116329.18      2921644.92     10115542.72
      2922176.17     10115053.13      2922774.28      10113825.7
#Sta/Elev= 30
  2972.9 1291.86  3293.1 1277.93  3730.7 1262.79  3781.4 1260.59  4092.4 1251.29
  4514.8 1245.51  4534.5 1245.36  4785.7 1242.51  4842.4 1240.73    4892 1236.74
  4906.5 1235.35    4970 1228.52  4998.1 1226.75  5019.3 1228.59  5040.9 1228.64
  5090.2 1233.82  5132.7 1235.06  5134.2 1235.14  5171.4 1236.47  5196.2  1238.2
  5344.8 1240.23  5839.3 1240.99  5940.8 1242.08  6043.5 1246.98  6220.5    1258
  6387.1 1262.51  6485.9 1267.58  6657.6 1271.18  6747.7 1275.56  6772.9 1275.31
#Mann= 12 ,-1 , 0
  2972.9     .05       0  3730.7      .1       0  3781.4     .05       0
  4514.8      .1       0  4534.5     .05       0    4892      .1       0
    4970    .035       0  5019.3      .1       0  5134.2     .16       0
  5171.4      .1       0  5839.3     .16       0  6220.5      .1       0
Bank Sta=4906.5,5132.7
XS Rating Curve= 0 ,0
Exp/Cntr=0.3,0.1

Type RM Length L Ch R = 1 ,100658  ,783,783,783
BEGIN DESCRIPTION:
CYPRESS CREEK 159.0
END DESCRIPTION:
XS GIS Cut Line= 4
      2921088.53     10116374.29      2922238.67     10115705.91
      2922568.53     10115384.73      2923137.11     10114069.62
#Sta/Elev= 30
  3548.3  1262.3  3987.7 1244.17  4022.7 1244.56  4242.2 1240.72  4456.5 1241.65
  4557.4 1243.98  4630.9 1243.18  4813.2 1235.32  4935.3 1230.74  4943.6 1230.12
  4965.2  1227.9  4978.9 1223.86  4992.8 1219.75  5007.2    1221  5021.3 1224.17
  5063.8 1229.99    5079 1230.35  5100.3 1231.14    5236 1232.05    5283 1232.03
  5500.3 1237.51  5514.3 1238.53  5667.7 1239.05  5943.6  1242.8  5994.5 1243.65
  6266.1 1248.15  6305.5 1247.77  6414.7 1249.54  6592.9 1252.68  6771.7 1259.02
#Mann= 17 ,-1 , 0
  3548.3     .05       0  4456.5      .1       0  4630.9     .05       0
  4813.2      .1       0  4935.3     .05       0  4965.2      .1       0
  4978.9     .07       0  5021.3      .1       0    5079     .16       0
  5100.3      .1       0    5236     .16       0  5500.3      .1       0
  5667.7     .05       0  5943.6     .16       0  5994.5      .1       0
  6305.5     .16       0  6414.7      .1       0
Bank Sta=4943.6,5063.8
XS Rating Curve= 0 ,0
Exp/Cntr=0.3,0.1

Type RM Length L Ch R = 1 ,99875   ,591,591,591
BEGIN DESCRIPTION:
CYPRESS CREEK 158.0
END DESCRIPTION:
XS GIS Cut Line= 3
      2921071.11     10116643.42      2923371.48      10116092.2
      2924294.72     10115619.74
#Sta/Elev= 30
  3232.6 1265.39  3281.3 1266.02  3380.2 1260.35  3548.3  1253.5    3744 1246.11
  3852.8 1243.43  4134.8 1238.56  4247.9 1237.93  4367.3 1234.77  4525.6 1234.05
  4624.6 1230.25  4750.7  1229.7  4800.2 1228.01  4839.8 1226.41    4906 1226.63
  4971.1 1224.44    4978 1221.62    4988 1219.77  5019.1 1222.07  5029.4  1223.8
  5080.8 1222.45  5111.7 1227.27  5409.9 1237.81    5752 1247.52  5819.4 1250.04
  5830.7 1251.53  6003.6 1256.72  6324.7 1269.86  6428.4 1275.32  6635.2 1285.04
#Mann= 6 ,-1 , 0
  3232.6     .05       0  4800.2      .1       0    4978     .07       0
  5019.1      .1       0  6003.6     .05       0  6428.4      .1       0
Bank Sta=4906,5111.7
XS Rating Curve= 0 ,0
Exp/Cntr=0.3,0.1

Type RM Length L Ch R = 1 ,99284   ,959,959,959
BEGIN DESCRIPTION:
CYPRESS CREEK 157.0
END DESCRIPTION:
XS GIS Cut Line= 4
      2921331.59     10117125.18      2922581.55     10116973.27
      2923249.95     10116643.41       2924278.6      10116200.7
#Sta/Elev= 30
    3334 1262.45  3523.4 1256.31  3667.7  1250.2  3812.4 1244.34  3975.6 1239.97
  4592.4 1228.24  4644.3 1226.39  4876.2 1226.51  4890.8    1226  4919.2 1221.65
  4957.7 1221.25  4972.3 1218.24  4986.6  1216.7  5002.1 1214.82    5009 1216.63
  5031.5 1219.96  5053.9 1220.55  5080.8 1221.09  5084.8 1221.06  5143.7 1220.64
  5334.9 1229.68  5454.7 1232.49  5642.5 1241.16  5825.8 1249.65  5990.1 1257.05
  6055.6  1258.6  6135.8 1260.69  6235.4 1265.29  6294.9 1265.64  6458.4 1270.56
#Mann= 15 ,-1 , 0
    3334      .1       0  3523.4     .05       0  3667.7      .1       0
  3812.4     .05       0  4592.4      .1       0  4876.2     .16       0
  4972.3      .1       0  4986.6     .07       0    5009      .1       0
  5080.8     .16       0  5084.8      .1       0  5454.7     .16       0
  5642.5      .1       0  5825.8     .05       0  6055.6      .1       0
Bank Sta=4957.7,5053.9
XS Rating Curve= 0 ,0
Exp/Cntr=0.3,0.1

Type RM Length L Ch R = 1 ,98325   ,478,478,478
BEGIN DESCRIPTION:
CYPRESS CREEK 155.0
END DESCRIPTION:
XS GIS Cut Line= 4
      2921730.88     10118218.93      2923293.36      10117741.5
      2923814.19     10117290.11      2924139.66     10116708.61
#Sta/Elev= 30
  3052.3  1252.9  3155.6 1250.95    3472 1241.97  3622.5 1238.37    3698 1237.65
  3844.9 1234.38    3949 1233.52  4008.8  1231.5  4079.7 1231.05  4150.5 1229.34
    4200 1229.55  4304.5 1226.61  4346.4 1226.76  4521.8 1224.04  4576.4 1223.76
  4943.8 1215.91  4985.5 1210.38  4999.5 1209.48    5014 1210.75  5024.9 1212.17
  5050.1 1214.24    5071 1212.52  5113.8 1215.77  5212.5 1222.21  5526.1 1234.72
  5572.2 1237.16  5715.4 1245.07  5883.4 1254.24  6027.7 1260.52  6041.7  1262.2
#Mann= 12 ,-1 , 0
  3052.3     .05       0  3155.6      .1       0    3472     .05       0
  3622.5      .1       0  4521.8     .05       0  4985.5    .035       0
    5014     .05       0  5024.9      .1       0  5526.1     .05       0
  5572.2      .1       0  5715.4     .05       0  6027.7      .1       0
Bank Sta=4943.8,5113.8
XS Rating Curve= 0 ,0
Exp/Cntr=0.3,0.1

Type RM Length L Ch R = 1 ,97847   ,450,450,450
BEGIN DESCRIPTION:
CYPRESS CREEK 154.0
END DESCRIPTION:
XS GIS Cut Line= 4
      2922303.75     10118648.63      2923388.84     10118188.55
      2924065.93     10117754.52      2924608.42      10117329.2
#Sta/Elev= 30
  3312.8 1239.07  3581.7 1233.23  3618.3 1233.54  3666.2 1231.74    3703 1230.99
  4011.3    1226  4410.6 1220.58  4470.9 1219.92  4535.5 1219.29  4740.4  1216.7
    4827    1217  4878.6 1213.77  4920.9 1214.13  4951.3 1210.15  4987.6 1208.29
  5001.5 1207.34  5014.7 1208.45  5037.4 1212.66    5073 1211.79  5102.6 1214.25
  5175.3 1218.58  5304.2 1223.11  5387.5 1226.35  5431.1 1227.97  5582.7  1233.9
  5789.7    1245  5818.6 1244.77  5853.9  1248.5  5981.9    1254    5985    1254
#Mann= 14 ,-1 , 0
  3312.8      .1       0  3581.7     .16       0  3666.2     .05       0
    3703      .1       0  4011.3     .05       0  4410.6      .1       0
  4470.9     .05       0  4535.5      .1       0  4987.6     .07       0
  5014.7      .1       0  5304.2     .05       0  5387.5      .1       0
  5431.1     .05       0  5981.9      .1       0
Bank Sta=4920.9,5102.6
XS Rating Curve= 0 ,0
Exp/Cntr=0.3,0.1

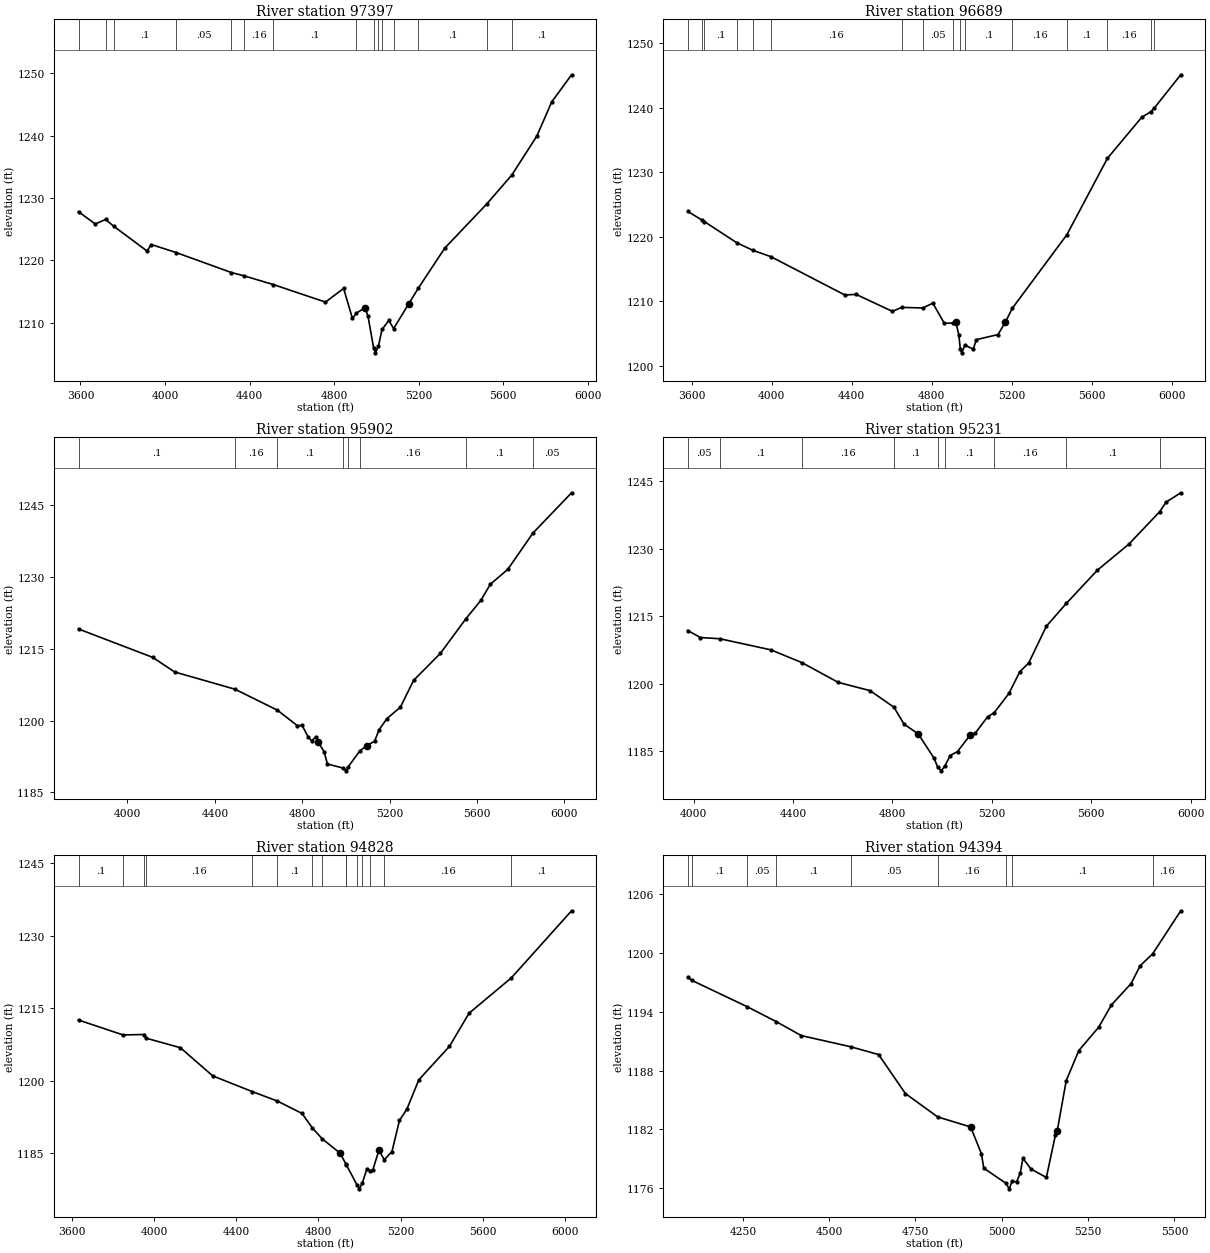
Type RM Length L Ch R = 1 ,97397   ,708,708,708
BEGIN DESCRIPTION:
CYPRESS CREEK 153.0
END DESCRIPTION:
XS GIS Cut Line= 3
      2922924.43     10119121.71      2924517.32     10117954.17
      2924790.77     10117724.12
#Sta/Elev= 30
  3590.6  1227.8    3670 1225.84  3718.7 1226.57  3756.5  1225.5  3914.4 1221.52
  3935.3 1222.55  4052.5 1221.27  4313.9 1218.07  4371.9 1217.56  4512.1 1216.15
  4758.8 1213.34  4844.5 1215.53  4886.2 1210.74  4905.4 1211.58  4944.9 1212.43
  4959.4 1211.18  4986.6 1205.98  4994.8 1205.22    5009 1206.25  5026.1 1208.96
  5058.6  1210.4  5081.1  1209.1  5151.7 1213.01  5198.6  1215.6  5323.1 1221.98
  5522.1 1229.06  5640.2 1233.68  5758.5  1239.9  5828.7 1245.37  5922.9 1249.72
#Mann= 15 ,-1 , 0
  3590.6      .1       0  3718.7     .05       0  3756.5      .1       0
  4052.5     .05       0  4313.9      .1       0  4371.9     .16       0
  4512.1      .1       0  4905.4     .16       0  4986.6     .07       0
    5009     .16       0  5026.1      .1       0  5081.1     .16       0
  5198.6      .1       0  5522.1     .16       0  5640.2      .1       0
Bank Sta=4944.9,5151.7
XS Rating Curve= 0 ,0
Exp/Cntr=0.3,0.1

Type RM Length L Ch R = 1 ,96689   ,787,787,787
BEGIN DESCRIPTION:
CYPRESS CREEK 152.0
END DESCRIPTION:
XS GIS Cut Line= 3
      2923328.04     10119568.78      2924729.99     10118652.96
      2925327.61     10118137.62
#Sta/Elev= 30
  3580.6 1223.91  3654.6 1222.51  3663.9 1222.32    3827 1219.02  3906.4 1217.87
  3995.8 1216.89  4365.2 1210.95  4422.5 1211.03  4603.5  1208.4  4649.8 1209.02
  4755.3 1208.93  4805.6 1209.67  4862.9 1206.55    4904 1206.59  4920.2 1206.72
  4935.3 1204.75  4942.8 1202.55  4950.2 1201.97  4965.5 1203.15  5007.7 1202.55
  5022.8 1204.01  5131.4 1204.81  5167.6 1206.72  5203.4 1208.91  5475.3 1220.29
    5678 1232.14  5848.7 1238.48  5894.5 1239.36  5912.4 1239.95  6044.3 1245.09
#Mann= 16 ,-1 , 0
  3580.6      .1       0  3654.6     .05       0  3663.9      .1       0
    3827     .05       0  3906.4      .1       0  3995.8     .16       0
  4649.8      .1       0  4755.3     .05       0    4904      .1       0
  4942.8     .07       0  4965.5      .1       0  5203.4     .16       0
  5475.3      .1       0    5678     .16       0  5894.5      .1       0
  5912.4     .16       0
Bank Sta=4920.2,5167.6
XS Rating Curve= 0 ,0
Exp/Cntr=0.3,0.1

Type RM Length L Ch R = 1 ,95902   ,671,671,671
BEGIN DESCRIPTION:
CYPRESS CREEK 150.0
END DESCRIPTION:
XS GIS Cut Line= 4
      2923792.47     10119677.27      2924756.03     10119542.72
      2925168.36     10119264.94      2925632.11     10118627.82
#Sta/Elev= 30
  3775.7 1219.14    4115 1213.22  4215.9 1210.16  4492.1 1206.56  4686.8 1202.17
  4777.7 1198.94  4799.8    1199  4828.6 1196.47  4843.6 1195.79  4864.6 1196.64
  4872.1 1195.61  4900.6 1193.48  4915.6 1190.93  4987.5 1190.08  5002.3  1189.5
  5008.5 1190.21  5063.6 1193.63  5095.5 1194.77  5131.5 1195.67  5152.5 1198.12
  5188.5 1200.43  5249.6 1202.79  5310.4 1208.41  5432.8 1214.03  5549.5 1221.26
  5618.3 1225.12  5661.9 1228.49  5741.5 1231.59  5856.6 1239.17  6033.8  1247.6
#Mann= 8 ,-1 , 0
  3775.7      .1       0  4492.1     .16       0  4686.8      .1       0
  4987.5     .07       0  5008.5      .1       0  5063.6     .16       0
  5549.5      .1       0  5856.6     .05       0
Bank Sta=4872.1,5095.5
XS Rating Curve= 0 ,0
Exp/Cntr=0.3,0.1

Type RM Length L Ch R = 1 ,95231   ,403,403,403
BEGIN DESCRIPTION:
CYPRESS CREEK 149.0
END DESCRIPTION:
XS GIS Cut Line= 4
      2924716.96     10120523.63      2925263.84     10120089.59
      2925784.68     10119373.45      2925949.62     10119008.83
#Sta/Elev= 30
  3976.4 1211.86  4027.8  1210.3  4105.6 1210.03  4311.3 1207.56  4435.7 1204.73
  4582.1 1200.33  4710.4 1198.49  4806.5  1194.8  4846.4 1191.08  4904.4 1188.85
  4967.7 1183.47  4982.4  1181.5  4996.8 1180.67  5011.7 1181.79  5032.6 1184.07
    5062 1184.96  5112.2 1188.57  5133.1 1189.03  5183.3 1192.69  5208.9 1193.54
  5269.1 1197.89  5312.5 1202.67  5348.7 1204.66  5419.8 1212.83    5500 1217.89
  5625.1 1225.28  5751.6 1231.06  5875.8 1238.28  5901.2 1240.38  5960.3 1242.47
#Mann= 9 ,-1 , 0
  3976.4     .05       0  4105.6      .1       0  4435.7     .16       0
  4806.5      .1       0  4982.4     .07       0  5011.7      .1       0
  5208.9     .16       0    5500      .1       0  5875.8     .05       0
Bank Sta=4904.4,5112.2
XS Rating Curve= 0 ,0
Exp/Cntr=0.3,0.1

Type RM Length L Ch R = 1 ,94828   ,434,434,434
BEGIN DESCRIPTION:
CYPRESS CREEK 148.0
END DESCRIPTION:
XS GIS Cut Line= 4
      2924773.36     10120975.03      2925598.04     10120323.97
       2926131.9      10119551.4      2926162.28     10119143.41
#Sta/Elev= 30
  3632.9 1212.55  3849.6 1209.47  3949.8 1209.56  3961.9  1208.8  4128.6 1206.83
  4285.7 1201.02  4477.6 1197.78  4600.4 1195.82  4720.4 1193.26  4770.1  1190.3
  4818.3 1188.03  4906.5 1185.02  4934.4 1182.75  4935.4 1182.69  4986.9 1178.58
  4999.7 1177.69    5014 1178.93  5036.4 1181.88  5050.5 1181.36  5064.7 1181.58
  5094.4 1185.66  5120.4  1183.7  5157.9 1185.38  5194.4 1191.81  5230.9 1194.18
  5288.4 1200.19  5437.8 1207.13  5533.1 1213.96  5738.3 1221.24  6031.8 1235.11
#Mann= 15 ,-1 , 0
  3632.9      .1       0  3849.6     .16       0  3949.8      .1       0
  3961.9     .16       0  4477.6     .05       0  4600.4      .1       0
  4770.1     .05       0  4818.3      .1       0  4934.4     .05       0
  4935.4      .1       0  4986.9     .07       0    5014      .1       0
  5050.5     .05       0  5120.4     .16       0  5738.3      .1       0
Bank Sta=4906.5,5094.4
XS Rating Curve= 0 ,0
Exp/Cntr=0.3,0.1

Type RM Length L Ch R = 1 ,94394   ,635,635,635
BEGIN DESCRIPTION:
CYPRESS CREEK 147.0
END DESCRIPTION:
XS GIS Cut Line= 3
      2925502.54     10120867.09       2926091.1     10120455.62
      2926320.26     10119783.76
#Sta/Elev= 30
  4090.3 1197.56  4101.9 1197.23  4262.4 1194.54  4347.5    1193    4419 1191.59
  4563.1 1190.44  4643.2 1189.65  4720.8 1185.67  4814.4 1183.28  4909.7 1182.26
  4941.1 1179.51  4947.8 1178.05  5011.2 1176.53  5021.5 1175.94  5029.8 1176.72
  5042.9 1176.65  5053.4 1177.54  5061.1 1179.05  5085.1 1177.95  5129.1  1177.1
  5155.2 1181.43  5160.4 1181.83  5186.5 1186.98  5223.1 1190.06  5280.5 1192.44
  5317.6 1194.72  5374.5  1196.9  5400.6 1198.71  5437.1 1199.95  5518.3 1204.33
#Mann= 9 ,-1 , 0
  4090.3     .16       0  4101.9      .1       0  4262.4     .05       0
  4347.5      .1       0  4563.1     .05       0  4814.4     .16       0
  5011.2     .07       0  5029.8      .1       0  5437.1     .16       0
Bank Sta=4909.7,5160.4
XS Rating Curve= 0 ,0
Exp/Cntr=0.3,0.1