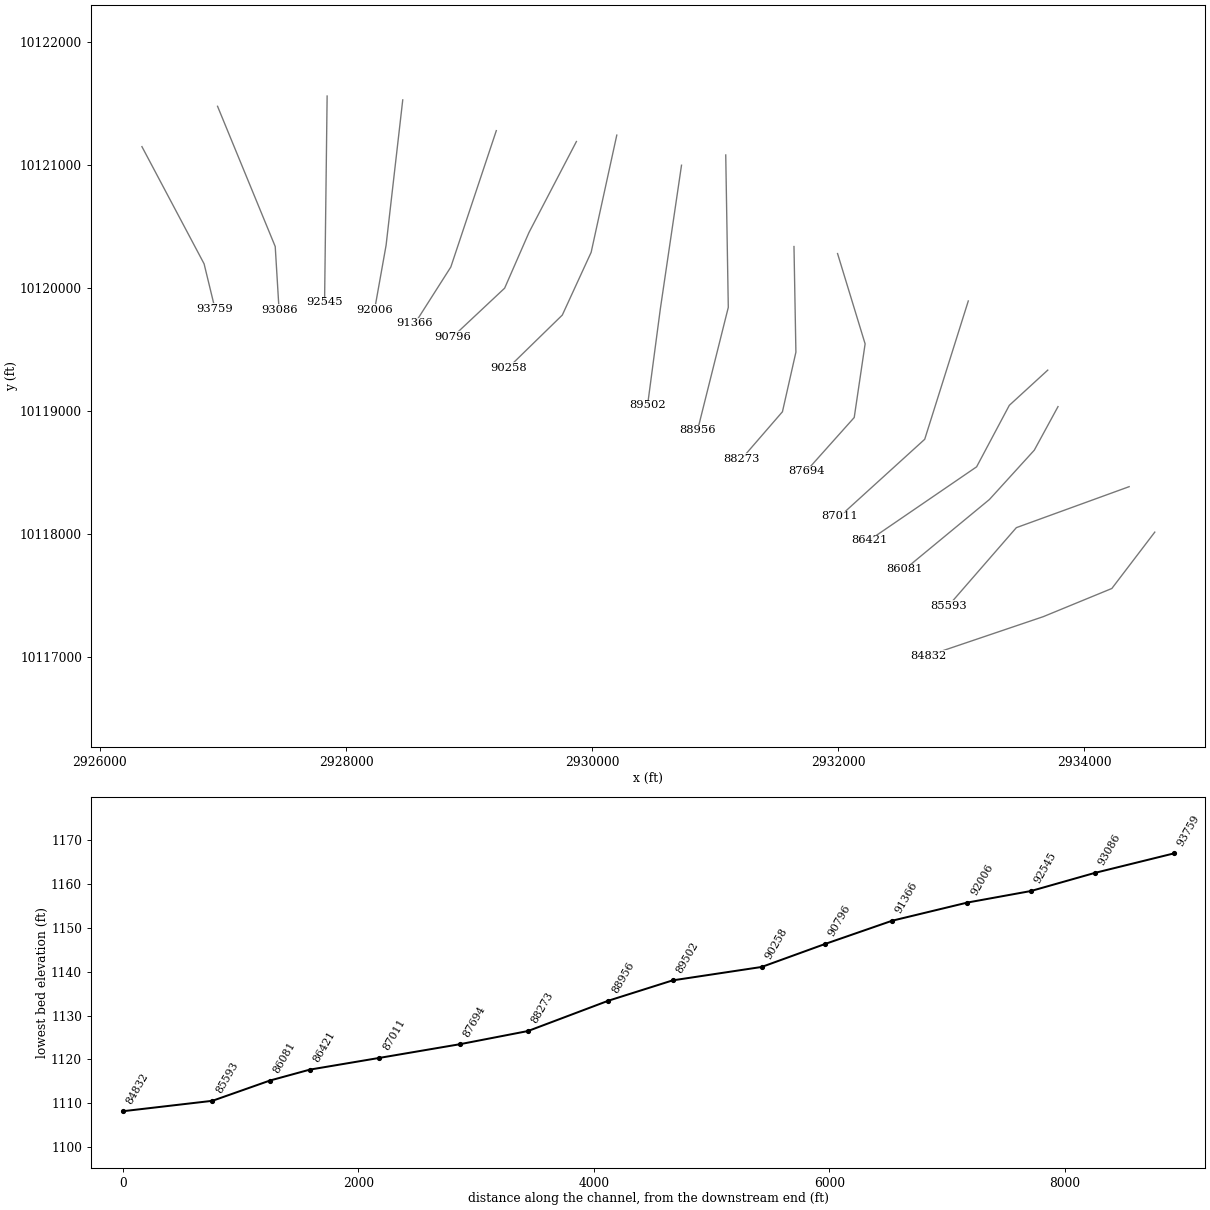
HEC-RAS study CYPRESS CREEK.prj: CYPRESS CREEK Base Level Engineering

--- CYPRESS CREEK.g01 (geometry) --- (continued)

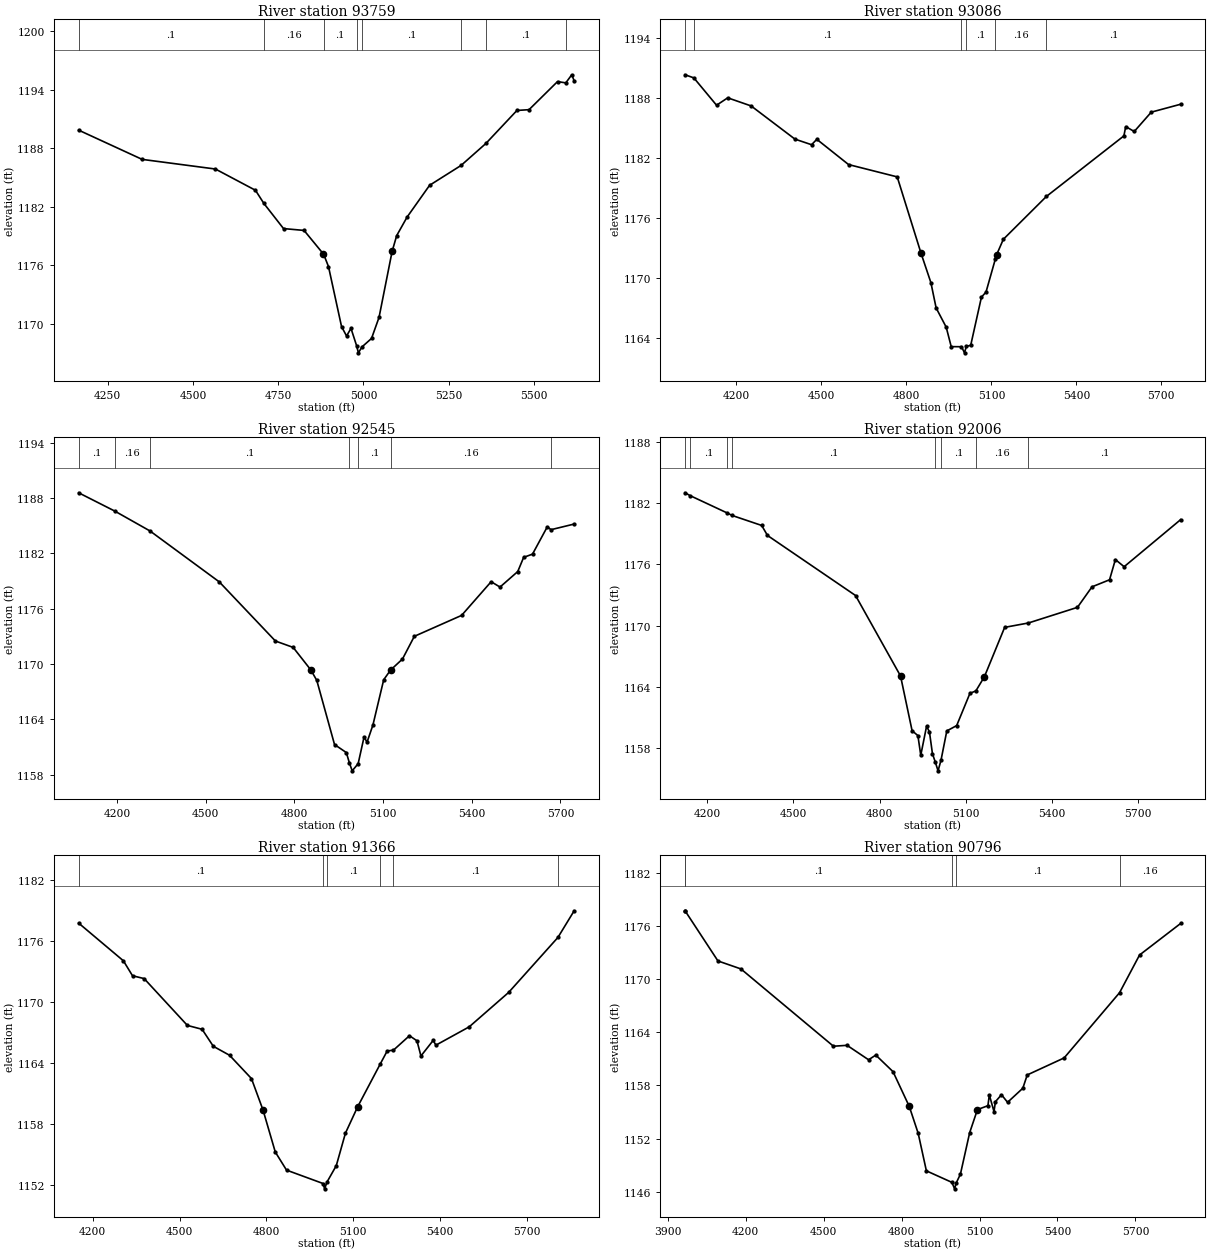
Type RM Length L Ch R = 1 ,93759   ,673,673,673
BEGIN DESCRIPTION:
CYPRESS CREEK 146.0
END DESCRIPTION:
XS GIS Cut Line= 3
      2926341.12      10121148.3      2926846.31      10120195.2
      2926934.85     10119830.61
#Sta/Elev= 30
  4164.4 1189.85  4350.7 1186.85  4565.7 1185.86  4683.2 1183.68  4707.9 1182.33
  4765.5 1179.75  4825.8 1179.56  4882.6 1177.14  4884.4 1177.01  4897.5 1175.85
  4935.8 1169.69  4950.5 1168.73  4963.5 1169.51  4979.8 1167.75  4985.2    1167
  4995.8 1167.61  5023.8 1168.48  5045.8 1170.64  5084.1  1177.4  5097.6 1179.03
  5128.1 1180.93  5194.1 1184.19  5286.5 1186.23  5359.2 1188.48  5450.4 1191.87
  5485.9 1191.95  5569.4 1194.83  5593.7  1194.7  5611.2 1195.53  5618.3 1194.91
#Mann= 8 ,-1 , 0
  4164.4      .1       0  4707.9     .16       0  4884.4      .1       0
  4979.8     .07       0  4995.8      .1       0  5286.5     .16       0
  5359.2      .1       0  5593.7     .16       0
Bank Sta=4882.6,5084.1
XS Rating Curve= 0 ,0
Exp/Cntr=0.3,0.1

Type RM Length L Ch R = 1 ,93086   ,541,541,541
BEGIN DESCRIPTION:
CYPRESS CREEK 145.0
END DESCRIPTION:
XS GIS Cut Line= 3
      2926955.67     10121476.49      2927424.43     10120335.83
      2927455.68      10119820.2
#Sta/Elev= 30
  4018.5 1190.29  4049.4 1189.98  4129.6 1187.25    4169 1187.99  4251.7 1187.18
  4406.3 1183.87  4465.1 1183.31  4483.6 1183.85  4595.7 1181.33  4767.5  1180.1
  4851.6 1172.48  4886.4 1169.55  4904.9 1167.02  4940.5  1165.1  4958.2 1163.16
  4994.5 1163.15  5005.1 1162.54  5011.6 1163.19    5027 1163.29  5064.9  1168.1
    5081  1168.6  5114.2 1171.92  5118.2 1172.31  5142.2 1173.87  5294.4 1178.15
  5567.9 1184.19  5574.4 1185.12  5604.5 1184.63  5664.6 1186.56  5768.3 1187.35
#Mann= 6 ,-1 , 0
  4018.5     .16       0  4049.4      .1       0  4994.5     .07       0
  5011.6      .1       0  5114.2     .16       0  5294.4      .1       0
Bank Sta=4851.6,5118.2
XS Rating Curve= 0 ,0
Exp/Cntr=0.3,0.1

Type RM Length L Ch R = 1 ,92545   ,539,539,539
BEGIN DESCRIPTION:
CYPRESS CREEK 144.0
END DESCRIPTION:
XS GIS Cut Line= 2
      2927846.31     10121559.79      2927825.48     10119882.72
#Sta/Elev= 30
  4069.4 1188.56  4190.9 1186.59    4311 1184.42  4545.5  1178.9  4735.5 1172.49
  4795.5  1171.8  4855.5 1169.35  4875.5 1168.22  4935.5 1161.27  4975.5  1160.4
  4985.5 1159.31  4995.3 1158.42  5015.5  1159.2  5035.5  1162.1  5045.5 1161.52
  5065.5 1163.39  5101.9 1168.29  5125.5 1169.36  5127.8 1169.42  5165.5 1170.54
  5205.6    1173  5365.6 1175.27  5465.6 1178.92  5495.6 1178.34  5555.6 1180.02
  5575.6 1181.56  5605.6 1181.91  5655.6 1184.87  5668.3 1184.56  5746.6 1185.17
#Mann= 7 ,-1 , 0
  4069.4      .1       0  4190.9     .16       0    4311      .1       0
  4985.5     .07       0  5015.5      .1       0  5127.8     .16       0
  5668.3      .1       0
Bank Sta=4855.5,5125.5
XS Rating Curve= 0 ,0
Exp/Cntr=0.3,0.1

Type RM Length L Ch R = 1 ,92006   ,640,640,640
BEGIN DESCRIPTION:
CYPRESS CREEK 143.0
END DESCRIPTION:
XS GIS Cut Line= 3
      2928460.89     10121528.54      2928325.48     10120346.25
      2928231.72     10119820.16
#Sta/Elev= 30
  4123.4 1183.02  4140.9 1182.74  4270.1 1181.04  4286.9  1180.8  4389.9 1179.82
  4410.1 1178.84  4716.5 1172.96  4873.1 1165.08  4913.3 1159.72  4933.5 1159.24
  4943.5 1157.32  4963.7 1160.16  4973.7  1159.6  4984.2 1157.46  4993.9 1156.66
  5003.7 1155.79    5014 1156.84  5034.1  1159.7  5068.4 1160.22  5114.6 1163.38
  5135.3 1163.62    5165 1165.01  5235.4 1169.84  5318.2 1170.27  5488.7  1171.8
  5539.4 1173.81  5600.4  1174.5  5620.7 1176.48  5651.2 1175.78  5847.8 1180.39
#Mann= 8 ,-1 , 0
  4123.4     .16       0  4140.9      .1       0  4270.1     .16       0
  4286.9      .1       0  4993.9     .07       0    5014      .1       0
  5135.3     .16       0  5318.2      .1       0
Bank Sta=4873.1,5165
XS Rating Curve= 0 ,0
Exp/Cntr=0.3,0.1

Type RM Length L Ch R = 1 ,91366   ,570,570,570
BEGIN DESCRIPTION:
CYPRESS CREEK 142.0
END DESCRIPTION:
XS GIS Cut Line= 3
       2929221.3      10121278.5      2928851.52     10120169.16
      2928559.86     10119710.84
#Sta/Elev= 30
    4151 1177.74  4305.6 1174.04  4337.2 1172.57  4377.4 1172.29  4526.9 1167.69
  4577.7 1167.31  4616.5 1165.64  4672.5 1164.76  4748.3 1162.47  4788.5 1159.36
  4830.6 1155.26  4869.5 1153.48    4996 1152.16    5001 1151.64  5009.8 1152.33
  5041.5 1153.92  5073.1 1157.11  5115.3  1159.7  5194.1 1163.94  5217.4 1165.18
    5239 1165.26  5294.4 1166.68  5320.3 1166.18    5334 1164.69  5376.4 1166.22
  5385.7 1165.75  5500.8 1167.55  5637.1 1170.93  5807.4 1176.33  5863.6 1178.95
#Mann= 6 ,-1 , 0
    4151      .1       0    4996     .07       0  5009.8      .1       0
  5194.1     .16       0    5239      .1       0  5807.4     .16       0
Bank Sta=4788.5,5115.3
XS Rating Curve= 0 ,0
Exp/Cntr=0.3,0.1

Type RM Length L Ch R = 1 ,90796   ,538,538,538
BEGIN DESCRIPTION:
CYPRESS CREEK 141.0
END DESCRIPTION:
XS GIS Cut Line= 4
      2929872.33     10121189.96      2929486.93     10120450.41
      2929289.02     10119997.29      2928867.15     10119601.46
#Sta/Elev= 30
    3967  1177.7  3967.3 1177.68  4093.4 1172.04  4181.8 1171.14  4537.8 1162.42
  4590.3 1162.52  4673.1 1160.89  4700.8 1161.42  4767.1 1159.55  4829.6 1155.63
  4863.9  1152.6  4895.5 1148.36  4993.7 1147.06  5004.1 1146.33  5009.8 1146.96
  5026.5 1147.99  5062.1 1152.67    5092 1155.27  5132.3 1155.71  5137.7 1156.93
  5155.7 1155.04  5161.1 1156.16  5184.5 1156.95  5207.9 1156.09  5266.6 1157.68
  5283.6 1159.18  5425.6  1161.1  5638.9 1168.46  5715.8 1172.71  5873.9 1176.27
#Mann= 5 ,-1 , 0
    3967     .16       0  3967.3      .1       0  4993.7     .07       0
  5009.8      .1       0  5638.9     .16       0
Bank Sta=4829.6,5092
XS Rating Curve= 0 ,0
Exp/Cntr=0.3,0.1

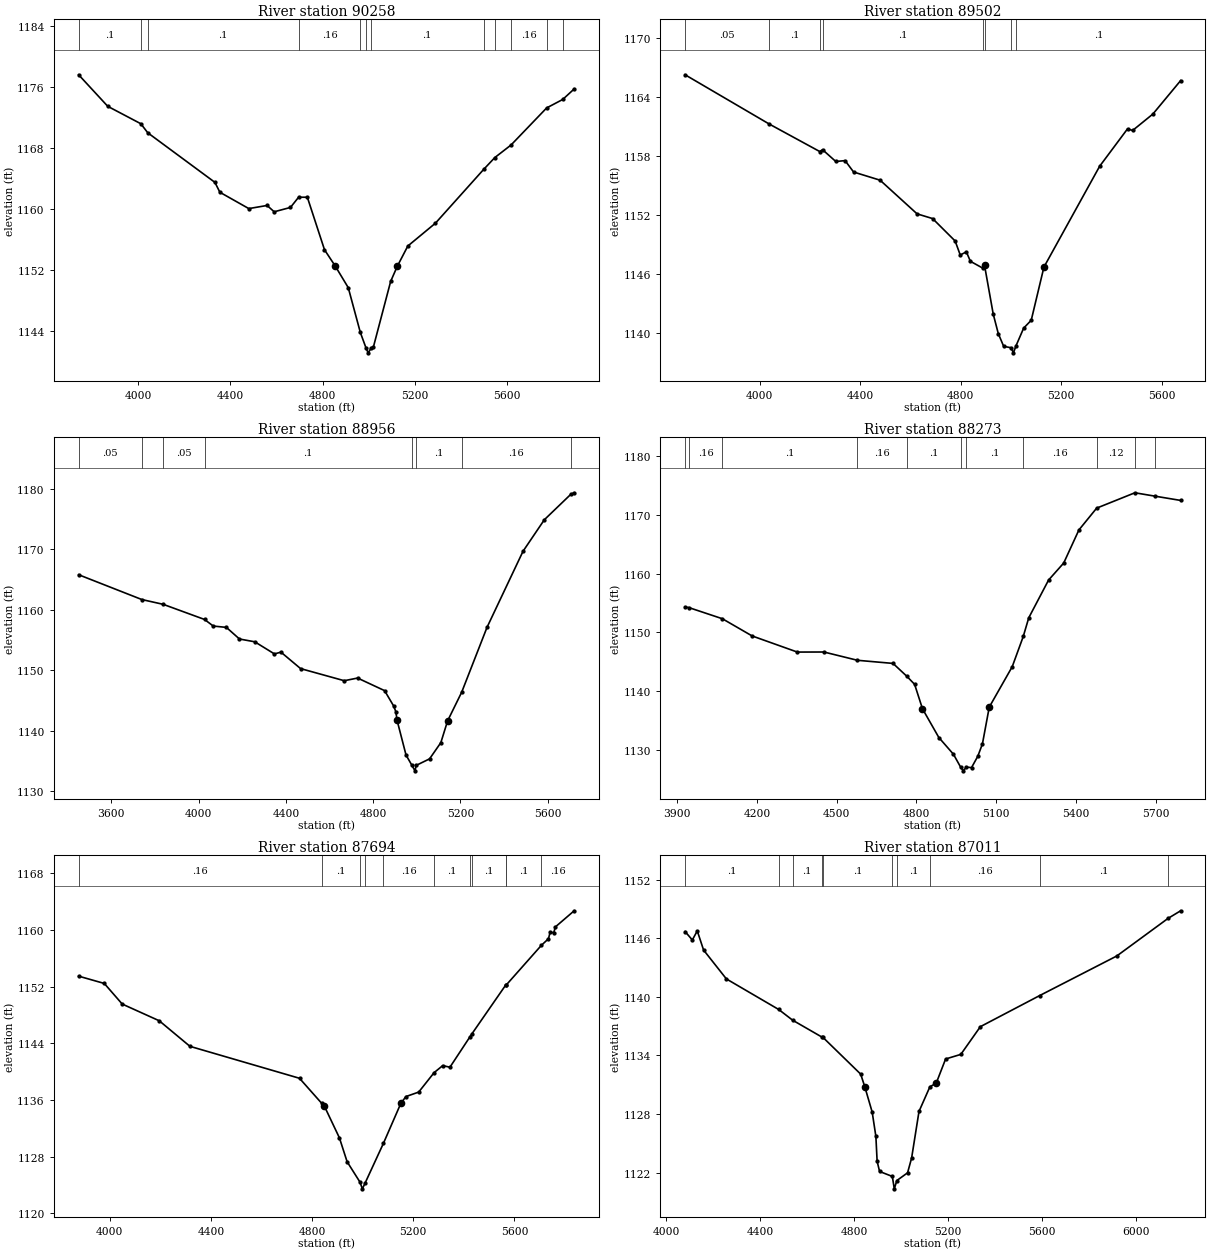
Type RM Length L Ch R = 1 ,90258   ,756,756,756
BEGIN DESCRIPTION:
CYPRESS CREEK 140.0
END DESCRIPTION:
XS GIS Cut Line= 4
      2930200.48      10121242.1      2929992.14     10120288.95
      2929757.77     10119778.54      2929320.27     10119351.46
#Sta/Elev= 30
  3741.7 1177.56  3868.1 1173.42  4011.3 1171.14  4041.5 1169.95  4332.6 1163.45
  4354.2 1162.15  4479.6 1160.01  4558.9 1160.42  4589.6 1159.59  4660.2 1160.16
  4695.5  1161.5  4733.4  1161.5  4807.8 1154.61  4853.8  1152.5  4910.8 1149.64
  4963.2 1143.76  4987.2 1141.78    4997 1141.09  5009.2 1141.66  5020.2  1141.9
  5094.7 1150.46  5123.2 1152.43  5169.1  1155.1    5289  1158.1    5498 1165.15
  5546.3  1166.7  5616.7 1168.35    5771 1173.21  5840.6 1174.32  5890.4  1175.7
#Mann= 12 ,-1 , 0
  3741.7      .1       0  4011.3     .05       0  4041.5      .1       0
  4695.5     .16       0  4963.2      .1       0  4987.2     .07       0
  5009.2      .1       0    5498     .16       0  5546.3      .1       0
  5616.7     .16       0    5771      .1       0  5840.6     .16       0
Bank Sta=4853.8,5123.2
XS Rating Curve= 0 ,0
Exp/Cntr=0.3,0.1

Type RM Length L Ch R = 1 ,89502   ,546,546,546
BEGIN DESCRIPTION:
CYPRESS CREEK 138.0
END DESCRIPTION:
XS GIS Cut Line= 3
      2930726.51     10120997.25      2930554.64     10119830.62
      2930450.48     10119044.21
#Sta/Elev= 30
  3703.5 1166.28  4038.1 1161.28  4239.6 1158.48  4250.6 1158.67  4303.4 1157.47
  4340.4 1157.56  4374.2  1156.4  4479.7 1155.57  4626.9 1152.15  4688.8 1151.67
  4778.5 1149.39  4798.7 1147.97  4823.1 1148.29  4839.1 1147.33  4888.1 1146.64
  4895.3 1146.93    4930 1141.97  4950.2 1139.98  4971.6 1138.69  5000.6 1138.55
  5010.5 1138.03  5020.8 1138.75  5051.1 1140.54  5081.3 1141.34  5131.8 1146.74
  5353.7 1156.99  5464.7 1160.79  5484.8 1160.62  5565.5 1162.29    5676 1165.69
#Mann= 8 ,-1 , 0
  3703.5     .05       0  4038.1      .1       0  4239.6     .16       0
  4250.6      .1       0  4888.1     .16       0  4895.3      .1       0
  5000.6     .07       0  5020.8      .1       0
Bank Sta=4895.3,5131.8
XS Rating Curve= 0 ,0
Exp/Cntr=0.3,0.1

Type RM Length L Ch R = 1 ,88956   ,683,683,683
BEGIN DESCRIPTION:
CYPRESS CREEK 137.0
END DESCRIPTION:
XS GIS Cut Line= 3
      2931085.89     10121080.58      2931106.73     10119841.04
      2930856.72     10118841.03
#Sta/Elev= 30
  3450.7 1165.79  3740.4 1161.69  3838.1  1160.9  4027.6  1158.4  4067.6 1157.31
  4127.6 1157.09  4187.7 1155.17  4257.7 1154.71  4347.7 1152.71  4377.7    1153
  4467.7 1150.28  4667.7 1148.28  4728.9 1148.72  4852.6 1146.64  4893.8 1144.12
  4904.1 1143.17  4909.6 1141.76  4950.9 1135.99  4976.3 1134.39  4991.8 1133.39
  4997.3 1134.29  5058.7 1135.37  5110.3 1138.05  5141.2 1141.64  5205.8 1146.38
  5321.9  1157.1  5486.9 1169.67  5584.4 1174.87  5706.2 1179.09  5721.2 1179.33
#Mann= 8 ,-1 , 0
  3450.7     .05       0  3740.4      .1       0  3838.1     .05       0
  4027.6      .1       0  4976.3     .07       0  4997.3      .1       0
  5205.8     .16       0  5706.2      .1       0
Bank Sta=4909.6,5141.2
XS Rating Curve= 0 ,0
Exp/Cntr=0.3,0.1

Type RM Length L Ch R = 1 ,88273   ,579,579,579
BEGIN DESCRIPTION:
CYPRESS CREEK 136.0
END DESCRIPTION:
XS GIS Cut Line= 4
      2931640.58     10120335.87       2931656.2     10119476.45
      2931546.83     10118992.08      2931214.41     10118607.72
#Sta/Elev= 30
  3929.9 1154.33  3944.4 1154.23    4070 1152.34  4182.1 1149.41  4352.1 1146.67
  4452.1 1146.68  4578.4 1145.27  4712.2 1144.74  4763.9 1142.56  4793.4 1141.18
    4823 1137.02  4884.5 1132.14  4939.5 1129.29  4966.5  1127.1  4976.5 1126.47
  4987.8  1127.1  5007.5 1127.02    5031 1128.94  5048.5 1131.05  5074.2 1137.31
  5160.6 1144.18  5202.1 1149.32  5222.8  1152.5  5297.4 1158.92  5354.4 1161.82
  5411.5 1167.44  5478.3 1171.15  5622.1 1173.76  5696.9 1173.19  5794.2 1172.46
#Mann= 11 ,-1 , 0
  3929.9      .1       0  3944.4     .16       0    4070      .1       0
  4578.4     .16       0  4763.9      .1       0  4966.5     .07       0
  4987.8      .1       0  5202.1     .16       0  5478.3     .12       0
  5622.1     .16       0  5696.9      .1       0
Bank Sta=4823,5074.2
XS Rating Curve= 0 ,0
Exp/Cntr=0.3,0.1

Type RM Length L Ch R = 1 ,87694   ,683,683,683
BEGIN DESCRIPTION:
CYPRESS CREEK 135.0
END DESCRIPTION:
XS GIS Cut Line= 4
      2931994.75     10120278.54       2932218.7     10119544.16
      2932130.16      10118945.2      2931739.97     10118508.18
#Sta/Elev= 30
  3877.3 1153.49  3978.7 1152.46  4049.6 1149.55    4196 1147.19  4317.4 1143.58
  4750.5 1139.07  4837.6 1135.56  4847.7 1135.22  4908.3 1130.66  4938.7 1127.29
  4989.2 1124.43  4999.1 1123.46  5009.4 1124.24  5082.1 1129.87  5150.9 1135.51
  5171.2 1136.49  5221.7 1137.12  5282.7 1139.87  5316.7 1140.86  5345.2 1140.63
  5424.1 1144.91  5430.9 1145.28  5565.5 1152.22  5567.8 1152.24    5707 1157.85
  5734.7 1158.77  5741.4 1159.69  5755.6 1159.63  5762.4 1160.45  5836.4 1162.72
#Mann= 11 ,-1 , 0
  3877.3     .16       0  4837.6      .1       0  4989.2     .07       0
  5009.4      .1       0  5082.1     .16       0  5282.7      .1       0
  5424.1     .16       0  5430.9      .1       0  5565.5     .16       0
  5567.8      .1       0    5707     .16       0
Bank Sta=4847.7,5150.9
XS Rating Curve= 0 ,0
Exp/Cntr=0.3,0.1

Type RM Length L Ch R = 1 ,87011   ,590,590,590
BEGIN DESCRIPTION:
CYPRESS CREEK 134.0
END DESCRIPTION:
XS GIS Cut Line= 3
      2933057.25     10119893.13      2932703.08     10118768.12
      2932015.56      10118143.1
#Sta/Elev= 30
  4081.1 1146.69  4111.9 1145.83  4132.9 1146.76  4159.7  1144.8  4256.8 1141.84
  4479.4 1138.71  4538.9 1137.61  4662.9 1135.89  4666.1 1135.89  4828.2 1132.09
  4845.8 1130.79  4877.2  1128.2  4892.9 1125.71  4898.2 1123.16  4908.7 1122.12
  4962.9 1121.61  4971.3 1120.34  4982.1 1121.19  5027.7 1121.98    5045  1123.5
  5076.4 1128.27  5122.7 1130.79  5149.8 1131.17  5189.6 1133.64  5254.3 1134.11
  5337.5 1136.95  5589.5 1140.13    5918 1144.19  6136.1 1148.04  6189.7 1148.82
#Mann= 10 ,-1 , 0
  4081.1      .1       0  4479.4     .16       0  4538.9      .1       0
  4662.9     .16       0  4666.1      .1       0  4962.9     .07       0
  4982.1      .1       0  5122.7     .16       0  5589.5      .1       0
  6136.1     .16       0
Bank Sta=4845.8,5149.8
XS Rating Curve= 0 ,0
Exp/Cntr=0.3,0.1

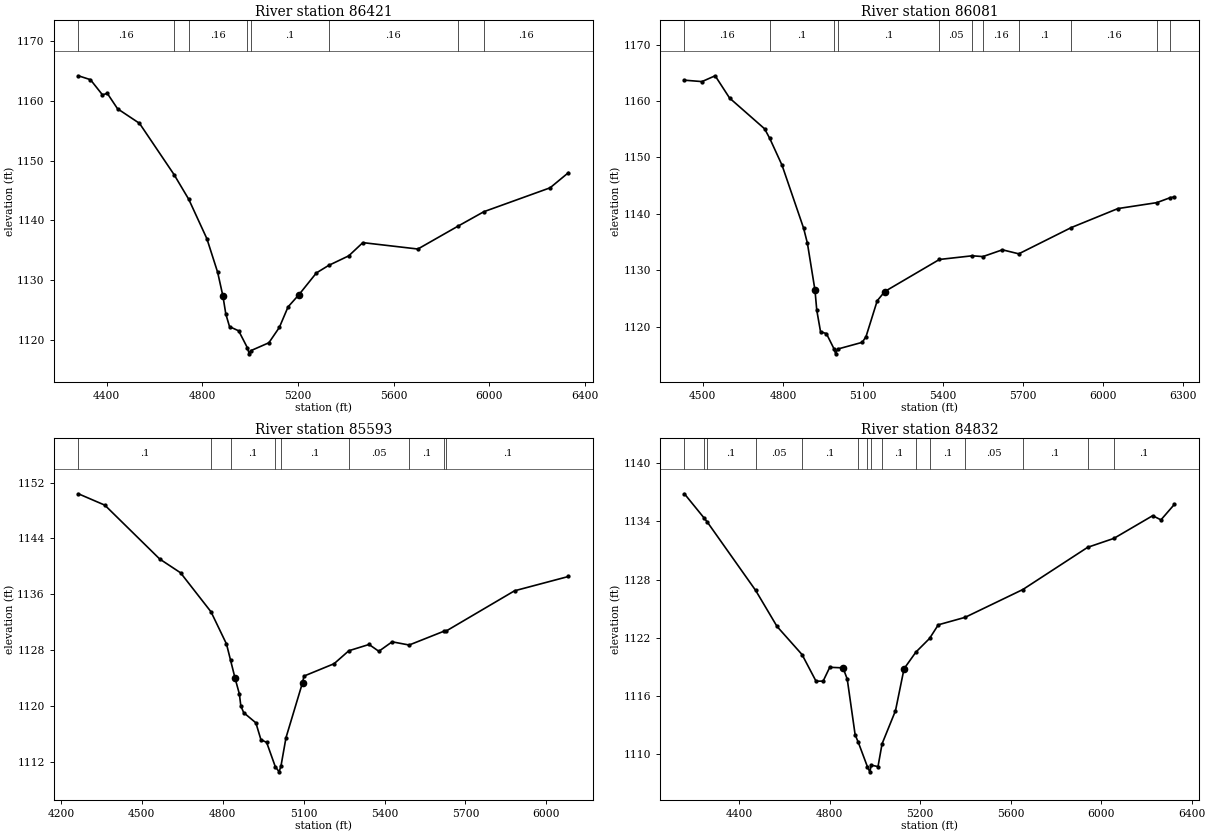
Type RM Length L Ch R = 1 ,86421   ,340,340,340
BEGIN DESCRIPTION:
CYPRESS CREEK 133.0
END DESCRIPTION:
XS GIS Cut Line= 4
      2933703.11     10119330.65      2933390.58     10119044.16
      2933124.95     10118544.16      2932249.97     10117945.22
#Sta/Elev= 30
  4281.1  1164.2  4331.6 1163.55  4381.6 1161.03  4402.5 1161.24  4445.1 1158.68
  4536.9 1156.24  4681.4 1147.67  4743.1 1143.52  4818.8 1136.94  4863.9 1131.31
  4885.9 1127.34  4898.1 1124.32  4913.6 1122.22  4951.9 1121.52  4988.7 1118.65
  4995.6 1117.67  5001.5 1118.18  5078.1 1119.52    5122 1122.09  5158.5 1125.53
  5203.8 1127.56    5277 1131.21    5328 1132.46  5412.4 1134.07  5471.3 1136.28
  5701.5 1135.21  5867.8    1139  5977.9 1141.46  6254.6 1145.45  6331.6 1147.99
#Mann= 8 ,-1 , 0
  4281.1     .16       0  4681.4      .1       0  4743.1     .16       0
  4988.7     .07       0  5001.5      .1       0    5328     .16       0
  5867.8      .1       0  5977.9     .16       0
Bank Sta=4885.9,5203.8
XS Rating Curve= 0 ,0
Exp/Cntr=0.3,0.1

Type RM Length L Ch R = 1 ,86081   ,488,488,488
BEGIN DESCRIPTION:
CYPRESS CREEK 132.0
END DESCRIPTION:
XS GIS Cut Line= 4
      2933786.41     10119033.74       2933593.7     10118679.58
      2933229.12     10118278.54      2932542.54     10117711.59
#Sta/Elev= 30
  4430.8 1163.68  4496.6 1163.43    4546 1164.46  4600.1 1160.51  4731.2 1155.06
  4750.4 1153.37  4796.7 1148.58  4877.3 1137.44  4891.5 1134.78  4919.9 1126.45
  4926.6  1122.9  4940.8 1119.07  4962.5 1118.77  4990.6 1116.11  4997.3 1115.17
  5004.4 1116.01  5096.9 1117.21  5111.1 1118.23    5153 1124.58  5181.4 1126.22
    5386  1131.9  5508.8 1132.55  5548.7 1132.41  5621.9 1133.61  5683.2  1132.9
  5879.7 1137.55  6054.4 1140.92  6199.9 1141.97  6250.7 1142.86  6266.4 1142.99
#Mann= 11 ,-1 , 0
  4430.8     .16       0  4750.4      .1       0  4990.6     .07       0
  5004.4      .1       0    5386     .05       0  5508.8      .1       0
  5548.7     .16       0  5683.2      .1       0  5879.7     .16       0
  6199.9      .1       0  6250.7     .16       0
Bank Sta=4919.9,5181.4
XS Rating Curve= 0 ,0
Exp/Cntr=0.3,0.1

Type RM Length L Ch R = 1 ,85593   ,761,761,761
BEGIN DESCRIPTION:
CYPRESS CREEK 131.0
END DESCRIPTION:
XS GIS Cut Line= 3
      2934364.57     10118382.72      2933447.87     10118049.37
      2932895.77     10117413.94
#Sta/Elev= 30
  4264.6 1150.39  4362.8 1148.76  4566.3 1141.04  4643.5 1139.07  4756.4 1133.48
  4813.8 1128.87  4829.1 1126.52  4845.7 1123.95  4861.6 1121.71    4867    1120
  4877.6 1119.03  4922.8 1117.57  4941.5 1115.16  4962.7 1114.77  4994.7  1111.3
    5009 1110.55  5015.9 1111.39  5034.5 1115.45  5095.7 1123.32  5101.1 1124.27
  5212.7 1126.04  5267.5  1127.9  5342.5  1128.8  5378.7 1127.82    5428 1129.18
  5491.1 1128.72  5620.2  1130.7  5628.6 1130.73  5881.9 1136.49  6081.8 1138.54
#Mann= 9 ,-1 , 0
  4264.6      .1       0  4756.4     .16       0  4829.1      .1       0
  4994.7     .07       0  5015.9      .1       0  5267.5     .05       0
  5491.1      .1       0  5620.2     .16       0  5628.6      .1       0
Bank Sta=4845.7,5095.7
XS Rating Curve= 0 ,0
Exp/Cntr=0.3,0.1

Type RM Length L Ch R = 1 ,84832   ,912,912,912
BEGIN DESCRIPTION:
CYPRESS CREEK 129.0
END DESCRIPTION:
XS GIS Cut Line= 4
      2934572.87     10118012.91      2934223.91     10117554.58
      2933666.62     10117325.41      2932730.63     10117008.22
#Sta/Elev= 30
    4157 1136.84  4245.6  1134.3  4256.6 1133.98  4472.2 1126.87  4566.6 1123.16
  4677.2 1120.26  4738.9 1117.52  4770.3 1117.52  4799.7 1118.95  4858.4 1118.89
    4877 1117.73  4911.9 1111.99  4926.1  1111.2    4966 1108.71  4976.6 1108.17
  4983.7 1108.86    5013 1108.71    5031 1111.06  5090.3 1114.47  5128.2  1118.8
  5180.7 1120.52  5240.8 1121.92  5279.6 1123.33  5398.1  1124.1  5653.6 1126.97
    5940 1131.32  6055.9 1132.24  6227.4 1134.58    6264 1134.15  6323.9 1135.76
#Mann= 15 ,-1 , 0
    4157     .05       0  4245.6     .16       0  4256.6      .1       0
  4472.2     .05       0  4677.2      .1       0  4926.1     .16       0
    4966     .07       0  4983.7     .16       0    5031      .1       0
  5180.7     .05       0  5240.8      .1       0  5398.1     .05       0
  5653.6      .1       0    5940     .05       0  6055.9      .1       0
Bank Sta=4858.4,5128.2
XS Rating Curve= 0 ,0
Exp/Cntr=0.3,0.1