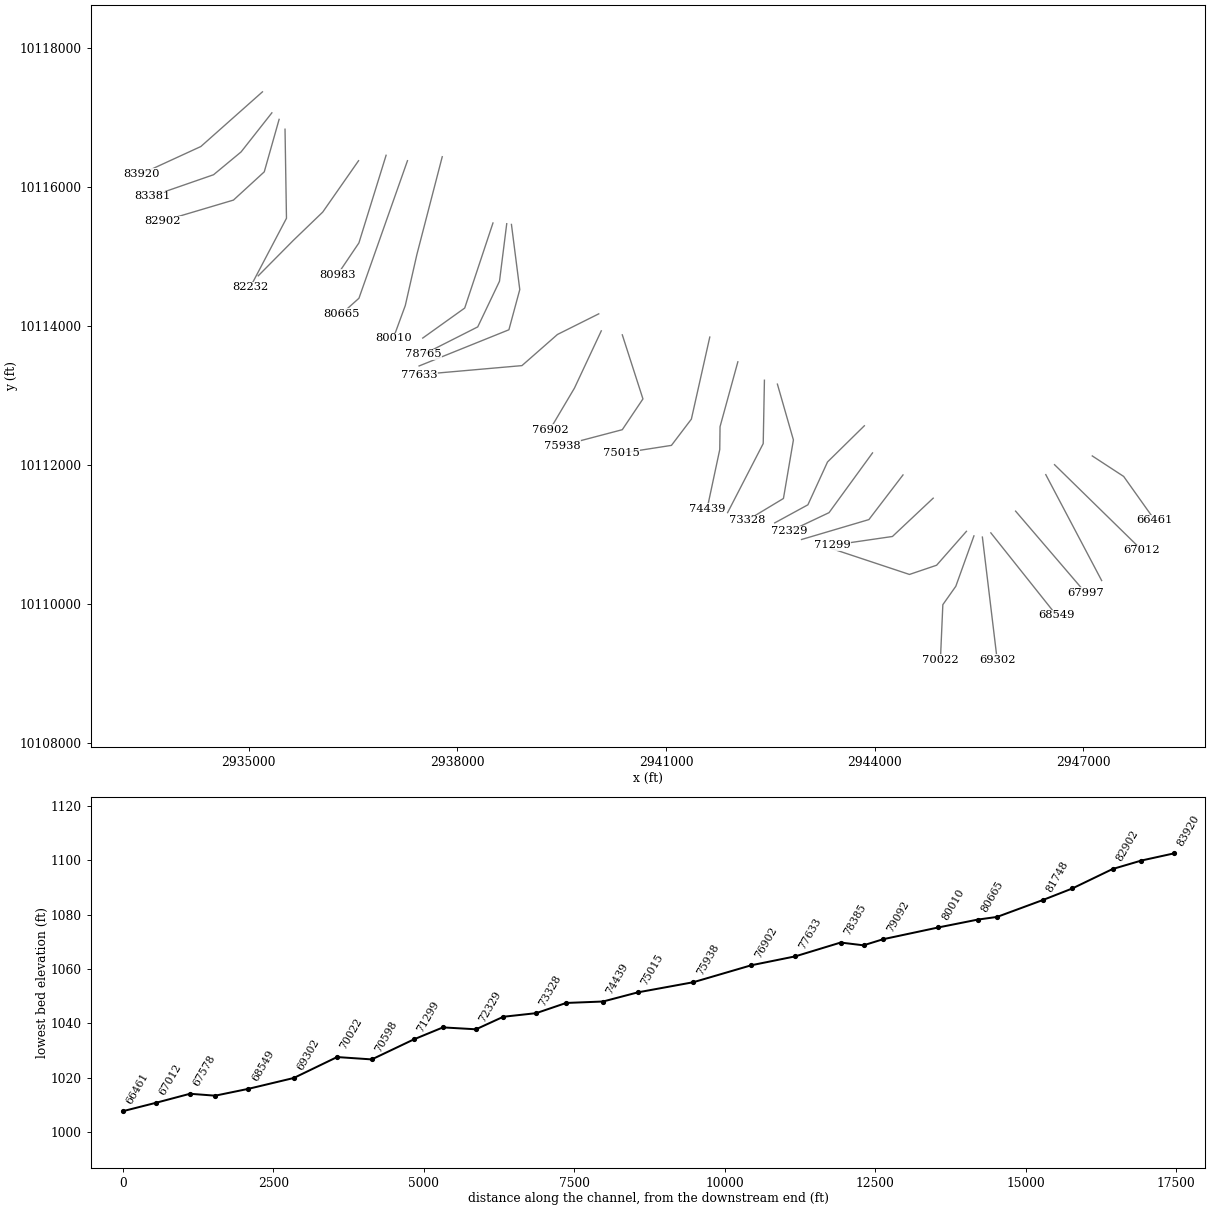
HEC-RAS study CYPRESS CREEK.prj: CYPRESS CREEK Base Level Engineering

--- CYPRESS CREEK.g01 (geometry) --- (continued)

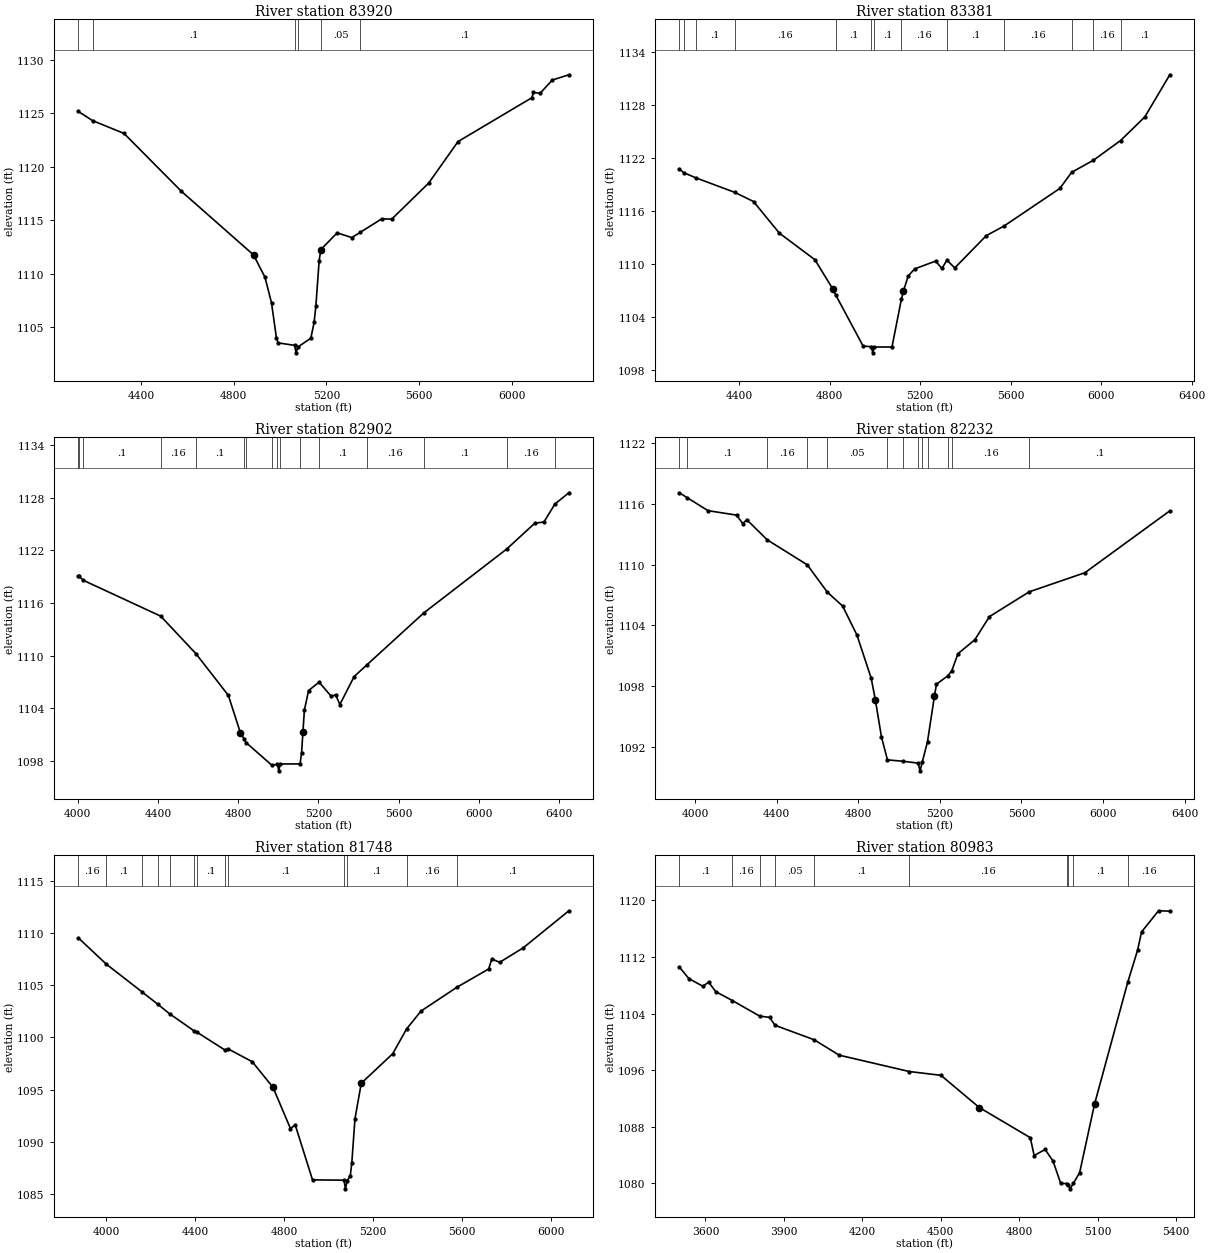
Type RM Length L Ch R = 1 ,83920   ,539,539,539
BEGIN DESCRIPTION:
CYPRESS CREEK 128.0
END DESCRIPTION:
XS GIS Cut Line= 3
      2935197.86     10117372.28      2934312.45     10116585.83
      2933463.47     10116195.19
#Sta/Elev= 30
  4128.5 1125.16  4189.5 1124.31  4325.6 1123.11  4573.1 1117.71  4885.1 1111.76
  4934.4 1109.68  4962.8 1107.28  4983.8 1104.03  4991.3 1103.54  5062.4 1103.31
  5068.8 1102.61  5076.6 1103.15  5132.6 1103.98  5146.8 1105.45  5154.4 1106.99
  5168.6 1111.23  5175.3 1112.18    5178 1112.31  5246.3 1113.82  5309.9 1113.38
  5346.8 1113.88  5438.2 1115.12  5482.3 1115.11  5641.3 1118.46  5768.5 1122.35
  6087.7 1126.45  6094.2 1126.95  6122.7 1126.85  6175.8  1128.1  6247.3 1128.59
#Mann= 6 ,-1 , 0
  4128.5     .05       0  4189.5      .1       0  5062.4     .07       0
  5076.6      .1       0    5178     .05       0  5346.8      .1       0
Bank Sta=4885.1,5175.3
XS Rating Curve= 0 ,0
Exp/Cntr=0.3,0.1

Type RM Length L Ch R = 1 ,83381   ,479,479,479
BEGIN DESCRIPTION:
CYPRESS CREEK 127.0
END DESCRIPTION:
XS GIS Cut Line= 4
      2935333.28     10117070.19      2934890.58      10116507.7
      2934494.75     10116179.58      2933609.31     10115872.28
#Sta/Elev= 30
  4135.9 1120.79    4156 1120.37    4208  1119.8  4381.6 1118.14  4463.8 1117.11
  4577.7 1113.54  4734.9 1110.53  4813.5 1107.24    4828 1106.49    4948 1100.76
  4984.3 1100.68  4990.7 1099.99  4997.5 1100.65  5075.6 1100.65  5117.1 1106.04
  5126.4    1107  5147.3 1108.69  5175.9 1109.49  5268.4 1110.37  5296.1 1109.54
  5318.5 1110.47    5353  1109.6  5492.3 1113.25  5570.9 1114.34  5817.1 1118.59
  5869.7 1120.42  5965.6 1121.78  6085.6 1124.01  6192.4 1126.67  6303.1 1131.45
#Mann= 13 ,-1 , 0
  4135.9      .1       0    4156     .16       0    4208      .1       0
  4381.6     .16       0    4828      .1       0  4984.3    .033       0
  4997.5      .1       0  5117.1     .16       0  5318.5      .1       0
  5570.9     .16       0  5869.7      .1       0  5965.6     .16       0
  6085.6      .1       0
Bank Sta=4813.5,5126.4
XS Rating Curve= 0 ,0
Exp/Cntr=0.3,0.1

Type RM Length L Ch R = 1 ,82902   ,670,670,670
BEGIN DESCRIPTION:
CYPRESS CREEK 126.0
END DESCRIPTION:
XS GIS Cut Line= 4
      2935437.44     10116976.41      2935223.91     10116221.25
       2934781.2       10115815.      2933765.61     10115512.92
#Sta/Elev= 30
  4003.8 1119.04  4006.9 1119.04    4028 1118.58  4414.2 1114.49  4589.5 1110.22
  4751.5 1105.46  4811.7 1101.18  4830.7 1100.47  4839.8 1100.08  4968.7 1097.49
  4996.1 1097.63  5002.6 1096.86  5010.2 1097.64    5109 1097.65  5116.3 1098.87
  5123.1 1101.24  5130.5 1103.78  5151.4 1106.01  5203.8 1106.97  5264.9 1105.34
  5285.9 1105.54  5307.4 1104.42  5378.4  1107.6  5440.7 1108.91  5724.8 1114.84
  6138.6 1122.13  6279.1 1125.08  6324.7 1125.22  6379.4 1127.27    6449 1128.55
#Mann= 16 ,-1 , 0
  4003.8      .1       0  4006.9     .16       0    4028      .1       0
  4414.2     .16       0  4589.5      .1       0  4830.7     .05       0
  4839.8      .1       0  4968.7     .05       0  4996.1    .033       0
  5010.2     .05       0    5109     .16       0  5203.8      .1       0
  5440.7     .16       0  5724.8      .1       0  6138.6     .16       0
  6379.4      .1       0
Bank Sta=4811.7,5123.1
XS Rating Curve= 0 ,0
Exp/Cntr=0.3,0.1

Type RM Length L Ch R = 1 ,82232   ,484,484,484
BEGIN DESCRIPTION:
CYPRESS CREEK 125.0
END DESCRIPTION:
XS GIS Cut Line= 3
      2935522.41     10116834.56      2935543.25     10115553.28
      2935020.51     10114558.86
#Sta/Elev= 30
  3922.5 1117.06  3962.6 1116.56  4063.4  1115.3  4203.4 1114.86  4233.4 1114.03
  4253.4 1114.41  4353.4 1112.43  4549.9 1109.97  4648.2 1107.28  4723.4 1105.91
  4793.4 1103.06  4863.5  1098.8  4883.5 1096.71  4913.5 1093.05    4943 1090.77
  5020.4 1090.63  5093.5 1090.45  5103.2 1089.69  5113.5 1090.52  5139.5 1092.57
  5173.5 1097.06  5183.5 1098.22  5239.7 1099.05  5258.4 1099.54  5288.8 1101.22
  5371.3 1102.59  5443.1 1104.87    5638 1107.31  5911.1 1109.19  6327.4 1115.28
#Mann= 13 ,-1 , 0
  3922.5     .16       0  3962.6      .1       0  4353.4     .16       0
  4549.9      .1       0  4648.2     .05       0    4943      .1       0
  5020.4     .05       0  5093.5     .07       0  5113.5     .05       0
  5139.5     .16       0  5239.7      .1       0  5258.4     .16       0
    5638      .1       0
Bank Sta=4883.5,5173.5
XS Rating Curve= 0 ,0
Exp/Cntr=0.3,0.1

Type RM Length L Ch R = 1 ,81748   ,765,765,765
BEGIN DESCRIPTION:
CYPRESS CREEK 124.0
END DESCRIPTION:
XS GIS Cut Line= 4
      2936579.71      10116381.4      2936064.08     10115641.82
      2935642.21     10115235.57      2935137.01     10114725.17
#Sta/Elev= 30
  3875.8 1109.53  4001.1 1107.02  4162.3 1104.35  4234.2 1103.15  4285.8 1102.26
  4396.8 1100.61  4409.4 1100.49  4532.9 1098.81  4550.4 1098.88  4657.7 1097.66
  4750.7 1095.21  4829.4 1091.26  4850.8 1091.61  4928.5 1086.34    5070 1086.31
  5076.7 1085.48  5084.1 1086.25  5098.3 1086.73  5105.2 1087.98  5119.4 1092.19
  5147.7  1095.6  5289.2 1098.43  5351.3  1100.8  5416.5 1102.52    5580 1104.83
  5720.5 1106.55  5734.7 1107.51  5770.1 1107.19  5876.1 1108.58  6081.2 1112.13
#Mann= 13 ,-1 , 0
  3875.8     .16       0  4001.1      .1       0  4162.3     .05       0
  4234.2      .1       0  4285.8     .05       0  4396.8     .16       0
  4409.4      .1       0  4532.9     .16       0  4550.4      .1       0
    5070     .07       0  5084.1      .1       0  5351.3     .16       0
    5580      .1       0
Bank Sta=4750.7,5147.7
XS Rating Curve= 0 ,0
Exp/Cntr=0.3,0.1

Type RM Length L Ch R = 1 ,80983   ,318,318,318
BEGIN DESCRIPTION:
CYPRESS CREEK 123.0
END DESCRIPTION:
XS GIS Cut Line= 3
      2936975.55     10116459.56      2936584.92     10115199.11
        2936274.     10114737.92
#Sta/Elev= 30
  3500.2  1110.6  3536.7 1108.95  3590.1 1107.87  3612.4 1108.44  3639.8  1107.1
    3703 1105.85  3807.3 1103.65  3845.8 1103.46  3866.1 1102.35  4015.9  1100.3
  4111.8 1098.12  4379.8 1095.81  4500.9 1095.27  4647.4 1090.72  4842.3 1086.46
  4857.3 1083.93  4899.3 1084.79  4929.3 1083.16  4958.9 1079.98  4983.1 1079.97
  4986.2 1079.81  4994.9 1079.22  5007.2 1079.99  5031.2 1081.51  5088.1 1091.19
  5215.1 1108.42  5253.1 1113.01    5268 1115.55  5332.8 1118.54    5376 1118.49
#Mann= 10 ,-1 , 0
  3500.2      .1       0    3703     .16       0  3807.3      .1       0
  3866.1     .05       0  4015.9      .1       0  4379.8     .16       0
  4983.1      .1       0  4986.2     .07       0  5007.2      .1       0
  5215.1     .16       0
Bank Sta=4647.4,5088.1
XS Rating Curve= 0 ,0
Exp/Cntr=0.3,0.1

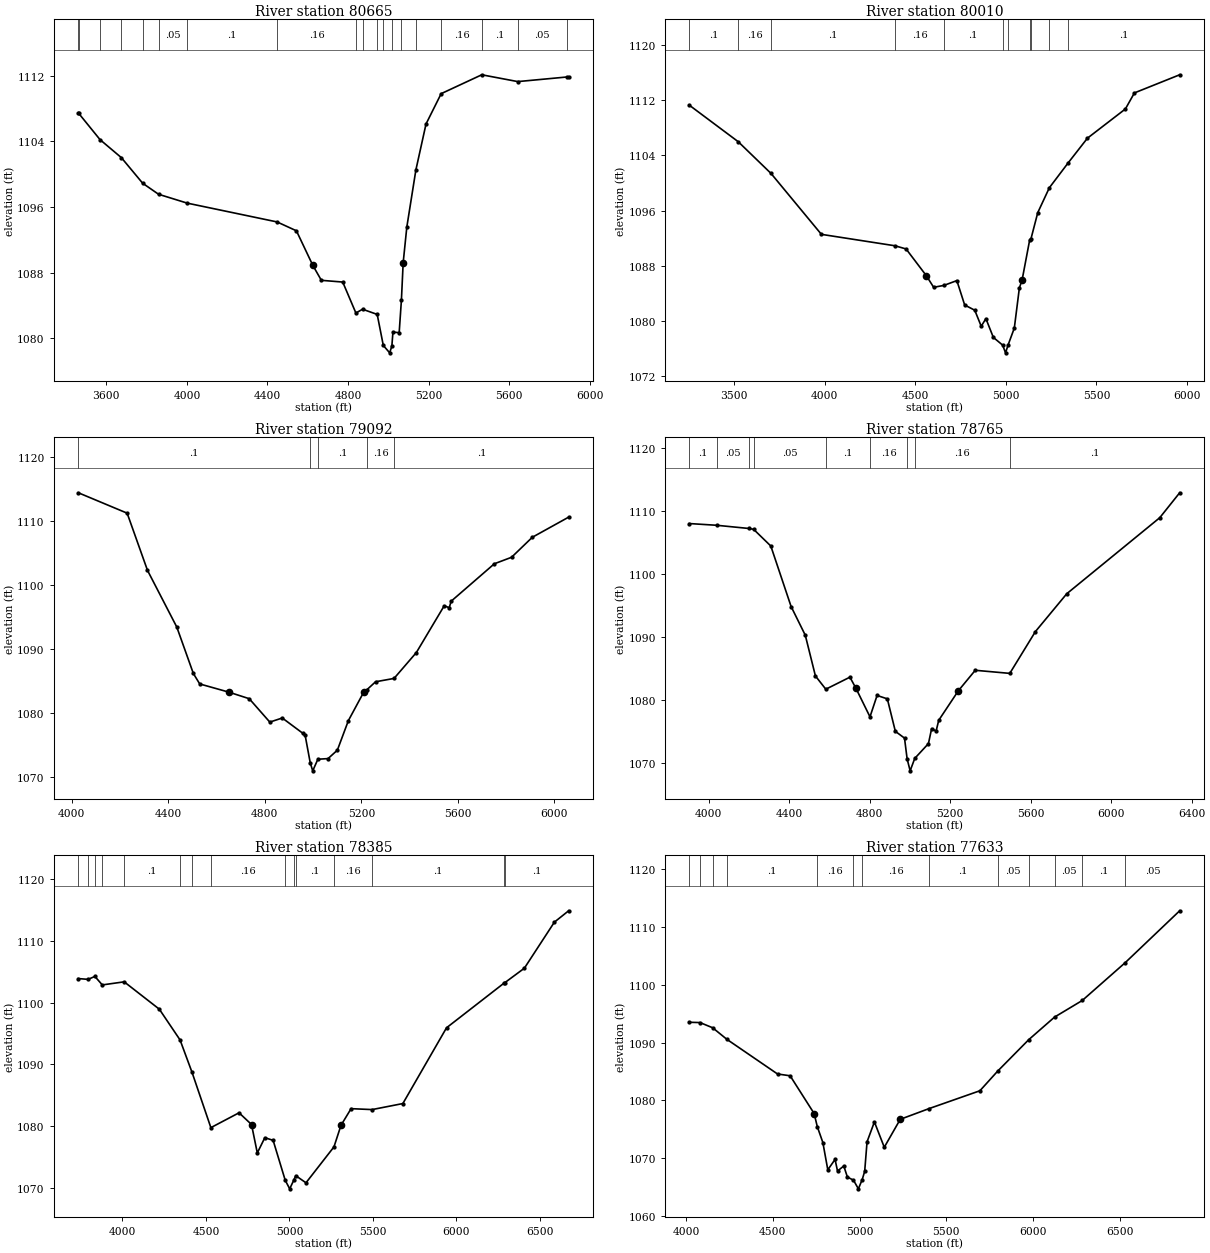
Type RM Length L Ch R = 1 ,80665   ,655,655,655
BEGIN DESCRIPTION:
CYPRESS CREEK 122.0
END DESCRIPTION:
XS GIS Cut Line= 3
      2937282.84     10116381.41      2936584.92     10114402.24
      2936335.19     10114178.52
#Sta/Elev= 30
  3461.3 1107.48  3463.1 1107.41  3568.9 1104.21  3674.7 1102.02  3780.6  1098.9
  3859.4 1097.56  4001.7 1096.48  4447.9 1094.19  4543.8 1093.11  4625.2  1088.9
  4667.6 1087.08  4773.7 1086.87    4839  1083.1  4872.1 1083.56  4944.8 1082.93
  4975.1 1079.15  5006.7 1078.25  5017.6 1079.08  5022.9 1080.77  5053.9 1080.71
    5065 1084.67 5073.73 1089.22  5091.8 1093.56  5136.9 1100.53  5187.2 1106.12
  5262.3 1109.81  5463.9 1112.11  5642.7 1111.28  5886.3 1111.84  5895.2 1111.86
#Mann= 19 ,-1 , 0
  3461.3      .1       0  3463.1     .16       0  3568.9      .1       0
  3674.7     .05       0  3780.6      .1       0  3859.4     .05       0
  4001.7      .1       0  4447.9     .16       0    4839      .1       0
  4872.1     .16       0  4944.8      .1       0  4975.1     .07       0
  5017.6      .1       0    5065     .16       0  5136.9      .1       0
  5262.3     .16       0  5463.9      .1       0  5642.7     .05       0
  5886.3      .1       0
Bank Sta=4625.2,5073.73
XS Rating Curve= 0 ,0
Exp/Cntr=0.3,0.1

Type RM Length L Ch R = 1 ,80010   ,918,918,918
BEGIN DESCRIPTION:
CYPRESS CREEK 121.0
END DESCRIPTION:
XS GIS Cut Line= 4
      2937782.83     10116438.69      2937418.25     10115032.44
      2937251.58     10114298.07      2937079.69     10113829.28
#Sta/Elev= 30
  3253.9 1111.28  3523.3 1105.99  3704.1 1101.39  3982.2 1092.55  4388.6 1090.89
  4449.5 1090.43  4560.7 1086.57  4601.5 1084.87  4657.7 1085.14  4729.6 1085.84
  4772.7  1082.3  4828.4 1081.54    4864 1079.22  4889.9 1080.32  4930.9  1077.6
  4982.2 1076.48  4998.2 1075.36  5012.9 1076.54  5046.7 1078.96  5074.5 1084.77
  5089.8 1085.96  5131.4 1091.74  5138.1 1091.86    5176  1095.7  5239.9 1099.31
  5341.7 1102.85    5450  1106.5  5659.5 1110.74  5709.3 1113.07    5959  1115.7
#Mann= 11 ,-1 , 0
  3253.9      .1       0  3523.3     .16       0  3704.1      .1       0
  4388.6     .16       0  4657.7      .1       0  4982.2     .07       0
  5012.9      .1       0  5131.4     .16       0  5138.1      .1       0
  5239.9     .16       0  5341.7      .1       0
Bank Sta=4560.7,5089.8
XS Rating Curve= 0 ,0
Exp/Cntr=0.3,0.1

Type RM Length L Ch R = 1 ,79092   ,327,327,327
BEGIN DESCRIPTION:
CYPRESS CREEK 120.0
END DESCRIPTION:
XS GIS Cut Line= 3
      2938511.99     10115485.55      2938105.75     10114261.61
      2937502.55     10113830.01
#Sta/Elev= 30
  4027.6 1114.38  4229.7  1111.2    4314 1102.28  4435.4 1093.44    4504  1086.2
  4530.4 1084.57  4651.2 1083.29  4735.5 1082.27  4820.8 1078.62  4872.4 1079.26
  4956.7  1076.9  4967.3 1076.54  4988.3 1072.26  4998.6 1071.02  5019.9 1072.83
  5062.1 1072.93  5100.6 1074.24  5146.4 1078.86  5209.6 1083.27  5222.8 1083.66
    5259 1084.91  5335.5 1085.43    5428 1089.47  5543.4 1096.76  5564.3 1096.46
  5572.1 1097.47  5751.1 1103.31  5822.3 1104.32  5908.3 1107.44  6058.9 1110.58
#Mann= 5 ,-1 , 0
  4027.6      .1       0  4988.3     .07       0  5019.9      .1       0
  5222.8     .16       0  5335.5      .1       0
Bank Sta=4651.2,5209.6
XS Rating Curve= 0 ,0
Exp/Cntr=0.3,0.1

Type RM Length L Ch R = 1 ,78765   ,380,380,380
BEGIN DESCRIPTION:
CYPRESS CREEK 119.0
END DESCRIPTION:
XS GIS Cut Line= 4
      2938709.92     10115475.15      2938605.75     10114647.03
      2938293.25     10113990.78      2937512.72     10113595.31
#Sta/Elev= 30
  3903.8 1107.97  4038.5  1107.7    4200 1107.19  4222.8 1107.06  4308.4 1104.41
  4409.2 1094.82  4479.7 1090.27  4530.1 1083.81  4581.7 1081.71  4701.5 1083.62
  4731.7 1081.84  4801.2 1077.33  4836.5 1080.72  4887.5 1080.18  4927.3 1075.03
  4972.8 1073.96  4985.8 1070.67  5000.8 1068.77  5023.7 1070.74  5091.8 1073.09
  5107.6 1075.47  5129.8 1075.06  5142.8 1076.78  5240.5 1081.47  5324.4 1084.71
    5496 1084.22  5623.4 1090.85  5779.3 1096.85  6241.4  1108.9  6340.3 1112.85
#Mann= 9 ,-1 , 0
  3903.8      .1       0  4038.5     .05       0    4200      .1       0
  4222.8     .05       0  4581.7      .1       0  4801.2     .16       0
  4985.8     .07       0  5023.7     .16       0    5496      .1       0
Bank Sta=4731.7,5240.5
XS Rating Curve= 0 ,0
Exp/Cntr=0.3,0.1

Type RM Length L Ch R = 1 ,78385   ,752,752,752
BEGIN DESCRIPTION:
CYPRESS CREEK 118.0
END DESCRIPTION:
XS GIS Cut Line= 4
      2938777.62     10115464.76      2938897.42     10114527.24
      2938741.17     10113949.11      2937450.09     10113428.52
#Sta/Elev= 30
  3735.8 1103.91  3794.2 1103.78  3834.7 1104.26    3879 1102.88  4010.2 1103.38
  4220.7 1098.94  4344.8 1093.95  4416.7 1088.68  4529.3 1079.72  4698.1 1082.13
  4772.7 1080.23  4807.4 1075.61  4852.4 1078.09  4902.1 1077.66  4974.6 1071.18
  5001.4 1069.79  5026.4 1071.23  5037.6 1071.93  5098.9 1070.77  5266.5  1076.6
  5308.6  1080.1    5369  1082.8  5494.8 1082.65  5679.1 1083.63  5940.5 1095.92
  6285.5 1103.18    6291 1103.27  6406.7 1105.59  6586.6 1113.07  6671.9 1114.91
#Mann= 15 ,-1 , 0
  3735.8      .1       0  3794.2     .05       0  3834.7      .1       0
    3879     .05       0  4010.2      .1       0  4344.8     .16       0
  4416.7      .1       0  4529.3     .16       0  4974.6     .07       0
  5026.4     .16       0  5037.6      .1       0  5266.5     .16       0
  5494.8      .1       0  6285.5     .05       0    6291      .1       0
Bank Sta=4772.7,5308.6
XS Rating Curve= 0 ,0
Exp/Cntr=0.3,0.1

Type RM Length L Ch R = 1 ,77633   ,731,731,731
BEGIN DESCRIPTION:
CYPRESS CREEK 117.0
END DESCRIPTION:
XS GIS Cut Line= 4
      2940032.85     10114178.28      2939439.08      10113881.4
      2938928.67     10113433.49      2937451.51     10113303.45
#Sta/Elev= 30
  4019.4 1093.51  4080.6 1093.46  4153.5 1092.56  4235.5 1090.56  4527.3 1084.57
  4599.9 1084.26  4738.4 1077.73  4756.4 1075.48  4788.6 1072.72  4817.1    1068
  4858.9  1069.8  4873.1 1067.79  4909.2 1068.66    4930 1066.75  4965.2  1066.2
  4993.4 1064.71  5015.4 1066.31  5029.7 1067.74  5043.3 1072.84  5085.7 1076.28
  5142.6  1071.9  5234.6 1076.73  5400.3 1078.58  5693.8 1081.67  5795.4 1085.04
  5974.8 1090.49  6124.2 1094.41  6283.8 1097.28    6531 1103.81  6845.2 1112.79
#Mann= 13 ,-1 , 0
  4019.4     .16       0  4080.6      .1       0  4153.5     .05       0
  4235.5      .1       0  4756.4     .16       0  4965.2     .07       0
  5015.4     .16       0  5400.3      .1       0  5795.4     .05       0
  5974.8      .1       0  6124.2     .05       0  6283.8      .1       0
    6531     .05       0
Bank Sta=4738.4,5234.6
XS Rating Curve= 0 ,0
Exp/Cntr=0.3,0.1

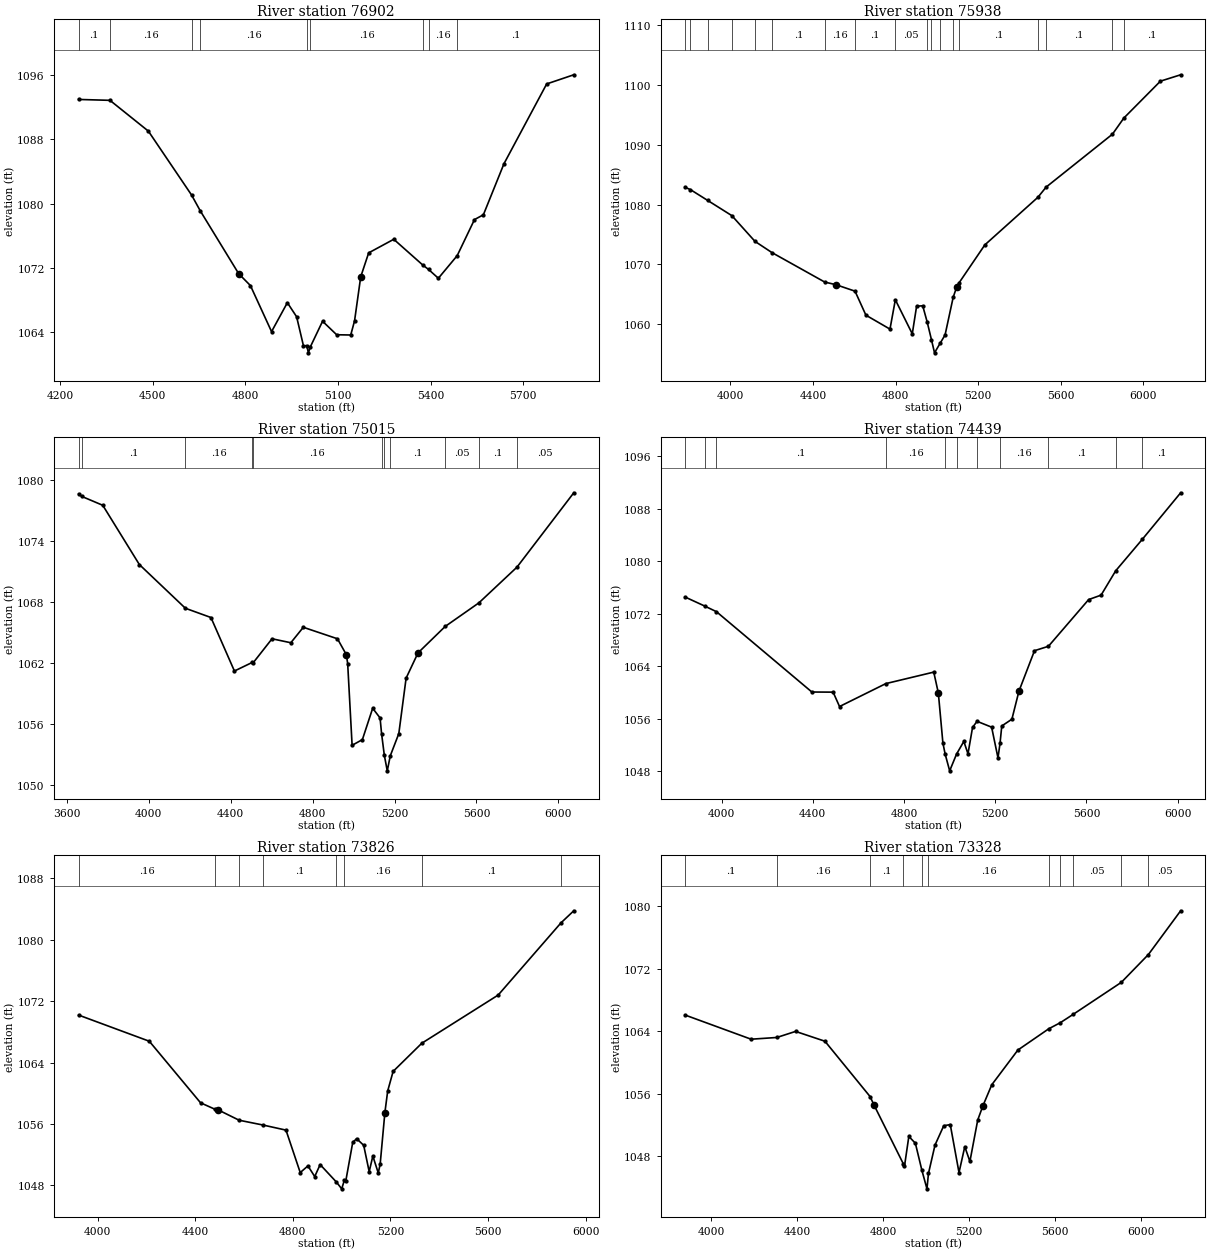
Type RM Length L Ch R = 1 ,76902   ,964,964,964
BEGIN DESCRIPTION:
CYPRESS CREEK 116.0
END DESCRIPTION:
XS GIS Cut Line= 3
      2940069.29     10113933.47      2939683.87     10113110.57
      2939329.72     10112511.63
#Sta/Elev= 30
  4259.7 1092.96  4361.3 1092.85  4485.7 1089.02  4625.5 1081.08  4654.2 1079.08
  4778.4 1071.28  4816.4  1069.8  4884.9 1064.07  4936.1 1067.67  4966.1 1065.92
  4988.2 1062.32    4999 1062.32  5004.3 1061.43  5010.3 1062.15  5050.2 1065.36
  5095.9 1063.68  5141.5 1063.65  5153.9 1065.42 5173.82 1070.89  5199.6 1073.87
  5280.9 1075.56  5375.1 1072.35  5393.5 1071.81  5425.4 1070.71  5486.4 1073.52
  5542.4 1078.01  5571.3 1078.61    5638 1084.96  5776.4 1094.89  5864.2 1096.03
#Mann= 9 ,-1 , 0
  4259.7      .1       0  4361.3     .16       0  4625.5      .1       0
  4654.2     .16       0    4999     .07       0  5010.3     .16       0
  5375.1      .1       0  5393.5     .16       0  5486.4      .1       0
Bank Sta=4778.4,5173.82
XS Rating Curve= 0 ,0
Exp/Cntr=0.3,0.1

Type RM Length L Ch R = 1 ,75938   ,923,923,923
BEGIN DESCRIPTION:
CYPRESS CREEK 115.0
END DESCRIPTION:
XS GIS Cut Line= 4
      2940371.39     10113876.15      2940668.25     10112954.32
      2940371.37     10112511.61      2939502.52     10112282.69
#Sta/Elev= 30
    3782 1082.85  3806.1 1082.49  3888.8  1080.7  4006.6 1078.14  4118.9 1073.83
  4200.8 1071.96    4457 1067.02  4510.6 1066.59  4603.7  1065.5  4656.5 1061.48
  4773.1 1059.15  4799.1 1064.06  4881.2 1058.36  4902.2 1062.99  4931.8 1063.05
  4953.6 1060.32  4974.2 1057.37    4989 1055.18  5016.2 1056.78  5040.1 1058.17
  5079.5 1064.48  5097.2 1066.27  5108.9 1066.94  5232.8 1073.24  5490.1 1081.21
  5529.8 1082.91  5851.4 1091.77  5906.7 1094.47  6083.9 1100.64    6182 1101.71
#Mann= 18 ,-1 , 0
    3782     .05       0  3806.1      .1       0  3888.8     .16       0
  4006.6      .1       0  4118.9     .05       0  4200.8      .1       0
    4457     .16       0  4603.7      .1       0  4799.1     .05       0
  4953.6     .16       0  4974.2     .07       0  5016.2     .16       0
  5079.5     .05       0  5108.9      .1       0  5490.1     .05       0
  5529.8      .1       0  5851.4     .05       0  5906.7      .1       0
Bank Sta=4510.6,5097.2
XS Rating Curve= 0 ,0
Exp/Cntr=0.3,0.1

Type RM Length L Ch R = 1 ,75015   ,576,576,576
BEGIN DESCRIPTION:
CYPRESS CREEK 114.0
END DESCRIPTION:
XS GIS Cut Line= 4
      2941629.18     10113844.07      2941364.43     10112663.52
      2941077.97     10112285.92      2940353.34      10112173.1
#Sta/Elev= 30
  3657.7 1078.66  3673.5 1078.41  3775.6 1077.54  3954.1 1071.72  4178.9 1067.42
  4303.7 1066.51  4418.3 1061.25  4505.7  1062.1  4510.2 1062.07  4601.9 1064.42
  4693.7 1064.03  4754.6 1065.55  4921.3 1064.42  4964.9 1062.85  4971.2 1061.97
  4992.8 1053.95    5043 1054.51  5093.2 1057.59  5129.3 1056.64  5136.8 1055.07
  5150.1 1052.97  5164.4 1051.44  5179.2 1052.92  5220.8  1055.1  5256.4 1060.55
  5314.4 1063.03  5447.1 1065.63  5611.7 1067.95  5797.6 1071.46  6074.9 1078.77
#Mann= 11 ,-1 , 0
  3657.7     .05       0  3673.5      .1       0  4178.9     .16       0
  4505.7      .1       0  4510.2     .16       0  5136.8      .1       0
  5150.1     .07       0  5179.2      .1       0  5447.1     .05       0
  5611.7      .1       0  5797.6     .05       0
Bank Sta=4964.9,5314.4
XS Rating Curve= 0 ,0
Exp/Cntr=0.3,0.1

Type RM Length L Ch R = 1 ,74439   ,613,613,613
BEGIN DESCRIPTION:
CYPRESS CREEK 113.0
END DESCRIPTION:
XS GIS Cut Line= 4
      2942032.83     10113488.17      2941776.76     10112555.01
      2941772.42     10112225.15      2941590.12     10111370.12
#Sta/Elev= 30
  3841.6 1074.51    3925 1073.18  3977.3 1072.31  4395.8 1060.08  4489.1 1060.06
  4517.2 1057.87  4720.3 1061.36  4930.5 1063.11  4950.6 1059.93  4970.6 1052.31
  4980.6 1050.61  5000.3 1048.08  5030.6 1050.64  5062.4 1052.56  5080.6 1050.67
  5100.6 1054.68  5120.3 1055.62  5184.3 1054.73  5212.2 1050.05  5221.2 1052.28
  5228.8 1054.91  5273.2 1055.94  5304.2 1060.22  5372.3 1066.37  5433.4 1067.04
  5609.8 1074.15  5664.4 1074.83  5728.4 1078.53  5845.8 1083.35  6013.4 1090.41
#Mann= 11 ,-1 , 0
  3841.6      .1       0    3925     .05       0  3977.3      .1       0
  4720.3     .16       0  4980.6     .07       0  5030.6     .16       0
  5120.3     .05       0  5221.2     .16       0  5433.4      .1       0
  5728.4     .16       0  5845.8      .1       0
#XS Ineff= 2 , 0
         4875.57  1062.3
Permanent Ineff=
       T       T
Bank Sta=4950.6,5304.2
XS Rating Curve= 0 ,0
Exp/Cntr=0.3,0.1

Type RM Length L Ch R = 1 ,73826   ,498,498,498
BEGIN DESCRIPTION:
CYPRESS CREEK 112.0
END DESCRIPTION:
XS GIS Cut Line= 3
      2942414.78     10113223.45      2942397.42     10112311.96
      2941885.43     10111318.36
#Sta/Elev= 30
  3922.2 1070.19    4212 1066.78    4422 1058.76  4481.7 1057.91    4492 1057.87
  4580.1 1056.49  4678.5 1055.86  4772.1  1055.2  4830.5 1049.67  4862.1 1050.54
  4889.9 1049.15  4912.1 1050.71  4978.6 1048.44  5000.5 1047.55  5011.7 1048.71
  5017.3 1048.59  5045.6 1053.59  5061.6 1054.09  5090.6 1053.22  5113.1 1049.79
  5128.1 1051.82  5150.3 1049.62  5158.1 1050.76 5177.42 1057.48    5189 1060.31
  5211.2 1062.85  5328.7 1066.52  5641.8  1072.8  5899.3 1082.21  5951.6 1083.78
#Mann= 8 ,-1 , 0
  3922.2     .16       0  4481.7      .1       0  4580.1     .16       0
  4678.5      .1       0  4978.6     .07       0  5011.7     .16       0
  5328.7      .1       0  5899.3     .16       0
Bank Sta=4492,5177.42
XS Rating Curve= 0 ,0
Exp/Cntr=0.3,0.1

Type RM Length L Ch R = 1 ,73328   ,546,546,546
BEGIN DESCRIPTION:
CYPRESS CREEK 111.0
END DESCRIPTION:
XS GIS Cut Line= 4
       2942601.4     10113167.01      2942831.44     10112364.04
      2942688.21     10111522.03      2942163.24     10111205.31
#Sta/Elev= 30
  3881.6 1066.06  4186.7 1062.98    4306  1063.2  4393.5 1063.98    4530 1062.72
    4740 1055.62  4757.8 1054.56  4894.1 1047.02  4899.8 1046.67  4920.1 1050.51
  4950.5 1049.64  4980.9 1046.16  5004.4 1043.79  5011.4 1045.76  5041.8  1049.4
  5082.4 1051.88  5112.8 1052.03  5153.4 1045.88  5180.3  1049.2  5204.1  1047.3
  5240.5 1052.62  5264.9 1054.46  5305.9 1057.14  5427.2 1061.59    5571 1064.32
  5624.7  1065.1  5683.4 1066.15  5908.2 1070.27  6034.1 1073.84  6184.1 1079.45
#Mann= 11 ,-1 , 0
  3881.6      .1       0    4306     .16       0    4740      .1       0
  4894.1     .16       0  4980.9     .07       0  5011.4     .16       0
    5571     .05       0  5624.7      .1       0  5683.4     .05       0
  5908.2      .1       0  6034.1     .05       0
Bank Sta=4757.8,5264.9
XS Rating Curve= 0 ,0
Exp/Cntr=0.3,0.1

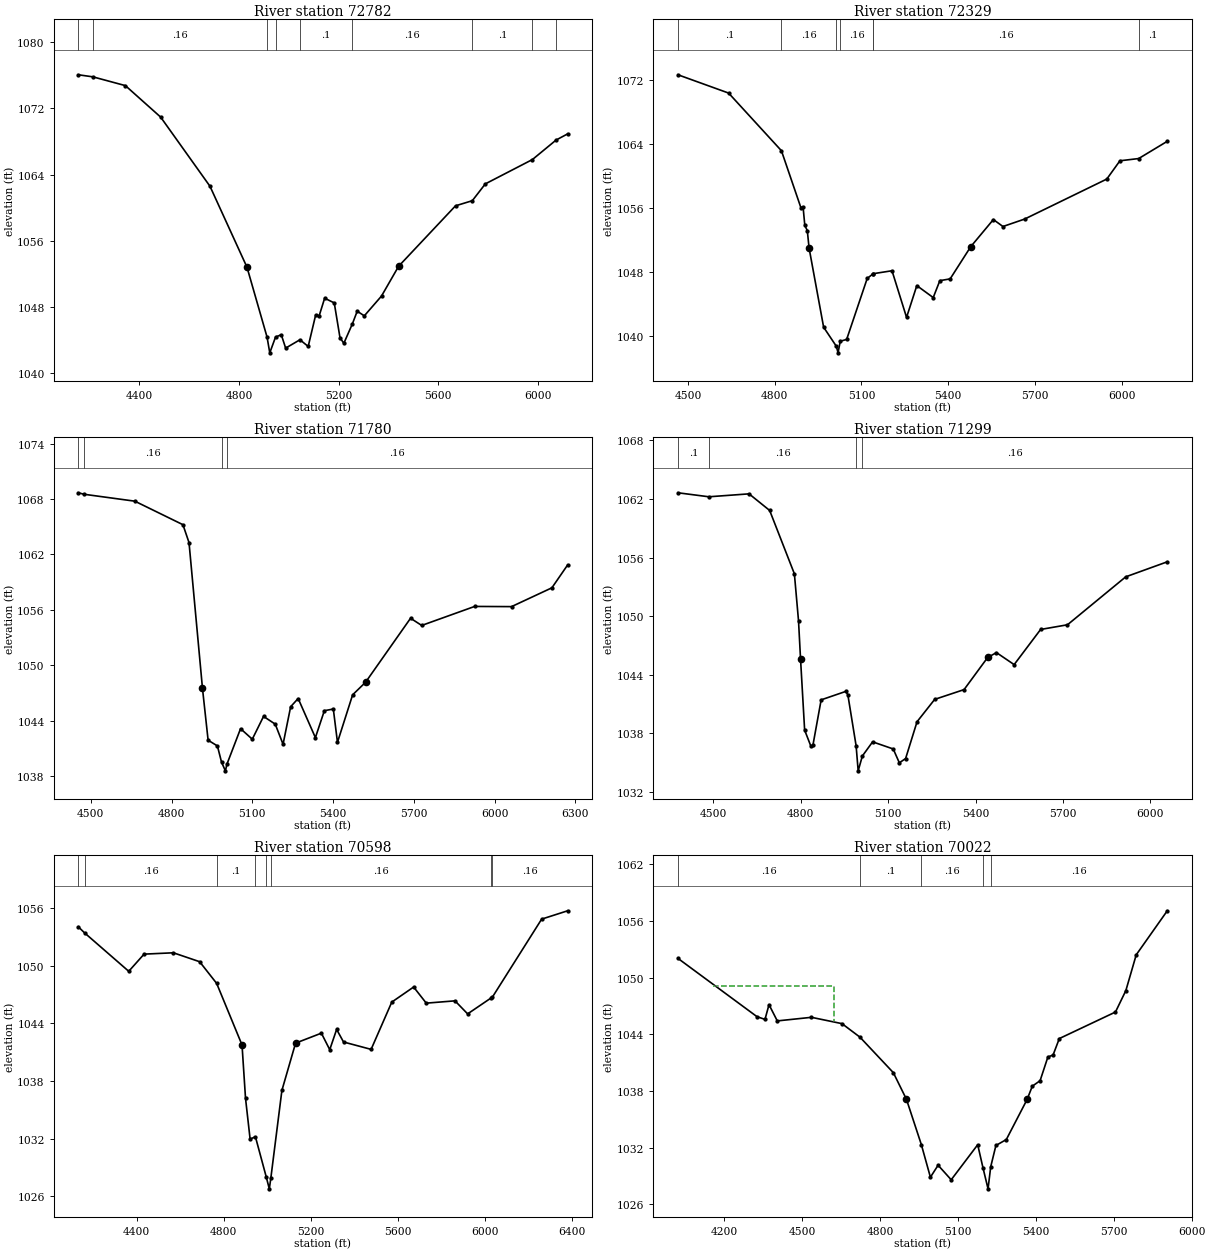
Type RM Length L Ch R = 1 ,72782   ,453,453,453
BEGIN DESCRIPTION:
CYPRESS CREEK 110.0
END DESCRIPTION:
XS GIS Cut Line= 4
      2943851.39     10112568.02      2943321.89      10112047.2
      2943039.78     10111430.88      2942562.93     10111170.78
#Sta/Elev= 30
  4155.4 1076.05  4213.9  1075.8  4344.3 1074.74  4485.7 1070.94  4683.8 1062.58
  4832.3  1052.8  4912.9 1044.35  4923.7 1042.46  4946.9 1044.37  4969.9 1044.65
  4987.4 1043.03  5044.8 1044.04  5077.9 1043.23    5108 1047.05  5121.9 1046.93
  5143.9 1049.06  5182.5 1048.49  5205.5 1044.29  5220.9 1043.61  5255.6 1045.99
  5274.6 1047.49  5303.1 1046.93  5372.1 1049.32  5440.8 1052.92  5669.1 1060.22
  5736.5 1060.84  5788.7 1062.87  5977.7 1065.81  6072.9 1068.17  6119.1 1068.91
#Mann= 9 ,-1 , 0
  4155.4      .1       0  4213.9     .16       0  4912.9     .07       0
  4946.9     .16       0  5044.8      .1       0  5255.6     .16       0
  5736.5      .1       0  5977.7     .05       0  6072.9     .16       0
Bank Sta=4832.3,5440.8
XS Rating Curve= 0 ,0
Exp/Cntr=0.3,0.1

Type RM Length L Ch R = 1 ,72329   ,549,549,549
BEGIN DESCRIPTION:
CYPRESS CREEK 109.0
END DESCRIPTION:
XS GIS Cut Line= 3
       2943968.6     10112177.42       2943343.6     10111318.03
      2942774.99     10111048.92
#Sta/Elev= 30
  4465.6 1072.67  4640.7 1070.38  4823.3 1063.16  4890.6 1056.03  4898.1 1056.15
  4904.2  1053.8  4912.8 1053.16  4918.9 1050.98  4969.2 1041.06  5013.2 1038.67
  5019.1 1037.85  5026.6  1039.3  5048.8 1039.53  5119.9 1047.17    5140 1047.74
  5140.4 1047.76  5205.6 1048.13  5255.9 1042.29  5291.4 1046.27  5348.1 1044.77
    5371 1046.89  5406.6 1047.11  5477.7 1051.14    5556 1054.54  5589.2 1053.67
    5664  1054.6  5948.1 1059.61  5993.6  1061.9  6058.4 1062.18  6157.3 1064.34
#Mann= 7 ,-1 , 0
  4465.6      .1       0  4823.3     .16       0  5013.2     .07       0
  5026.6     .16       0    5140      .1       0  5140.4     .16       0
  6058.4      .1       0
Bank Sta=4918.9,5477.7
XS Rating Curve= 0 ,0
Exp/Cntr=0.3,0.1

Type RM Length L Ch R = 1 ,71780   ,481,481,481
BEGIN DESCRIPTION:
CYPRESS CREEK 108.0
END DESCRIPTION:
XS GIS Cut Line= 3
      2944406.99      10111860.6      2943916.51     10111218.21
      2942948.64     10110931.75
#Sta/Elev= 30
  4453.6 1068.69  4474.6 1068.53  4663.5 1067.78  4842.2 1065.23  4864.8 1063.29
  4914.8 1047.48  4935.7 1041.87  4970.2 1041.25  4985.5  1039.5  4999.8 1038.55
  5006.4 1039.33  5056.2 1043.12  5099.8 1041.98  5141.6 1044.45  5185.1 1043.61
  5214.1 1041.43  5242.3  1045.5  5270.2 1046.39  5334.2 1042.15  5367.5 1045.07
  5400.8 1045.25  5416.2 1041.64  5472.5 1046.79  5520.5 1048.15  5687.7 1055.09
  5729.1 1054.31  5925.7 1056.37  6062.8 1056.35  6212.7 1058.39  6271.2 1060.87
#Mann= 4 ,-1 , 0
  4453.6      .1       0  4474.6     .16       0  4985.5     .07       0
  5006.4     .16       0
Bank Sta=4914.8,5520.5
XS Rating Curve= 0 ,0
Exp/Cntr=0.3,0.1

Type RM Length L Ch R = 1 ,71299   ,701,701,701
BEGIN DESCRIPTION:
CYPRESS CREEK 107.0
END DESCRIPTION:
XS GIS Cut Line= 3
      2944840.97     10111526.35      2944255.05     10110975.15
      2943387.95     10110848.75
#Sta/Elev= 30
    4378 1062.64  4484.2 1062.23  4622.2 1062.53    4693 1060.83  4777.9 1054.34
  4792.1 1049.53    4799 1045.64  4813.1 1038.33  4834.5 1036.69  4841.5 1036.77
  4869.8 1041.43  4954.8  1042.3  4961.6 1041.94  4989.9 1036.73    4997 1034.16
  5011.4 1035.68  5046.6 1037.13  5117.4  1036.4  5138.4 1034.98  5159.9 1035.42
  5199.2 1039.19  5259.8 1041.48  5360.7 1042.48  5441.7 1045.77    5472 1046.27
  5532.7 1045.04  5623.6 1048.64  5715.9 1049.12  5915.9 1054.03  6058.7 1055.57
#Mann= 4 ,-1 , 0
    4378      .1       0  4484.2     .16       0  4989.9     .07       0
  5011.4     .16       0
Bank Sta=4799,5441.7
XS Rating Curve= 0 ,0
Exp/Cntr=0.3,0.1

Type RM Length L Ch R = 1 ,70598   ,576,576,576
BEGIN DESCRIPTION:
CYPRESS CREEK 106.0
END DESCRIPTION:
XS GIS Cut Line= 4
      2945319.27     10111049.45      2944890.29     10110561.55
      2944499.98     10110428.99      2943375.11     10110802.72
#Sta/Elev= 30
  4132.2 1054.08  4161.2 1053.44  4363.8 1049.44  4434.1 1051.23  4568.8 1051.37
  4689.3 1050.44  4767.5 1048.18    4884 1041.76    4900 1036.21  4921.1 1031.95
  4945.5 1032.19    4995 1028.02  5009.3 1026.76  5016.1 1027.84  5067.1 1037.02
  5129.9 1041.95  5248.4 1042.99  5286.8 1041.27  5318.5 1043.38  5350.1 1042.07
  5476.8  1041.3  5571.8 1046.23  5672.1  1047.8  5730.1 1046.12    5862 1046.36
  5920.1    1045  6028.4 1046.67  6034.1 1046.76    6260 1054.88  6379.4 1055.75
#Mann= 8 ,-1 , 0
  4132.2      .1       0  4161.2     .16       0  4767.5      .1       0
  4945.5     .16       0    4995     .07       0  5016.1     .16       0
  6028.4      .1       0  6034.1     .16       0
Bank Sta=4884,5129.9
XS Rating Curve= 0 ,0
Exp/Cntr=0.3,0.1

Type RM Length L Ch R = 1 ,70022   ,720,720,720
BEGIN DESCRIPTION:
CYPRESS CREEK 105.0
END DESCRIPTION:
XS GIS Cut Line= 4
      2945426.92     10110983.79      2945166.51     10110259.01
      2944979.88     10109994.25      2944945.16     10109204.28
#Sta/Elev= 30
  4021.3 1052.03  4325.7 1045.86  4356.5 1045.57    4372 1047.13  4403.9 1045.41
  4535.5 1045.79  4653.1 1045.12  4722.3 1043.69  4850.9 1039.93  4901.4 1037.11
  4958.7 1032.32  4993.7 1028.86  5023.3 1030.13  5073.8 1028.59  5175.9  1032.3
    5196 1029.88  5215.7 1027.63    5226 1029.97    5246 1032.22  5286.1 1032.85
  5366.1 1037.09  5386.2  1038.5  5416.2 1039.08  5446.2 1041.59  5466.2  1041.8
  5490.2 1043.54  5706.5 1046.35  5746.5 1048.62  5786.5 1052.41  5906.1 1057.07
#Mann= 5 ,-1 , 0
  4021.3     .16       0  4722.3      .1       0  4958.7     .16       0
    5196     .07       0    5226     .16       0
#XS Ineff= 1 ,-1
 4155.68 4623.86 1049.14
Permanent Ineff=
       T
Bank Sta=4901.4,5366.1
XS Rating Curve= 0 ,0
Exp/Cntr=0.3,0.1

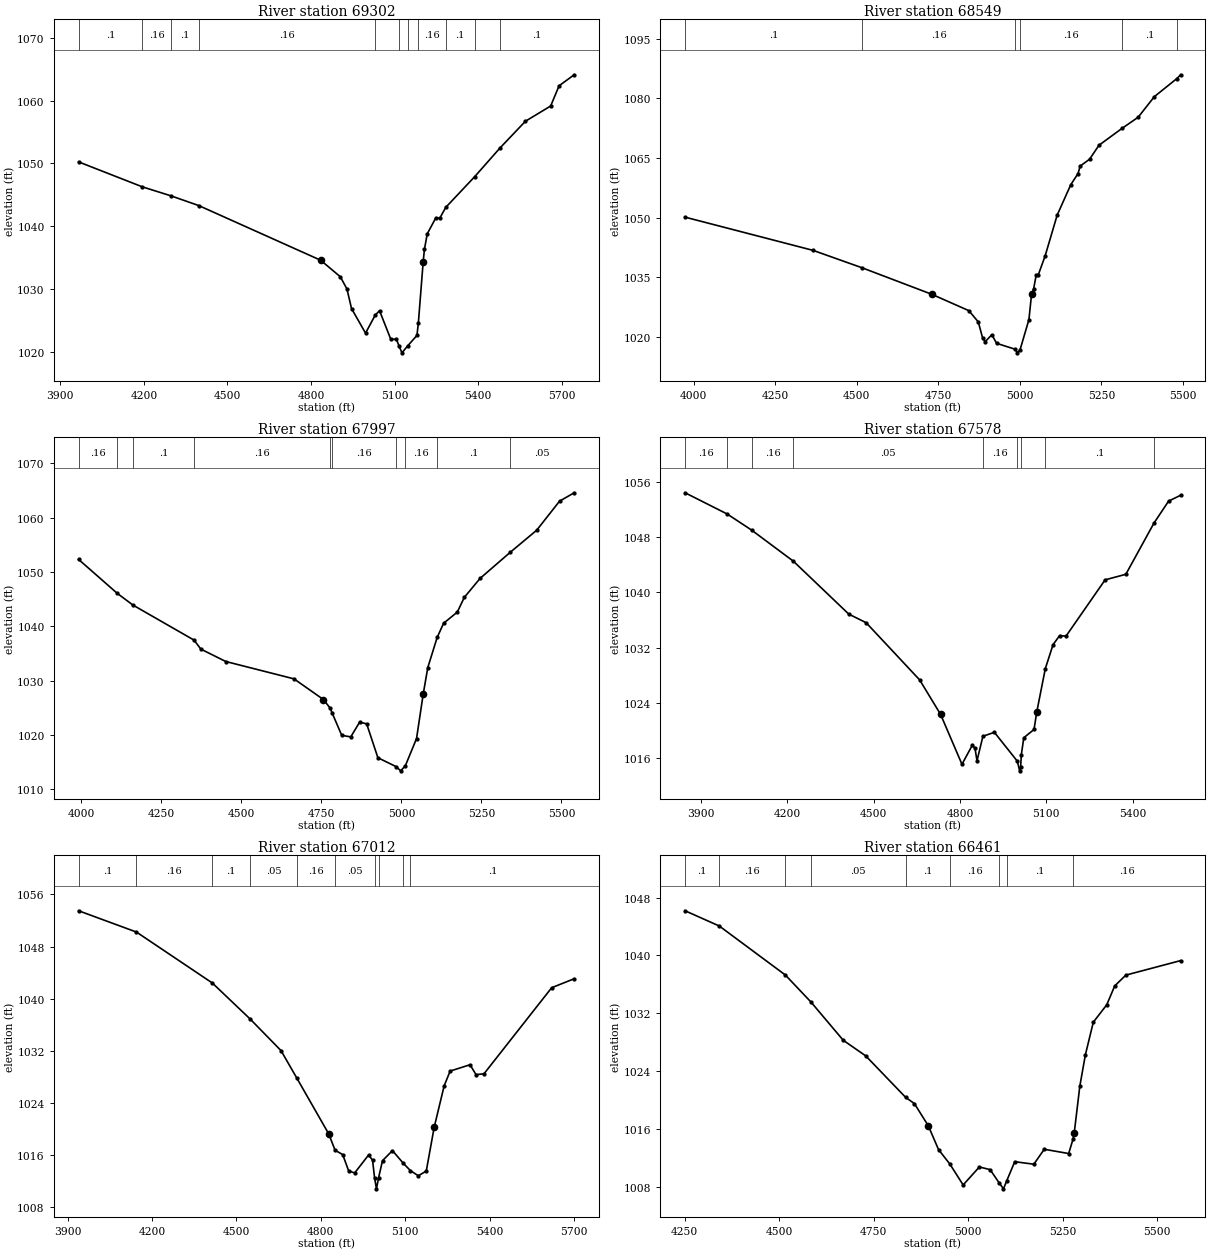
Type RM Length L Ch R = 1 ,69302   ,753,753,753
BEGIN DESCRIPTION:
CYPRESS CREEK 103.0
END DESCRIPTION:
XS GIS Cut Line= 2
      2945548.45     10110966.51      2945761.13     10109199.96
#Sta/Elev= 30
  3965.6 1050.25  4194.9 1046.28  4298.5 1044.84  4397.1 1043.31  4834.6 1034.63
  4905.1 1032.01  4929.1 1030.06  4945.4 1026.96  4995.8 1023.05  5030.5 1025.91
  5046.1 1026.61  5086.4 1022.08  5106.6 1022.08  5116.6 1020.95  5126.5 1019.92
  5146.8 1021.01  5180.4 1022.69  5185.4 1024.65 5202.77 1034.39  5207.3 1036.38
  5217.4 1038.83  5247.6 1041.32  5262.6 1041.33  5283.9 1043.03    5388 1047.92
  5478.1 1052.44  5569.9 1056.71  5660.5 1059.13  5690.7 1062.34  5744.9 1064.09
#Mann= 11 ,-1 , 0
  3965.6      .1       0  4194.9     .16       0  4298.5      .1       0
  4397.1     .16       0  5030.5      .1       0  5116.6     .07       0
  5146.8      .1       0  5185.4     .16       0  5283.9      .1       0
    5388     .16       0  5478.1      .1       0
Bank Sta=4834.6,5202.77
XS Rating Curve= 0 ,0
Exp/Cntr=0.3,0.1

Type RM Length L Ch R = 1 ,68549   ,552,552,552
BEGIN DESCRIPTION:
CYPRESS CREEK 102.0
END DESCRIPTION:
XS GIS Cut Line= 2
        2945670.     10111027.22      2946615.86     10109838.38
#Sta/Elev= 30
  3973.8  1050.1  4366.4 1041.73  4516.4 1037.35    4730 1030.68  4843.8 1026.55
  4872.6 1023.72  4885.6 1019.77  4893.4  1018.7  4914.2  1020.5  4928.6 1018.33
  4986.3 1016.82  4992.5 1015.93  5000.6 1016.67  5027.9 1024.31    5036 1030.73
  5042.4 1032.08  5050.4 1035.61  5056.8 1035.62  5077.6 1040.35  5114.5 1050.62
  5156.1 1058.26  5178.5 1061.09  5184.9 1062.96  5213.8 1064.69  5242.6 1068.21
  5313.5 1072.47  5362.7 1075.26  5412.4 1080.45    5481 1084.98    5493 1085.96
#Mann= 6 ,-1 , 0
  3973.8      .1       0  4516.4     .16       0  4986.3     .07       0
  5000.6     .16       0  5313.5      .1       0    5481     .05       0
Bank Sta=4730,5036
XS Rating Curve= 0 ,0
Exp/Cntr=0.3,0.1

Type RM Length L Ch R = 1 ,67997   ,419,419,419
BEGIN DESCRIPTION:
CYPRESS CREEK 101.0
END DESCRIPTION:
XS GIS Cut Line= 2
      2946025.89     10111339.74      2947032.86     10110163.49
#Sta/Elev= 30
  3991.2 1052.31  4112.3 1046.05  4161.1 1043.91    4352 1037.46  4373.1 1035.81
    4451 1033.53    4664 1030.34  4756.2 1026.53  4777.2 1024.94  4783.7 1024.01
  4813.3 1019.94  4841.6 1019.66  4869.2 1022.37  4891.2 1022.06  4926.3 1015.82
  4983.4 1014.18  4997.4 1013.41  5011.9 1014.32  5047.1 1019.36  5067.9 1027.54
  5082.2 1032.41  5111.5 1037.96  5131.6 1040.57  5174.4 1042.62  5196.3 1045.33
  5245.7 1048.83  5339.7 1053.62  5422.5 1057.69  5493.8 1063.03  5539.6 1064.58
#Mann= 10 ,-1 , 0
  3991.2     .16       0  4112.3     .05       0  4161.1      .1       0
    4352     .16       0  4777.2     .05       0  4783.7     .16       0
  4983.4     .07       0  5011.9     .16       0  5111.5      .1       0
  5339.7     .05       0
Bank Sta=4756.2,5067.9
XS Rating Curve= 0 ,0
Exp/Cntr=0.3,0.1

Type RM Length L Ch R = 1 ,67578   ,566,566,566
BEGIN DESCRIPTION:
CYPRESS CREEK 100.0
END DESCRIPTION:
XS GIS Cut Line= 2
       2946459.9     10111864.95      2947262.85      10110341.5
#Sta/Elev= 30
  3844.6 1054.47  3990.8 1051.39  4075.5 1049.06  4221.1 1044.53  4413.4 1036.86
  4473.8 1035.61  4659.9  1027.3  4732.5  1022.3  4806.8 1015.06  4842.6 1017.82
    4852  1017.4    4859 1015.57  4879.6 1019.13  4919.4  1019.7    4999 1015.52
  5007.3 1014.11  5010.5 1014.61  5013.2 1016.48  5021.6 1018.91  5057.2 1020.12
  5066.8 1022.67  5096.5 1028.96  5123.3 1032.42  5145.9 1033.73  5168.5 1033.67
  5304.2 1041.83  5376.3 1042.64  5474.3 1050.09  5524.9 1053.26  5566.7 1054.11
#Mann= 9 ,-1 , 0
  3844.6     .16       0  3990.8      .1       0  4075.5     .16       0
  4221.1     .05       0  4879.6     .16       0    4999     .07       0
  5013.2     .16       0  5096.5      .1       0  5474.3     .05       0
Bank Sta=4732.5,5066.8
XS Rating Curve= 0 ,0
Exp/Cntr=0.3,0.1

Type RM Length L Ch R = 1 ,67012   ,551,551,551
BEGIN DESCRIPTION:
CYPRESS CREEK 99.0
END DESCRIPTION:
XS GIS Cut Line= 2
      2946585.81     10112008.11      2947843.97     10110775.98
#Sta/Elev= 30
  3939.5 1053.49  4145.1 1050.22  4414.8 1042.39  4549.1 1036.86  4658.6 1032.02
  4715.4 1027.75  4828.4 1019.21  4850.8 1016.71  4877.9 1016.04  4899.1 1013.54
  4920.4 1013.22  4969.8 1015.97    4984 1015.19  4991.1  1012.5  4997.9 1010.78
  5005.2 1012.44  5019.4 1015.11  5054.7 1016.65  5093.9 1014.68  5118.8 1013.57
  5146.7 1012.79  5174.9 1013.51  5203.1 1020.25  5238.6 1026.62  5259.7 1028.87
  5330.4 1029.84  5351.7 1028.32    5380 1028.45  5620.5 1041.67  5700.5 1043.05
#Mann= 10 ,-1 , 0
  3939.5      .1       0  4145.1     .16       0  4414.8      .1       0
  4549.1     .05       0  4715.4     .16       0  4850.8     .05       0
  4991.1    .035       0  5005.2     .05       0  5093.9     .16       0
  5118.8      .1       0
Bank Sta=4828.4,5203.1
XS Rating Curve= 0 ,0
Exp/Cntr=0.3,0.1

Type RM Length L Ch R = 1 ,66461   ,616,616,616
BEGIN DESCRIPTION:
CYPRESS CREEK 98.0
END DESCRIPTION:
XS GIS Cut Line= 3
      2947128.28     10112134.03      2947579.71     10111838.87
      2948026.75     10111209.54
#Sta/Elev= 30
  4251.1 1046.19  4341.6 1044.08  4516.5 1037.29  4584.2 1033.55  4669.5 1028.26
  4729.2 1026.09  4834.5 1020.36  4858.1 1019.47  4894.7 1016.41  4921.7 1013.12
  4951.6 1011.12  4986.9 1008.22  5029.8 1010.71  5058.2 1010.34  5082.5 1008.48
  5093.6 1007.68  5102.5 1008.83  5123.4 1011.44  5173.9 1011.09  5201.5 1013.16
  5266.1 1012.57  5278.2 1014.65  5280.9 1015.46  5295.6  1021.9  5310.4 1026.26
  5331.3 1030.76    5367 1033.18  5387.9 1035.78  5417.4 1037.28  5562.4 1039.29
#Mann= 9 ,-1 , 0
  4251.1      .1       0  4341.6     .16       0  4516.5      .1       0
  4584.2     .05       0  4834.5      .1       0  4951.6     .16       0
  5082.5     .07       0  5102.5      .1       0  5278.2     .16       0
Bank Sta=4894.7,5280.9
XS Rating Curve= 0 ,0
Exp/Cntr=0.3,0.1