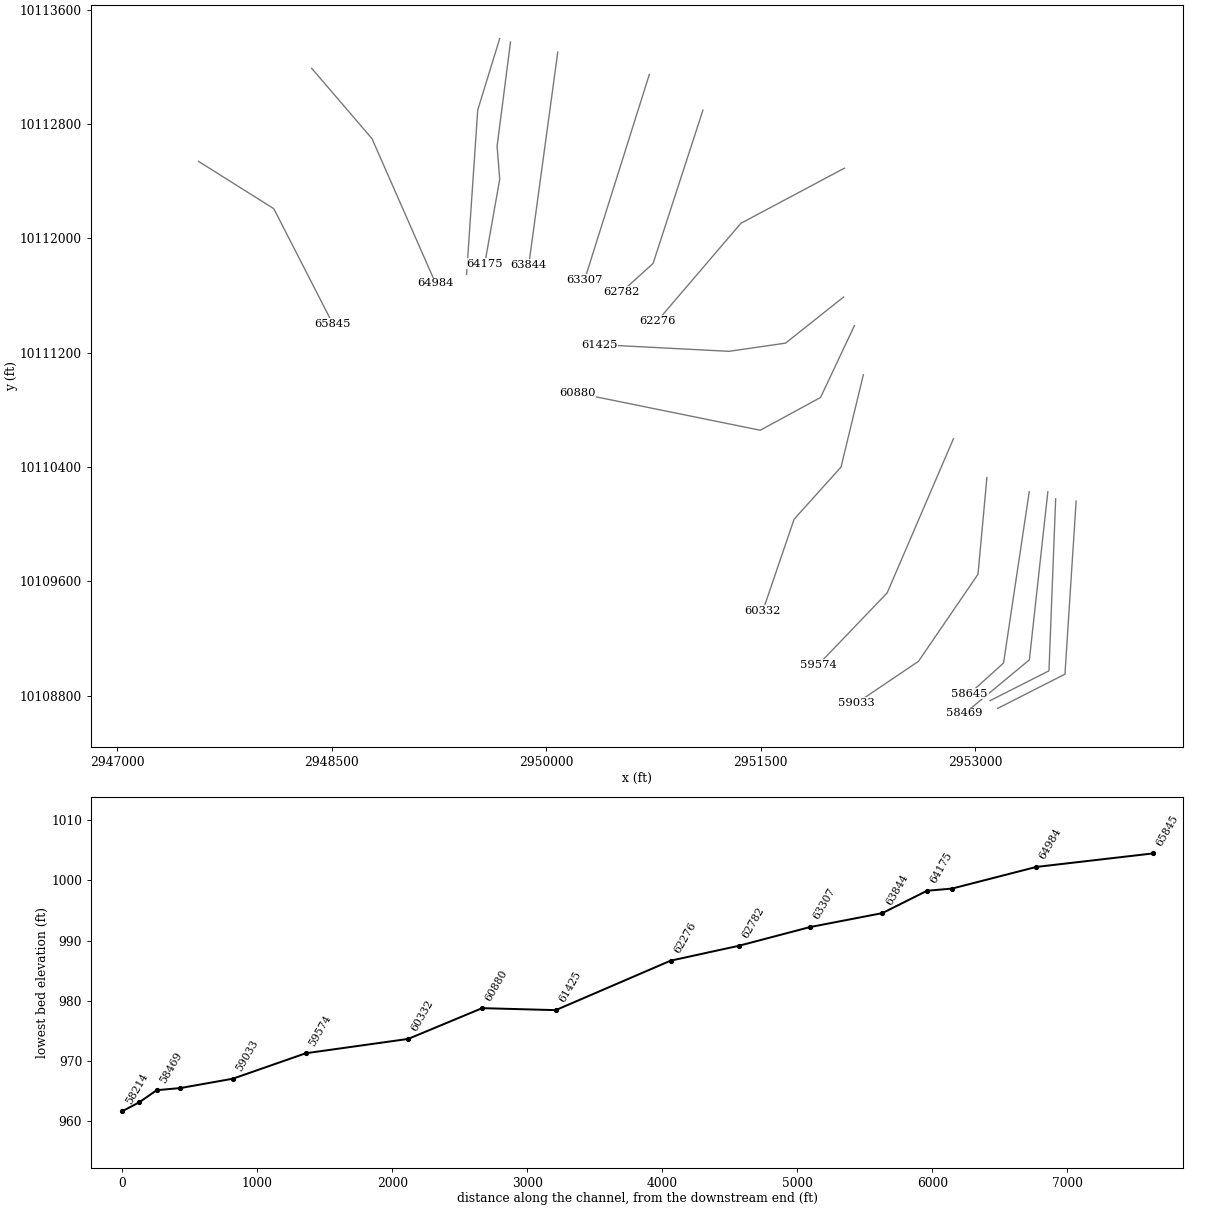
HEC-RAS study CYPRESS CREEK.prj: CYPRESS CREEK Base Level Engineering

--- CYPRESS CREEK.g01 (geometry) --- (continued)

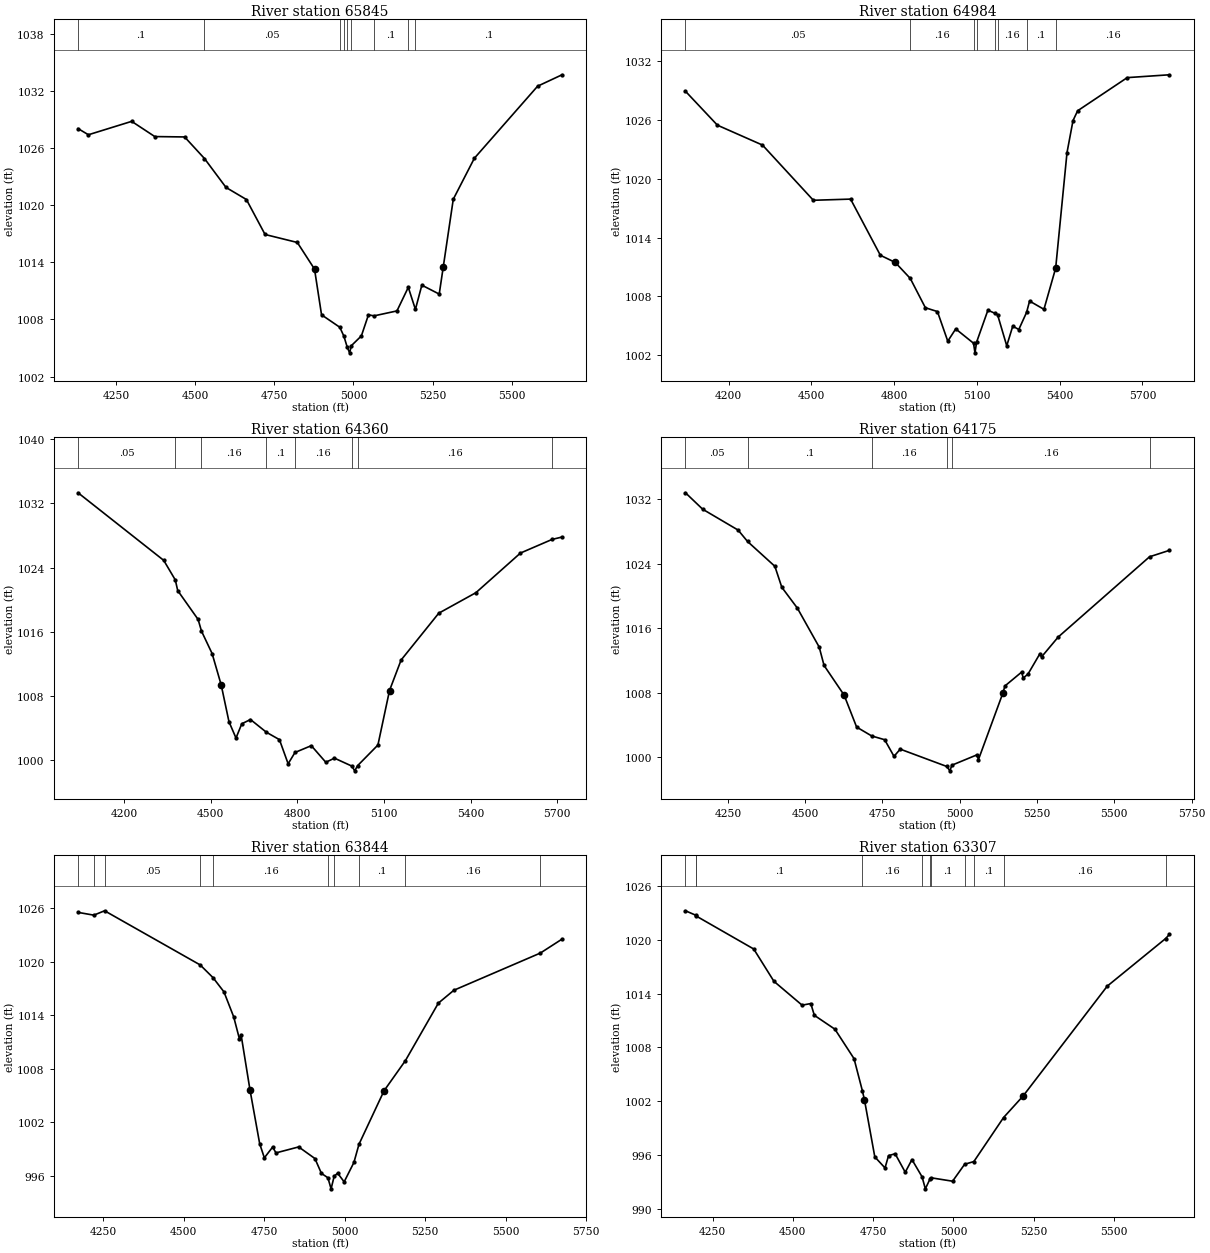
Type RM Length L Ch R = 1 ,65845   ,861,861,861
BEGIN DESCRIPTION:
CYPRESS CREEK 97.0
END DESCRIPTION:
XS GIS Cut Line= 3
      2947568.38     10112537.81      2948094.42     10112207.09
       2948508.5     10111399.75
#Sta/Elev= 30
  4130.1 1028.08  4162.8 1027.43  4299.5 1028.84  4372.5 1027.24  4466.7  1027.2
  4529.4 1024.93  4597.4 1021.89  4661.8 1020.62  4720.8 1016.94  4822.7  1016.1
    4877  1013.3  4899.2 1008.49  4956.9 1007.18  4969.8 1006.24    4980 1005.12
  4987.8 1004.49  4993.6 1005.25    5025 1006.27  5047.4 1008.49  5065.1 1008.38
  5137.4  1008.9  5173.2 1011.38  5195.7 1009.06    5216 1011.61  5270.9 1010.67
  5283.5 1013.49  5315.3 1020.65  5381.9 1024.96  5581.7 1032.54  5658.8 1033.74
#Mann= 9 ,-1 , 0
  4130.1      .1       0  4529.4     .05       0  4956.9      .1       0
  4969.8     .05       0    4980    .035       0  4993.6     .05       0
  5065.1      .1       0  5173.2     .05       0  5195.7      .1       0
Bank Sta=4877,5283.5
XS Rating Curve= 0 ,0
Exp/Cntr=0.3,0.1

Type RM Length L Ch R = 1 ,64984   ,624,624,624
BEGIN DESCRIPTION:
CYPRESS CREEK 96.0
END DESCRIPTION:
XS GIS Cut Line= 3
      2948360.03     10113188.87      2948781.92     10112696.67
      2949227.21     10111683.69
#Sta/Elev= 30
  4043.3 1028.93  4159.1 1025.47  4322.6 1023.44    4507 1017.81    4642 1017.93
    4750  1012.2    4804 1011.47  4858.4 1009.84  4913.2 1006.85  4956.9 1006.46
  4994.4 1003.44  5023.2 1004.69  5087.8 1003.23    5093 1002.25  5098.9 1003.34
  5139.9  1006.6  5166.3 1006.27  5174.8 1006.15  5208.2 1002.97    5230 1004.97
  5251.9 1004.63  5280.2 1006.38    5291 1007.53  5343.1 1006.69  5385.6 1010.89
  5426.7 1022.67  5448.5 1025.94  5465.3 1026.94  5645.1 1030.32  5798.1 1030.61
#Mann= 8 ,-1 , 0
  4043.3     .05       0  4858.4     .16       0  5087.8     .07       0
  5098.9     .16       0  5166.3      .1       0  5174.8     .16       0
  5280.2      .1       0  5385.6     .16       0
Bank Sta=4804,5385.6
XS Rating Curve= 0 ,0
Exp/Cntr=0.3,0.1

Type RM Length L Ch R = 1 ,64360   ,185,185,185
BEGIN DESCRIPTION:
CYPRESS CREEK 95.0
END DESCRIPTION:
XS GIS Cut Line= 3
      2949675.14     10113397.18       2949521.5     10112897.19
      2949443.51      10111748.1
#Sta/Elev= 30
  4041.4 1033.33  4337.9  1024.9  4377.9 1022.46  4386.3 1021.13  4456.9 1017.53
  4468.5 1016.08  4505.3 1013.28  4536.7 1009.37  4563.7 1004.77    4588 1002.74
    4608 1004.52  4638.1 1005.05  4693.3 1003.46  4738.3 1002.54  4768.4  999.53
  4792.1 1000.94  4848.6 1001.79  4898.7  999.72  4928.8 1000.23  4988.9  999.24
  4998.7  998.65  5008.9   999.3  5079.1 1001.87  5119.2 1008.67  5159.3 1012.47
  5289.6 1018.31  5418.2 1020.87  5572.2 1025.81  5681.6 1027.51  5716.2 1027.81
#Mann= 8 ,-1 , 0
  4041.4     .05       0  4377.9      .1       0  4468.5     .16       0
  4693.3      .1       0  4792.1     .16       0  4988.9     .07       0
  5008.9     .16       0  5681.6      .1       0
Bank Sta=4536.7,5119.2
XS Rating Curve= 0 ,0
Exp/Cntr=0.3,0.1

Type RM Length L Ch R = 1 ,64175   ,331,331,331
BEGIN DESCRIPTION:
CYPRESS CREEK 94.0
END DESCRIPTION:
XS GIS Cut Line= 5
      2949750.72     10113372.77      2949656.96     10112643.57
      2949667.38     10112515.97      2949675.19      10112411.8
      2949571.02     10111823.24
#Sta/Elev= 30
  4112.7 1032.78  4168.4 1030.74  4283.1 1028.15  4313.5 1026.74  4401.9 1023.66
  4424.3 1021.06  4474.7 1018.47  4545.3 1013.64    4561 1011.36  4625.9 1007.68
  4666.3 1003.72  4714.9 1002.62    4757 1002.15  4787.2 1000.09  4807.4 1000.98
  4958.1  998.83  4967.9  998.29  4974.5  998.99  5055.3 1000.27  5060.4  999.69
  5139.4 1007.94  5146.1 1008.82  5200.1 1010.54  5205.2  1009.8  5220.6 1010.29
  5259.3 1012.83  5264.4 1012.42  5318.4 1014.89  5613.7 1024.84  5678.1 1025.64
#Mann= 6 ,-1 , 0
  4112.7     .05       0  4313.5      .1       0  4714.9     .16       0
  4958.1     .07       0  4974.5     .16       0  5613.7      .1       0
Bank Sta=4625.9,5139.4
XS Rating Curve= 0 ,0
Exp/Cntr=0.3,0.1

Type RM Length L Ch R = 1 ,63844   ,537,537,537
BEGIN DESCRIPTION:
CYPRESS CREEK 93.0
END DESCRIPTION:
XS GIS Cut Line= 2
      2950081.58     10113302.76      2949878.45     10111813.15
#Sta/Elev= 30
  4171.7  1025.5  4220.7 1025.19  4254.1 1025.68  4551.1 1019.62  4590.9  1018.2
  4624.9 1016.61  4655.2 1013.81  4673.1 1011.33  4678.1 1011.82  4705.6 1005.68
  4735.9  999.62  4750.4  998.04  4776.3  999.25  4786.4  998.59    4857  999.26
  4907.5  997.96  4927.7   996.3  4947.8  995.81  4957.7  994.57  4967.4  995.99
  4978.1  996.32  4998.3  995.35  5028.6  997.52  5044.4  999.56  5122.2 1005.54
  5188.5 1008.91    5291 1015.35  5339.2 1016.79  5607.8 1020.95  5675.1 1022.51
#Mann= 10 ,-1 , 0
  4171.7     .05       0  4220.7      .1       0  4254.1     .05       0
  4551.1      .1       0  4590.9     .16       0  4947.8     .07       0
  4967.4     .16       0  5044.4      .1       0  5188.5     .16       0
  5607.8      .1       0
Bank Sta=4705.6,5122.2
XS Rating Curve= 0 ,0
Exp/Cntr=0.3,0.1

Type RM Length L Ch R = 1 ,63307   ,525,525,525
BEGIN DESCRIPTION:
Mapping XS d59d84bc
END DESCRIPTION:
XS GIS Cut Line= 2
      2950722.21     10113146.52      2950269.06     10111708.95
#Sta/Elev= 30
  4165.6 1023.23  4197.4 1022.74  4199.3 1022.64  4378.2 1018.97  4441.1 1015.37
  4528.8 1012.71  4555.9 1012.89    4567 1011.58  4631.1 1010.03  4690.6 1006.75
  4716.5 1003.18  4722.9 1002.19  4755.3   995.8  4787.1  994.57  4798.1  995.94
  4818.6  996.15  4850.1  994.09    4871   995.5  4902.5  993.58  4912.7  992.24
  4927.6  993.37  4930.7  993.47  4997.5  993.09  5035.1  994.98  5063.8  995.28
  5156.4 1000.19    5217 1002.58  5479.2 1014.83  5661.2 1020.14  5672.9  1020.6
#Mann= 11 ,-1 , 0
  4165.6     .05       0  4197.4     .16       0  4199.3      .1       0
  4716.5     .16       0  4902.5     .07       0  4927.6     .16       0
  4930.7      .1       0  5035.1     .16       0  5063.8      .1       0
  5156.4     .16       0  5661.2      .1       0
Bank Sta=4722.9,5217
XS Rating Curve= 0 ,0
Exp/Cntr=0.3,0.1

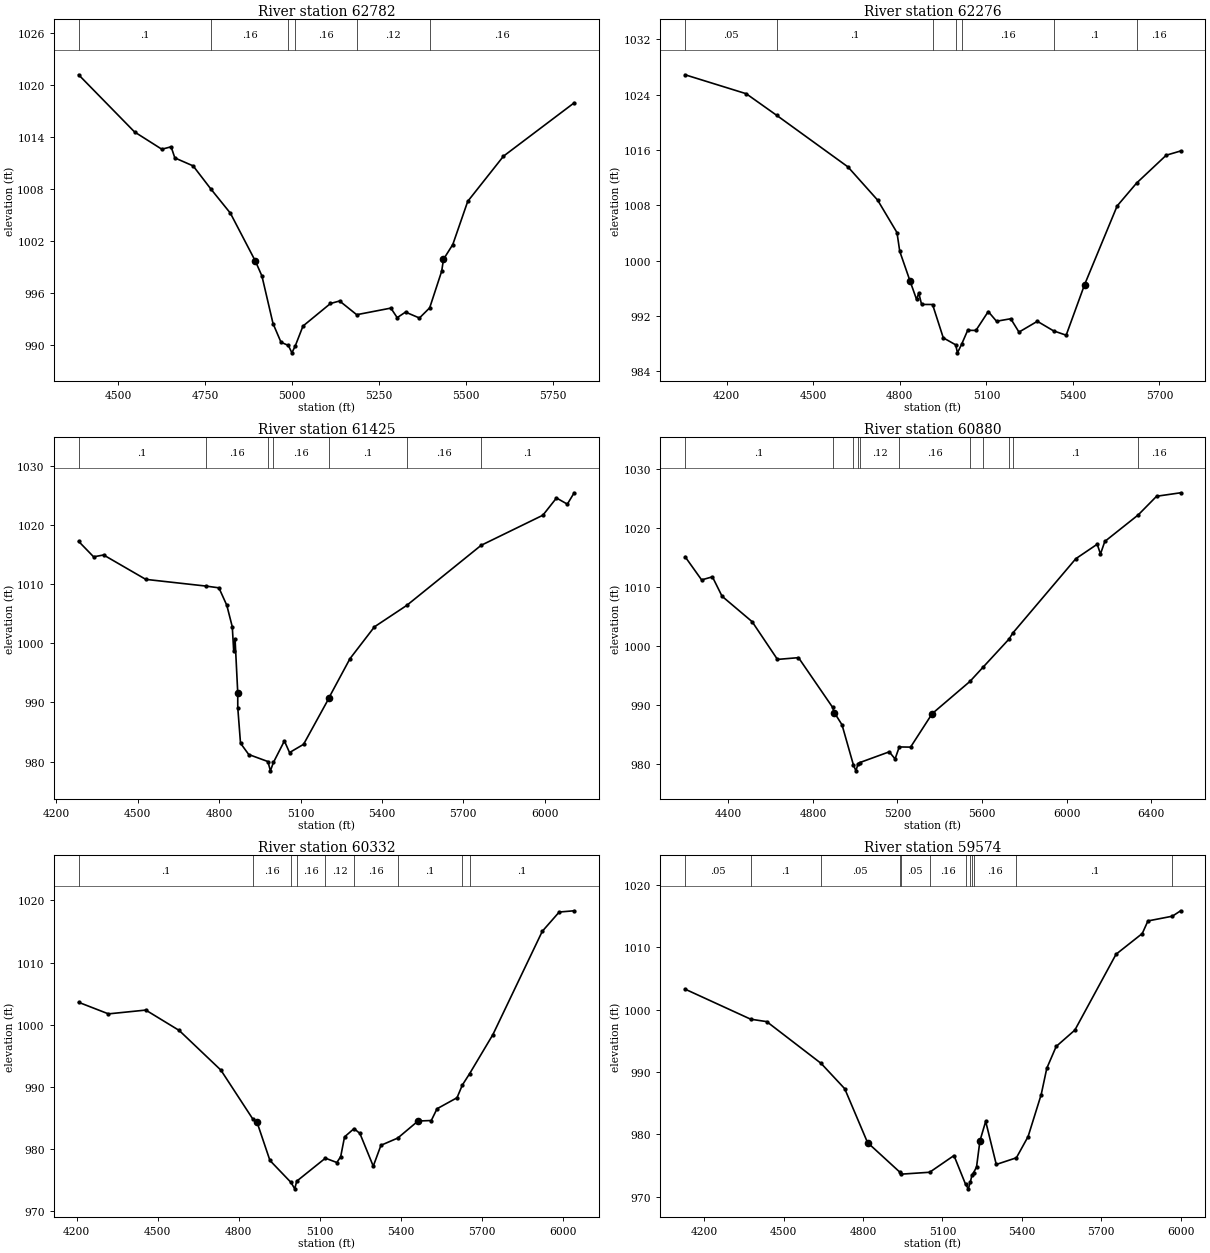
Type RM Length L Ch R = 1 ,62782   ,506,506,506
BEGIN DESCRIPTION:
CYPRESS CREEK 91.0
END DESCRIPTION:
XS GIS Cut Line= 3
      2951097.19     10112896.46      2950748.25     10111823.58
      2950529.49     10111625.66
#Sta/Elev= 30
  4386.7 1021.15  4547.3 1014.57  4625.6 1012.58  4652.3 1012.86    4663 1011.58
  4715.6 1010.66  4765.9 1008.03  4822.5 1005.22  4894.3   999.7  4913.1  997.99
    4945  992.51  4967.9  990.36    4989  989.99  4999.2  989.14  5008.9  989.94
    5031  992.22    5110  994.82  5136.2  995.11  5185.3  993.53  5283.4  994.29
  5301.6  993.19  5325.5  993.83  5365.5  993.15  5394.9  994.32  5429.4  998.54
  5434.6  999.91  5461.3 1001.61  5504.2 1006.58  5606.9 1011.78  5809.9 1017.92
#Mann= 6 ,-1 , 0
  4386.7      .1       0  4765.9     .16       0    4989     .07       0
  5008.9     .16       0  5185.3     .12       0  5394.9     .16       0
Bank Sta=4894.3,5434.6
XS Rating Curve= 0 ,0
Exp/Cntr=0.3,0.1

Type RM Length L Ch R = 1 ,62276   ,851,851,851
BEGIN DESCRIPTION:
CYPRESS CREEK 90.0
END DESCRIPTION:
XS GIS Cut Line= 3
      2952086.79     10112490.25      2951362.83     10112104.83
      2950779.51     10111422.56
#Sta/Elev= 30
  4055.6 1026.87  4267.5 1024.13    4373 1021.01  4620.1 1013.55  4723.1 1008.74
  4790.1 1004.05  4799.7 1001.34  4835.4  997.04    4858  994.38  4865.6  995.31
  4875.4  993.66  4913.4  993.65  4950.6  988.83  4993.5  987.82  4999.8  986.66
  5014.3  987.91  5035.2  989.92  5063.7   989.9  5106.5  992.63  5135.1  991.23
  5184.5  991.59    5213  989.66  5276.7  991.22  5332.8  989.84  5376.6  989.21
  5440.3  996.51  5553.3  1007.9  5620.5  1011.2  5723.5 1015.24  5773.4 1015.85
#Mann= 7 ,-1 , 0
  4055.6     .05       0    4373      .1       0  4913.4     .16       0
  4993.5     .07       0  5014.3     .16       0  5332.8      .1       0
  5620.5     .16       0
Bank Sta=4835.4,5440.3
XS Rating Curve= 0 ,0
Exp/Cntr=0.3,0.1

Type RM Length L Ch R = 1 ,61425   ,545,545,545
BEGIN DESCRIPTION:
CYPRESS CREEK 89.0
END DESCRIPTION:
XS GIS Cut Line= 4
      2952081.57      10111589.2      2951675.33     10111266.29
       2951279.5       10111209.      2950373.31     10111255.87
#Sta/Elev= 30
  4282.3  1017.2  4337.5 1014.59  4374.4  1014.9  4529.7 1010.78    4751 1009.65
  4799.3 1009.35  4828.4  1006.4  4848.6 1002.76  4853.8  998.65  4858.9 1000.63
 4868.66  991.66  4868.8  989.11  4878.9   983.1  4909.2  981.19  4979.9     980
  4989.1  978.43  5000.2  979.85  5040.6  983.48  5059.6  981.52  5111.3  982.91
  5204.2  990.66  5205.4  990.83  5282.3  997.38  5372.5 1002.76  5491.5 1006.38
  5765.6 1016.53  5993.3 1021.62  6043.4 1024.53  6083.4 1023.49  6108.6 1025.41
#Mann= 7 ,-1 , 0
  4282.3      .1       0    4751     .16       0  4979.9     .07       0
  5000.2     .16       0  5205.4      .1       0  5491.5     .16       0
  5765.6      .1       0
Bank Sta=4868.66,5204.2
XS Rating Curve= 0 ,0
Exp/Cntr=0.3,0.1

Type RM Length L Ch R = 1 ,60880   ,548,548,548
BEGIN DESCRIPTION:
CYPRESS CREEK 88.0
END DESCRIPTION:
XS GIS Cut Line= 4
       2952157.1     10111388.69      2951920.12     10110886.08
      2951498.25     10110656.91      2950217.02     10110917.33
#Sta/Elev= 30
  4195.7 1015.14  4273.8  1011.2  4324.9 1011.72  4370.5 1008.42  4512.7  1004.1
  4632.4  997.69  4731.9  997.99  4893.2  989.55  4901.2  988.66  4937.7  986.58
  4991.9  979.72  5003.4  978.76  5013.7  979.96  5022.2  980.17    5161  981.99
  5188.6  980.78  5208.4  982.82  5261.9  982.79  5363.9  988.47  5542.6  993.95
  5604.2  996.35  5728.8  1001.2  5744.3 1002.13  6043.2  1014.8  6144.4 1017.26
  6159.9  1015.6  6180.3 1017.73  6338.3 1022.24  6425.2 1025.41  6538.9    1026
#Mann= 11 ,-1 , 0
  4195.7      .1       0  4893.2     .16       0  4991.9     .07       0
  5013.7     .16       0  5022.2     .12       0  5208.4     .16       0
  5542.6      .1       0  5604.2     .16       0  5728.8     .05       0
  5744.3      .1       0  6338.3     .16       0
Bank Sta=4901.2,5363.9
XS Rating Curve= 0 ,0
Exp/Cntr=0.3,0.1

Type RM Length L Ch R = 1 ,60332   ,758,758,758
BEGIN DESCRIPTION:
CYPRESS CREEK 87.0
END DESCRIPTION:
XS GIS Cut Line= 4
       2952219.6     10111044.93      2952063.35      10110399.1
      2951735.22     10110034.52      2951516.47     10109393.89
#Sta/Elev= 30
  4207.8 1003.62    4318 1001.76    4456 1002.37  4579.4   999.1  4733.7  992.72
    4852  984.84  4867.1  984.37    4915   978.2  4992.8  974.67  5006.7  973.64
    5014  974.87    5120  978.57  5162.4  977.87  5176.6  978.82  5190.8  981.99
  5225.9  983.32  5247.6  982.54    5297  977.28  5325.4  980.64  5387.5   981.8
  5462.5  984.54  5511.5  984.62  5532.7  986.51  5606.6  988.28  5626.3  990.32
  5653.3  992.16  5739.1  998.42  5921.8 1015.03  5984.4 1018.13  6039.7 1018.33
#Mann= 9 ,-1 , 0
  4207.8      .1       0    4852     .16       0  4992.8     .07       0
    5014     .16       0    5120     .12       0  5225.9     .16       0
  5387.5      .1       0  5626.3     .05       0  5653.3      .1       0
Bank Sta=4867.1,5462.5
XS Rating Curve= 0 ,0
Exp/Cntr=0.3,0.1

Type RM Length L Ch R = 1 ,59574   ,541,541,541
BEGIN DESCRIPTION:
CYPRESS CREEK 86.0
END DESCRIPTION:
XS GIS Cut Line= 3
      2952849.82     10110597.05      2952386.27     10109518.89
      2951902.71     10109014.54
#Sta/Elev= 30
  4127.9 1003.29  4375.7  998.47  4436.3  998.08  4641.8  991.38    4731  987.32
  4817.3  978.68  4938.4  973.97  4942.9  973.61  5051.9  973.92  5143.8   976.6
  5187.4  972.01    5198  971.26  5205.5  972.33  5212.2  973.52  5217.7  973.84
    5229  974.75  5241.8  978.94  5263.6  982.09  5303.6  975.17  5379.6  976.24
  5423.8  979.64  5473.4  986.39  5494.5   990.6    5530   994.1  5600.5  996.72
  5756.2 1008.89  5855.2 1012.21  5876.6 1014.23  5968.9 1014.99  6000.2 1015.86
#Mann= 12 ,-1 , 0
  4127.9     .05       0  4375.7      .1       0  4641.8     .05       0
  4938.4      .1       0  4942.9     .05       0  5051.9     .16       0
  5187.4    .035       0  5205.5     .16       0  5212.2     .05       0
  5217.7     .16       0  5379.6      .1       0  5968.9     .05       0
Bank Sta=4817.3,5241.8
XS Rating Curve= 0 ,0
Exp/Cntr=0.3,0.1

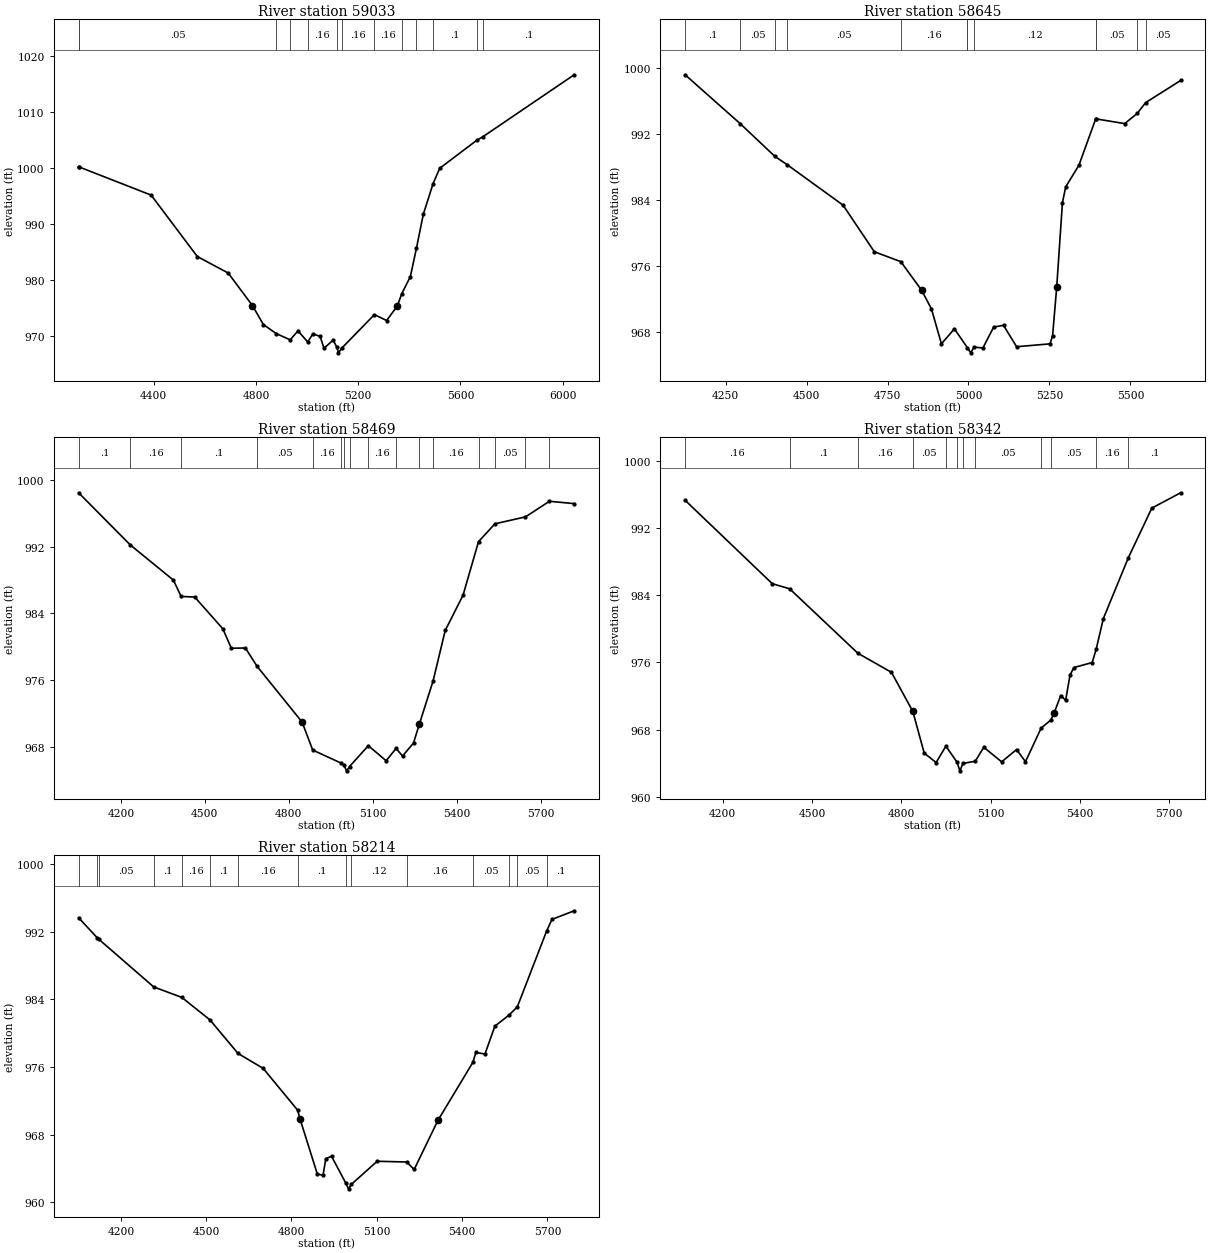
Type RM Length L Ch R = 1 ,59033   ,388,388,388
BEGIN DESCRIPTION:
CYPRESS CREEK 85.0
END DESCRIPTION:
XS GIS Cut Line= 4
      2953084.18      10110326.2      2953021.68      10109649.1
      2952605.02     10109039.73      2952173.61     10108748.65
#Sta/Elev= 30
  4106.1 1000.23  4108.8 1000.23  4389.8  995.21  4570.5  984.23    4691  981.29
  4786.1  975.47  4828.9  972.07  4879.4  970.46  4933.8  969.34  4964.2  970.96
  5002.1  968.96  5022.7  970.41  5050.9  969.96  5065.8  967.83  5101.7  969.29
  5116.6     968  5122.4  967.02  5137.5  967.95  5263.1  973.85  5310.9   972.8
  5352.9  975.39  5370.1  977.58  5403.7  980.62  5427.7  985.72  5454.5  991.78
  5492.8  997.28  5518.8 1000.01  5663.6 1005.01  5687.8 1005.65  6044.7 1016.72
#Mann= 13 ,-1 , 0
  4106.1      .1       0  4108.8     .05       0  4879.4      .1       0
  4933.8     .05       0  5002.1     .16       0  5116.6    .035       0
  5137.5     .16       0  5263.1     .16       0  5370.1     .12       0
  5427.7     .16       0  5492.8      .1       0  5663.6     .05       0
  5687.8      .1       0
Bank Sta=4786.1,5352.9
XS Rating Curve= 0 ,0
Exp/Cntr=0.3,0.1

Type RM Length L Ch R = 1 ,58645   ,176,176,176
BEGIN DESCRIPTION:
Mapping XS ec87342f
END DESCRIPTION:
XS GIS Cut Line= 3
      2953380.21     10110226.12      2953200.53     10109028.19
      2952963.57     10108814.67
#Sta/Elev= 30
  4124.9  999.17  4295.3  993.24  4402.1  989.28  4440.2  988.27  4612.7  983.37
  4709.2  977.72  4791.1  976.52  4855.4  973.05  4885.7  970.79  4916.5  966.56
  4956.5  968.38  4996.9  966.08  5006.8  965.47  5017.2  966.16  5044.6  966.06
  5077.8  968.59  5108.2  968.81  5148.6  966.21  5251.9  966.56  5259.8  967.56
 5272.44   973.4  5290.2  983.68  5300.3  985.59    5341   988.2  5392.9  993.82
  5393.1  993.83  5482.6  993.25  5520.8  994.48  5547.3   995.8  5655.2  998.48
#Mann= 12 ,-1 , 0
  4124.9      .1       0  4295.3     .05       0  4402.1      .1       0
  4440.2     .05       0  4791.1     .16       0  4996.9     .12       0
  4996.9     .07       0  5017.2     .12       0  5392.9     .16       0
  5393.1     .05       0  5520.8      .1       0  5547.3     .05       0
Bank Sta=4855.4,5272.44
XS Rating Curve= 0 ,0
Exp/Cntr=0.3,0.1

Type RM Length L Ch R = 1 ,58469   ,127,127,127
BEGIN DESCRIPTION:
CYPRESS CREEK 84.0
END DESCRIPTION:
XS GIS Cut Line= 3
      2953510.42     10110226.12      2953381.06     10109050.14
      2952927.97     10108675.17
#Sta/Elev= 30
  4048.9  998.45  4233.4   992.2  4387.6  987.98  4415.3  986.02  4463.8  985.95
  4564.4  982.14  4594.6  979.81  4644.9  979.84  4686.8  977.64  4847.6  970.96
  4885.6   967.6    4985  966.07    4997  965.77  5006.8  965.11  5017.1  965.62
  5084.4  968.13  5147.9  966.32  5183.7   967.8  5206.6  966.88  5245.9  968.45
  5266.7  970.71  5266.8  970.72  5315.6  975.86  5359.2  981.94    5423  986.18
  5478.2  992.59  5536.9  994.73    5646  995.56  5731.7  997.43  5820.1  997.15
#Mann= 16 ,-1 , 0
  4048.9      .1       0  4233.4     .16       0  4415.3      .1       0
  4686.8     .05       0  4885.6     .16       0    4985     .12       0
    4997     .07       0  5017.1     .12       0  5084.4     .16       0
  5183.7     .05       0  5266.8     .12       0  5315.6     .16       0
  5478.2      .1       0  5536.9     .05       0    5646      .1       0
  5731.7     .05       0
Bank Sta=4847.6,5266.7
XS Rating Curve= 0 ,0
Exp/Cntr=0.3,0.1

Type RM Length L Ch R = 1 ,58342   ,128,128,128
BEGIN DESCRIPTION:
Mapping XS 2efb02ee
END DESCRIPTION:
XS GIS Cut Line= 3
      2953565.11     10110176.64      2953518.23      10108973.5
      2953106.82     10108765.19
#Sta/Elev= 30
  4073.6  995.28  4366.7  985.36  4424.8  984.76  4654.4  977.09    4767  974.83
  4838.9  970.18  4877.1  965.23  4917.1  964.11    4950  966.05  4987.2  964.16
    4997  963.12  5007.2     964  5048.6  964.26  5077.3  965.92  5137.3  964.19
  5187.4  965.65  5217.4  964.21  5269.9  968.19  5303.1  969.18  5313.5  969.98
  5335.8  972.07  5352.4   971.5  5367.1  974.51  5380.3   975.4  5441.5  975.99
    5455  977.58  5479.1  981.22  5563.3  988.47    5642  994.35  5738.8  996.17
#Mann= 12 ,-1 , 0
  4073.6     .16       0  4424.8      .1       0  4654.4     .16       0
  4838.9     .05       0    4950     .16       0  4987.2     .07       0
  5007.2     .16       0  5048.6     .05       0  5269.9     .16       0
  5303.1     .05       0    5455     .16       0  5563.3      .1       0
Bank Sta=4838.9,5313.5
XS Rating Curve= 0 ,0
Exp/Cntr=0.3,0.1

Type RM Length L Ch R = 1 ,58214   ,210,210,210
BEGIN DESCRIPTION:
Mapping XS 916fd040
END DESCRIPTION:
XS GIS Cut Line= 3
      2953708.34     10110161.02      2953630.21     10108950.06
      2953158.88     10108710.49
#Sta/Elev= 30
  4051.7  993.64  4117.9  991.25  4121.8  991.13  4315.7  985.47  4414.5  984.23
  4513.3  981.58  4612.1  977.61  4700.3  975.85  4821.6  970.91  4830.6  969.81
  4890.7  963.38  4910.8   963.2  4920.8  965.18  4940.8  965.46  4990.9  962.29
  5000.7  961.61    5011  962.15  5101.2  964.87  5204.9  964.78  5231.4   963.9
  5314.9   969.7  5437.8  976.56  5448.4  977.73  5480.3  977.54  5515.2  980.84
  5564.5  982.13  5594.1  983.12  5696.7  992.05  5715.8  993.45  5793.9  994.47
#Mann= 15 ,-1 , 0
  4051.7     .05       0  4117.9     .16       0  4121.8     .05       0
  4315.7      .1       0  4414.5     .16       0  4513.3      .1       0
  4612.1     .16       0  4821.6      .1       0  4990.9     .07       0
    5011     .12       0  5204.9     .16       0  5437.8     .05       0
  5564.5     .16       0  5594.1     .05       0  5696.7      .1       0
Bank Sta=4830.6,5314.9
XS Rating Curve= 0 ,0
Exp/Cntr=0.3,0.1