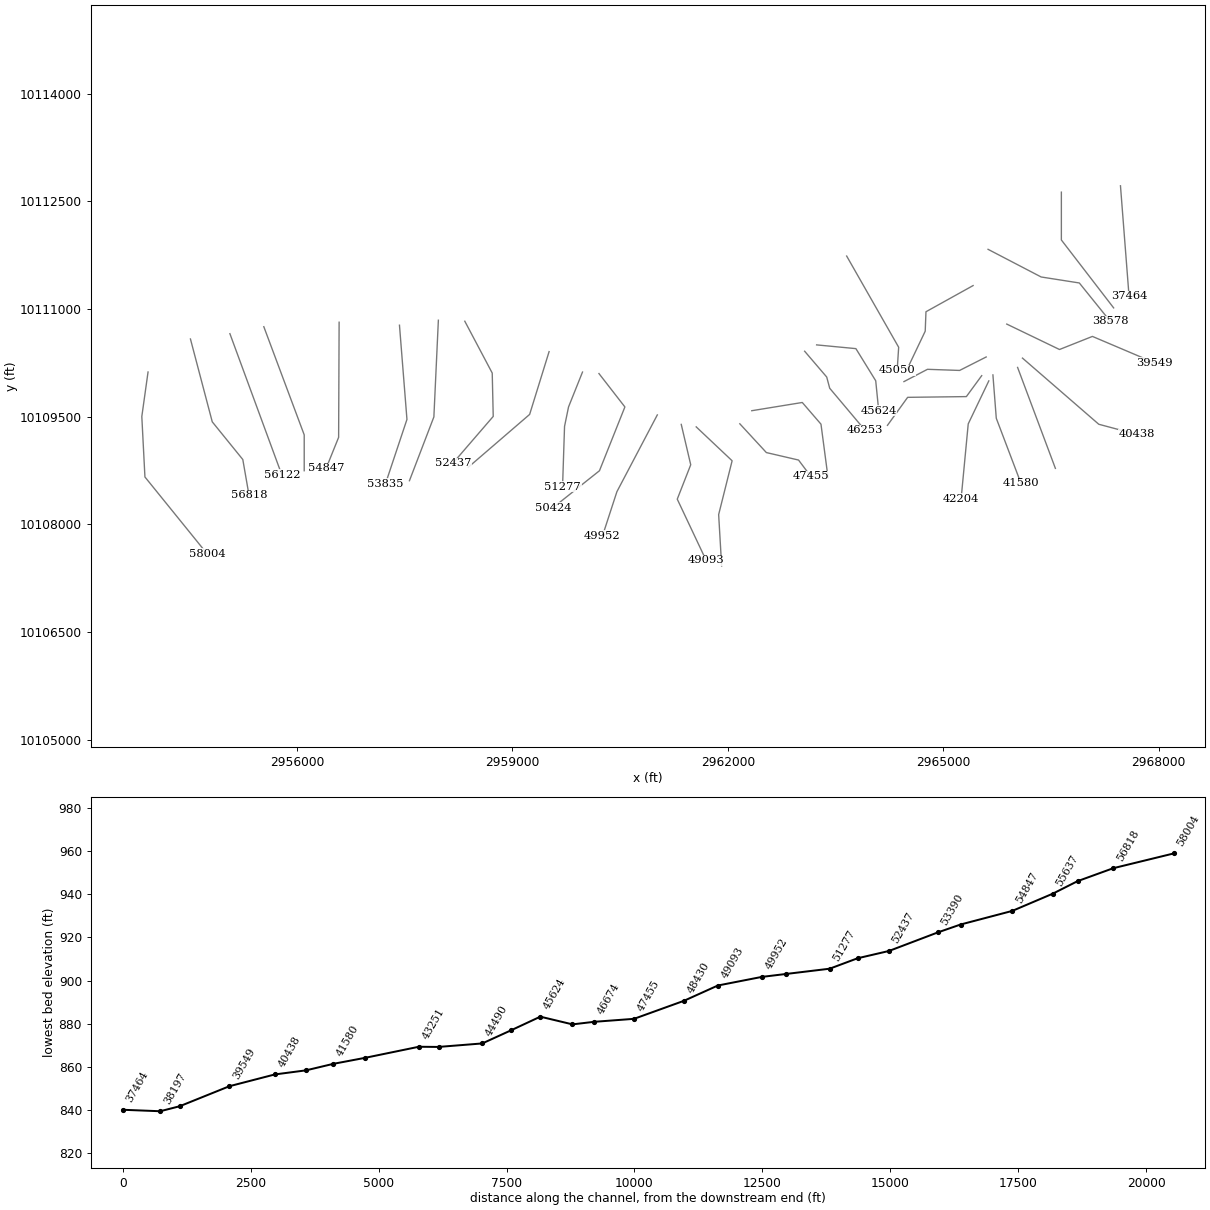
HEC-RAS study CYPRESS CREEK.prj: CYPRESS CREEK Base Level Engineering

--- CYPRESS CREEK.g01 (geometry) --- (continued)

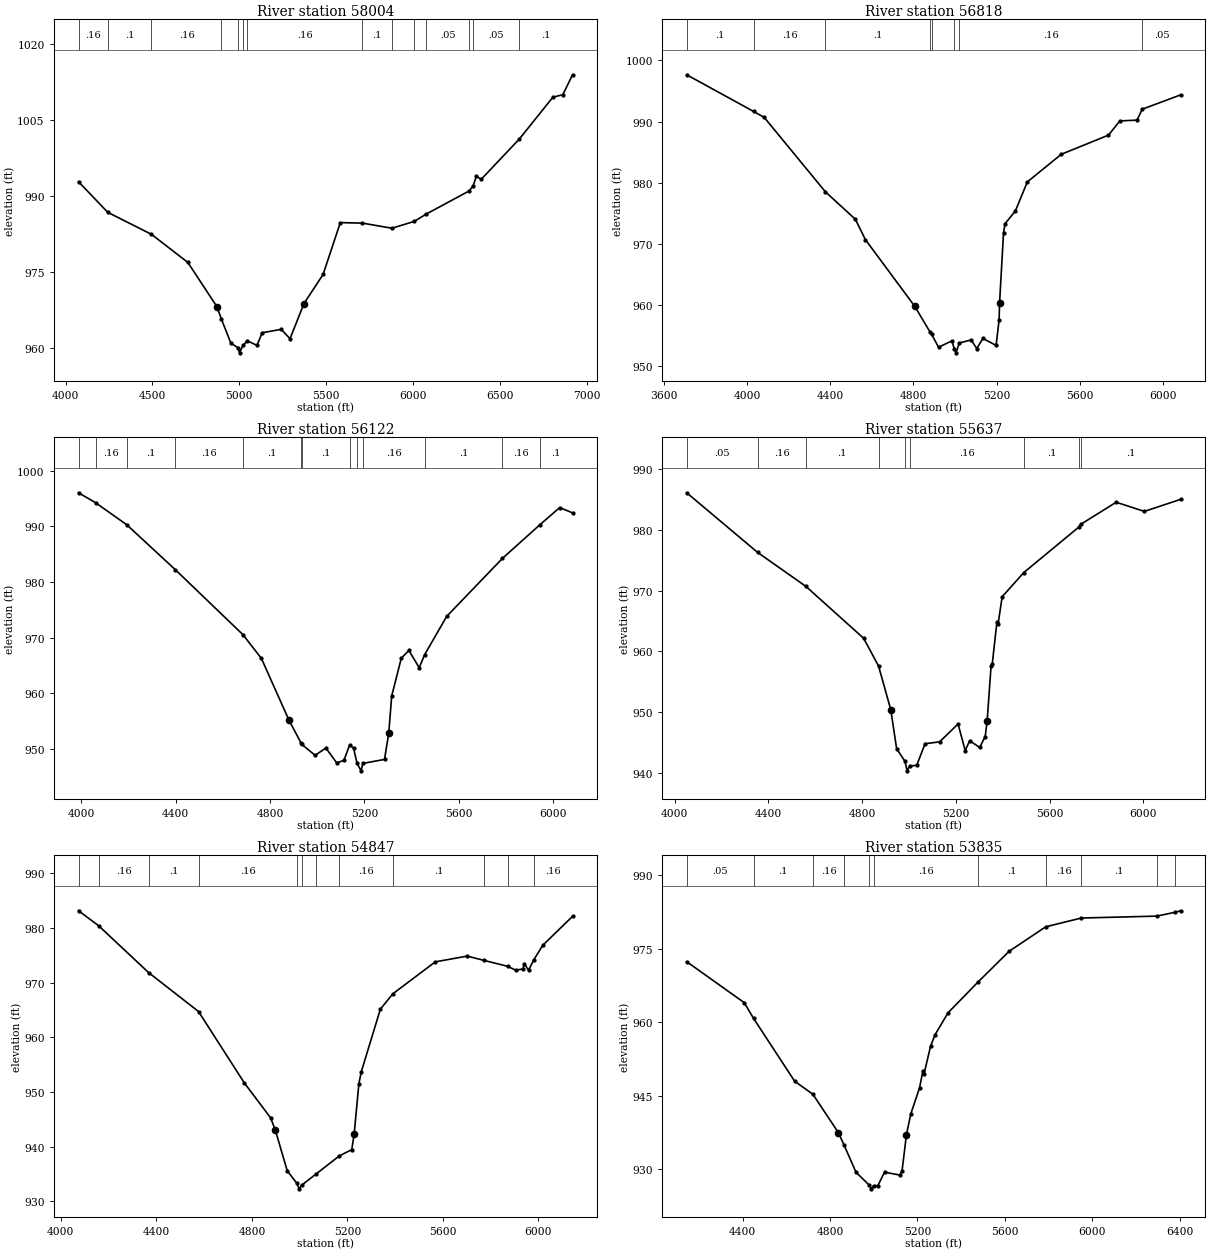
Type RM Length L Ch R = 1 ,58004   ,1186,1186,1186
BEGIN DESCRIPTION:
CYPRESS CREEK 83.0
END DESCRIPTION:
XS GIS Cut Line= 4
      2953927.06     10110123.92      2953840.26     10109503.27
      2953883.66     10108661.25      2954747.35     10107593.58
#Sta/Elev= 30
  4074.5  992.76    4243  986.71    4494  982.38  4703.5  976.83  4870.9  968.08
    4897   965.6  4951.1  960.89  4991.1     960  5000.9  958.97  5021.1  960.44
  5045.6  961.35  5101.3  960.44  5131.3  962.94  5241.4  963.61  5291.5  961.75
  5371.6  968.69  5481.8  974.45    5581  984.69  5708.6  984.59  5878.3  983.58
    6007  984.94  6075.4  986.38    6320   990.9  6344.7  991.86  6364.3  993.87
  6391.6  993.24  6611.1 1001.19  6804.1 1009.45  6861.6 1009.96  6917.6 1013.89
#Mann= 14 ,-1 , 0
  4074.5     .16       0    4243      .1       0    4494     .16       0
    4897      .1       0  4991.1     .07       0  5021.1      .1       0
  5045.6     .16       0  5708.6      .1       0  5878.3     .05       0
    6007      .1       0  6075.4     .05       0    6320      .1       0
  6344.7     .05       0  6611.1      .1       0
Bank Sta=4870.9,5371.6
XS Rating Curve= 0 ,0
Exp/Cntr=0.3,0.1

Type RM Length L Ch R = 1 ,56818   ,696,696,696
BEGIN DESCRIPTION:
CYPRESS CREEK 82.0
END DESCRIPTION:
XS GIS Cut Line= 4
      2954517.34     10110583.99      2954821.16     10109429.48
      2955246.51     10108904.31      2955333.01     10108406.91
#Sta/Elev= 30
  3710.6  997.66  4032.1  991.65  4083.1  990.68  4376.8   978.5  4521.6  973.97
  4569.1  970.67    4807  959.71  4879.5  955.55  4887.5  955.16  4921.1  953.02
  4985.1  954.06  4996.5   952.8  5005.6   952.1  5020.2  953.71  5077.8  954.22
    5105  952.79  5133.8  954.46  5197.7  953.32  5212.1  957.49 5214.29  960.21
  5233.5   971.8  5240.8  973.26  5290.4  975.35  5347.9  980.11    5511  984.63
  5737.9  987.77  5792.4   990.1  5875.2  990.23  5900.1  992.02  6085.1  994.37
#Mann= 8 ,-1 , 0
  3710.6      .1       0  4032.1     .16       0  4376.8      .1       0
  4879.5     .05       0  4887.5      .1       0  4996.5     .07       0
  5020.2     .16       0  5900.1     .05       0
Bank Sta=4807,5214.29
XS Rating Curve= 0 ,0
Exp/Cntr=0.3,0.1

Type RM Length L Ch R = 1 ,56122   ,485,485,485
BEGIN DESCRIPTION:
CYPRESS CREEK 81.0
END DESCRIPTION:
XS GIS Cut Line= 2
      2955066.83     10110657.77      2955789.05     10108692.47
#Sta/Elev= 30
  3988.8  996.05  4060.7  994.27  4193.3   990.3  4399.3  982.22  4685.8  970.55
  4763.7   966.3  4880.2  955.24  4931.5  951.13  4935.4  950.84  4991.5  948.89
  5037.2   950.2  5082.9  947.54  5113.4  947.97  5137.8  950.75  5154.4  950.16
    5169  947.48  5186.1   946.1  5194.2  947.44  5285.6  948.15  5303.5  952.87
  5316.1  959.56  5356.8  966.34  5388.8  967.73  5432.6  964.63  5455.8  966.98
  5549.2  973.85  5785.6  984.27  5942.9  990.26    6028  993.39  6082.6  992.44
#Mann= 13 ,-1 , 0
  3988.8      .1       0  4060.7     .16       0  4193.3      .1       0
  4399.3     .16       0  4685.8      .1       0  4931.5     .05       0
  4935.4      .1       0  5137.8     .16       0    5169     .07       0
  5194.2     .16       0  5455.8      .1       0  5785.6     .16       0
  5942.9      .1       0
Bank Sta=4880.2,5303.5
XS Rating Curve= 0 ,0
Exp/Cntr=0.3,0.1

Type RM Length L Ch R = 1 ,55637   ,790,790,790
BEGIN DESCRIPTION:
CYPRESS CREEK 80.0
END DESCRIPTION:
XS GIS Cut Line= 3
      2955539.06     10110754.97      2956101.54     10109248.06
      2956101.54     10108748.43
#Sta/Elev= 30
  4051.4  986.14  4353.5  976.32  4560.2   970.7  4806.4  962.15  4870.1  957.57
  4922.3  950.35  4947.2  943.94  4982.9  941.85  4991.8  940.29  5002.5  941.09
  5032.8  941.19  5068.5  944.76  5130.8  945.07  5209.3  948.02  5239.7  943.64
  5258.9  945.25  5301.6  944.15  5325.2  945.95  5333.6  948.59  5350.2  957.54
  5355.5  957.97  5375.2  964.87  5380.5  964.58  5397.6     969    5490  972.99
  5724.9  980.49  5732.2  980.92  5884.2  984.58  6004.2  983.07  6159.5  985.06
#Mann= 9 ,-1 , 0
  4051.4     .05       0  4353.5     .16       0  4560.2      .1       0
  4870.1     .16       0  4982.9     .07       0  5002.5     .16       0
    5490      .1       0  5724.9     .16       0  5732.2      .1       0
Bank Sta=4922.3,5333.6
XS Rating Curve= 0 ,0
Exp/Cntr=0.3,0.1

Type RM Length L Ch R = 1 ,54847   ,1012,1012,1012
BEGIN DESCRIPTION:
CYPRESS CREEK 79.0
END DESCRIPTION:
XS GIS Cut Line= 3
      2956587.65      10110817.5      2956580.71     10109213.34
      2956407.11      10108782.8
#Sta/Elev= 30
  4074.2  983.17  4158.6  980.42  4367.9  971.85  4576.6  964.74    4768   951.7
    4878  945.32    4898  943.07    4948  935.61    4988  933.33  4997.7  932.31
    5008  932.96  5068.3  935.01  5166.7  938.36    5218  939.47    5228  942.25
    5248  951.56    5258  953.72    5338  965.18  5389.7  967.97    5568  973.83
  5701.3  974.88    5773  974.08  5871.8     973  5904.4   972.3  5934.9  972.53
  5940.3  973.51  5958.3  972.29  5979.1  974.11  6018.1  976.87  6142.6  982.15
#Mann= 12 ,-1 , 0
  4074.2     .05       0  4158.6     .16       0  4367.9      .1       0
  4576.6     .16       0    4988     .07       0    5008     .16       0
  5068.3     .05       0  5166.7     .16       0  5389.7      .1       0
    5773     .16       0  5871.8      .1       0  5979.1     .16       0
Bank Sta=4898,5228
XS Rating Curve= 0 ,0
Exp/Cntr=0.3,0.1

Type RM Length L Ch R = 1 ,53835   ,445,445,445
BEGIN DESCRIPTION:
CYPRESS CREEK 78.0
END DESCRIPTION:
XS GIS Cut Line= 3
      2957427.93     10110775.86       2957532.1     10109463.34
      2957233.69     10108568.11
#Sta/Elev= 30
  4144.7  972.34  4407.7  963.99  4450.7  960.76  4638.4  947.96  4722.2  945.28
    4839  937.43  4864.6  934.93  4919.3  929.37  4979.4  926.77  4989.2  925.99
  4999.5  926.62  5019.6  926.66  5049.7  929.39  5119.9   928.8  5129.9  929.62
    5150  937.02    5170  941.29  5210.2  946.62  5225.5  950.12  5230.5  949.42
  5260.3  955.06  5280.4   957.4  5340.6  961.92    5478  968.21  5619.7  974.46
  5787.4  979.46  5949.9  981.25    6295  981.64    6379  982.42    6405  982.73
#Mann= 11 ,-1 , 0
  4144.7     .05       0  4450.7      .1       0  4722.2     .16       0
  4864.6      .1       0  4979.4     .07       0  4999.5     .16       0
    5478      .1       0  5787.4     .16       0  5949.9      .1       0
    6295     .05       0    6379      .1       0
Bank Sta=4839,5150
XS Rating Curve= 0 ,0
Exp/Cntr=0.3,0.1

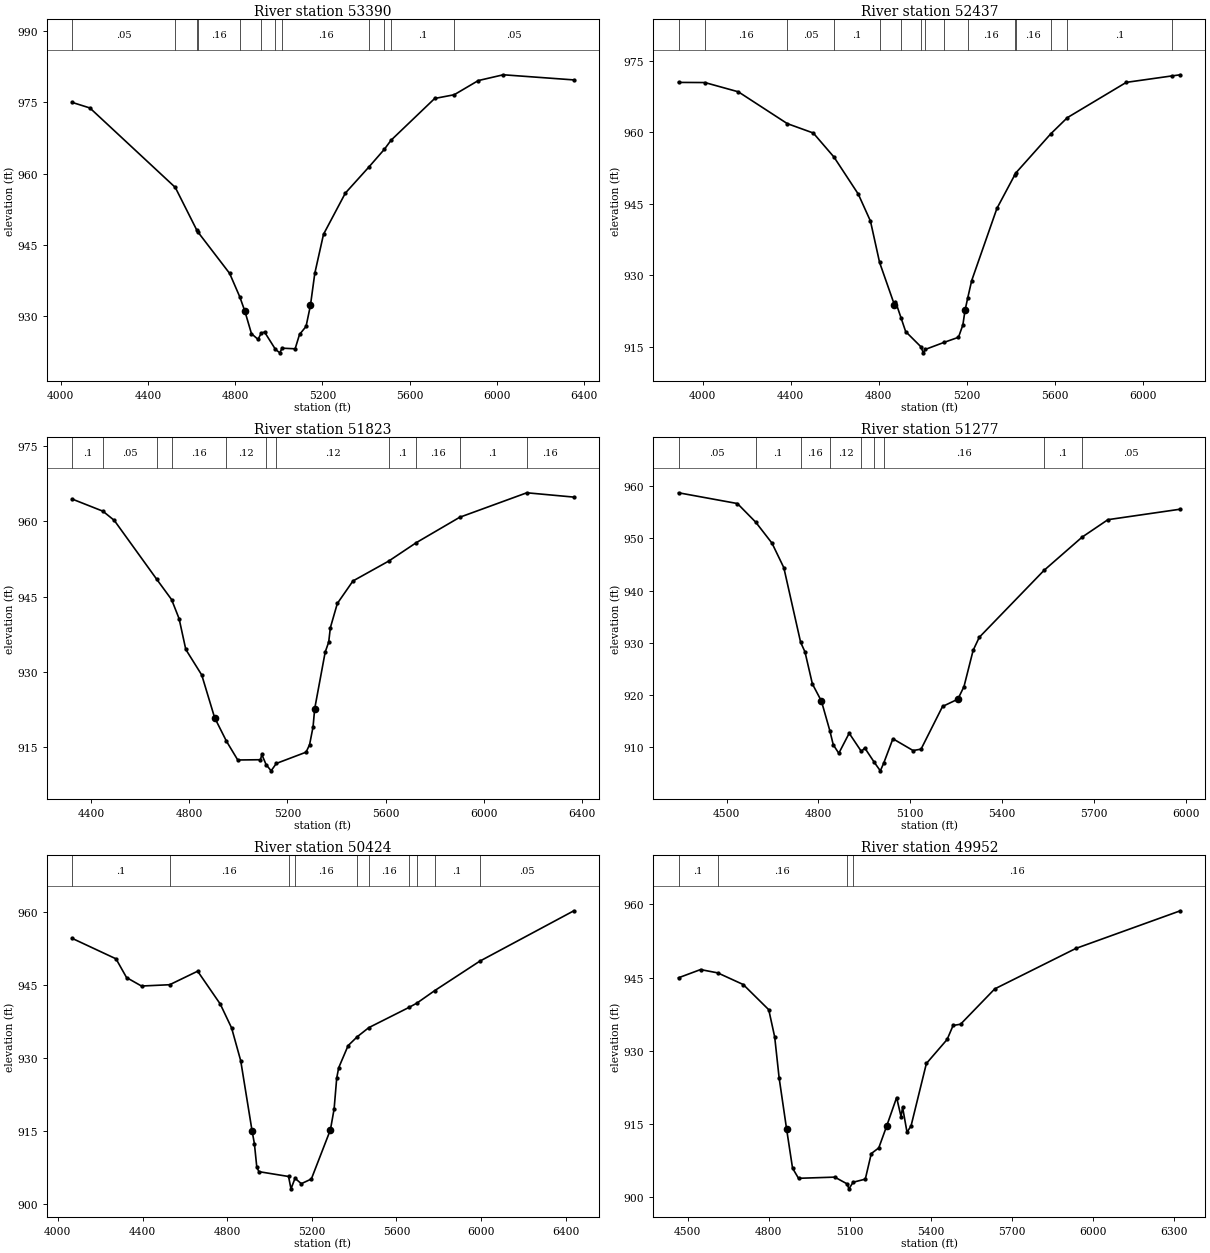
Type RM Length L Ch R = 1 ,53390   ,953,953,953
BEGIN DESCRIPTION:
CYPRESS CREEK 77.0
END DESCRIPTION:
XS GIS Cut Line= 3
       2957969.6     10110845.33       2957907.1     10109498.06
      2957566.83     10108609.18
#Sta/Elev= 30
  4052.2  974.99  4133.9  973.81  4525.3  957.11  4623.9  948.13  4629.6   947.7
  4774.6  939.02  4821.2  934.08  4844.6  931.05  4874.7  926.34  4904.7  925.16
  4919.8  926.48  4934.7  926.69  4984.8  923.04  5004.6  922.32  5014.8   923.3
  5074.9  923.17  5094.9  926.18  5124.9  927.87    5145  932.29    5165  939.04
    5205  947.25  5305.1  955.91  5413.9  961.44  5484.1  965.13  5514.5  967.02
  5714.7  975.81  5804.1  976.59  5914.4  979.57  6029.2  980.79  6352.7  979.71
#Mann= 12 ,-1 , 0
  4052.2     .05       0  4525.3     .16       0  4623.9      .1       0
  4629.6     .16       0  4821.2      .1       0  4919.8     .16       0
  4984.8     .07       0  5014.8     .16       0  5413.9      .1       0
  5484.1     .16       0  5514.5      .1       0  5804.1     .05       0
Bank Sta=4844.6,5145
XS Rating Curve= 0 ,0
Exp/Cntr=0.3,0.1

Type RM Length L Ch R = 1 ,52437   ,614,614,614
BEGIN DESCRIPTION:
CYPRESS CREEK 76.0
END DESCRIPTION:
XS GIS Cut Line= 4
      2958337.66     10110831.37       2958719.6     10110109.17
      2958733.49       10109505.      2958172.23     10108853.67
#Sta/Elev= 30
  3890.8  970.43  4010.7   970.4  4162.6  968.46  4385.2  961.79  4503.4  959.82
  4597.6  954.77  4707.8  947.02  4763.2  941.36  4804.8  932.68  4872.1  923.81
  4877.1  924.48    4903  920.97  4923.3  918.19  4993.3  914.97    5003  913.73
  5013.3  914.46  5099.5  915.95  5163.3  916.99  5183.3  919.57  5193.3  922.67
  5205.2  925.19  5223.4  928.87  5338.2  944.02    5419  951.01  5424.8  951.48
  5582.1  959.61  5658.3  963.04  5926.3  970.44    6135   971.8  6171.9  972.03
#Mann= 15 ,-1 , 0
  3890.8      .1       0  4010.7     .16       0  4385.2     .05       0
  4597.6      .1       0  4804.8     .05       0    4903     .16       0
  4993.3     .07       0  5013.3     .16       0  5099.5     .05       0
  5205.2     .16       0    5419     .05       0  5424.8     .16       0
  5582.1     .05       0  5658.3      .1       0    6135     .05       0
Bank Sta=4872.1,5193.3
XS Rating Curve= 0 ,0
Exp/Cntr=0.3,0.1

Type RM Length L Ch R = 1 ,51823   ,546,546,546
BEGIN DESCRIPTION:
CYPRESS CREEK 75.0
END DESCRIPTION:
XS GIS Cut Line= 3
      2959511.27      10110407.8      2959240.43     10109532.78
      2958387.45     10108797.69
#Sta/Elev= 30
  4323.5   964.4  4448.9  961.98  4495.2  960.15  4667.5  948.47  4728.5   944.4
    4759  940.61  4786.3  934.48  4851.2   929.4  4903.5  920.93  4951.8  916.23
  4997.7   912.5  5090.3  912.55  5095.5  913.61  5112.9   911.6  5133.5  910.34
  5154.7  911.81  5275.7  914.05    5290  915.53  5304.2   919.1  5310.8  922.68
  5353.6  933.97  5367.9  935.95  5374.5  938.79    5403  943.63  5466.6   948.1
  5612.2  952.06  5724.6  955.73    5901  960.77  6174.1  965.64  6365.5  964.78
#Mann= 11 ,-1 , 0
  4323.5      .1       0  4448.9     .05       0  4667.5      .1       0
  4728.5     .16       0  4951.8     .12       0  5112.9     .07       0
  5154.7     .12       0  5612.2      .1       0  5724.6     .16       0
    5901      .1       0  6174.1     .16       0
Bank Sta=4903.5,5310.8
XS Rating Curve= 0 ,0
Exp/Cntr=0.3,0.1

Type RM Length L Ch R = 1 ,51277   ,853,853,853
BEGIN DESCRIPTION:
CYPRESS CREEK 74.0
END DESCRIPTION:
XS GIS Cut Line= 4
      2959976.56     10110123.09       2959782.1     10109636.95
      2959726.54     10109366.12      2959698.81     10108527.24
#Sta/Elev= 30
  4343.2  958.73  4535.5  956.67  4595.6  953.09  4648.6  949.08  4687.2  944.39
    4742  930.12  4756.3  928.27  4780.5  922.14  4810.1  918.84  4837.4  913.21
  4848.7  910.49  4866.8  908.86  4900.7   912.7  4940.4  909.22  4951.7  909.88
  4982.4  907.16  5002.5   905.5  5013.7     907  5043.6  911.64  5109.4  909.39
  5135.5  909.65  5205.7  917.82  5255.7  919.22  5275.7  921.61  5305.7  928.57
  5325.7  931.06    5537  943.86  5661.7  950.24    5746  953.58  5982.6  955.59
#Mann= 9 ,-1 , 0
  4343.2     .05       0  4595.6      .1       0    4742     .16       0
  4837.4     .12       0  4940.4     .16       0  4982.4     .07       0
  5013.7     .16       0    5537      .1       0  5661.7     .05       0
Bank Sta=4810.1,5255.7
XS Rating Curve= 0 ,0
Exp/Cntr=0.3,0.1

Type RM Length L Ch R = 1 ,50424   ,472,472,472
BEGIN DESCRIPTION:
CYPRESS CREEK 73.0
END DESCRIPTION:
XS GIS Cut Line= 4
       2960205.7     10110102.23      2960566.82     10109636.95
      2960212.65     10108748.06      2959566.79     10108234.15
#Sta/Elev= 30
  4067.1  954.56  4274.8  950.34  4324.6  946.49  4395.2  944.75  4528.3  945.02
  4660.5   947.8  4767.2  941.06    4821  936.13  4864.1  929.38  4917.9  914.92
  4928.7  912.35  4940.1  907.49  4950.2  906.59  5090.1   905.6  5101.6  903.06
  5120.7  905.23  5150.4  904.12  5197.8  905.08  5287.9   915.2  5305.4  919.48
  5317.6   925.8  5326.9  927.94  5371.5   932.5  5415.1  934.34  5469.4   936.2
  5658.5  940.34  5696.6  941.24  5780.5   943.8  5993.4  949.85  6438.3  960.22
#Mann= 10 ,-1 , 0
  4067.1      .1       0  4528.3     .16       0  5090.1     .07       0
  5120.7     .16       0  5415.1      .1       0  5469.4     .16       0
  5658.5      .1       0  5696.6     .16       0  5780.5      .1       0
  5993.4     .05       0
Bank Sta=4917.9,5287.9
XS Rating Curve= 0 ,0
Exp/Cntr=0.3,0.1

Type RM Length L Ch R = 1 ,49952   ,859,859,859
BEGIN DESCRIPTION:
CYPRESS CREEK 72.0
END DESCRIPTION:
XS GIS Cut Line= 3
      2961018.21     10109525.84      2960455.71     10108456.39
      2960254.38     10107838.52
#Sta/Elev= 30
  4466.7  944.96  4548.2  946.64  4611.9  945.96  4706.4  943.57  4800.8  938.41
  4822.8  932.82  4839.2  924.44  4866.9  913.94  4888.9  905.94    4911  903.86
  5045.3   904.1  5090.5  902.73  5097.8   901.7  5113.1  903.05  5158.3  903.69
  5180.5  908.93  5208.2  910.09  5237.4  914.56  5274.3  920.41  5290.7   916.5
  5296.4  918.42  5312.8   913.3  5327.8  914.61  5384.5  927.39  5461.4  932.32
  5483.4  935.18  5511.1  935.44  5637.7  942.68    5938  950.97  6324.9  958.69
#Mann= 4 ,-1 , 0
  4466.7      .1       0  4611.9     .16       0  5090.5     .07       0
  5113.1     .16       0
Bank Sta=4866.9,5237.4
XS Rating Curve= 0 ,0
Exp/Cntr=0.3,0.1

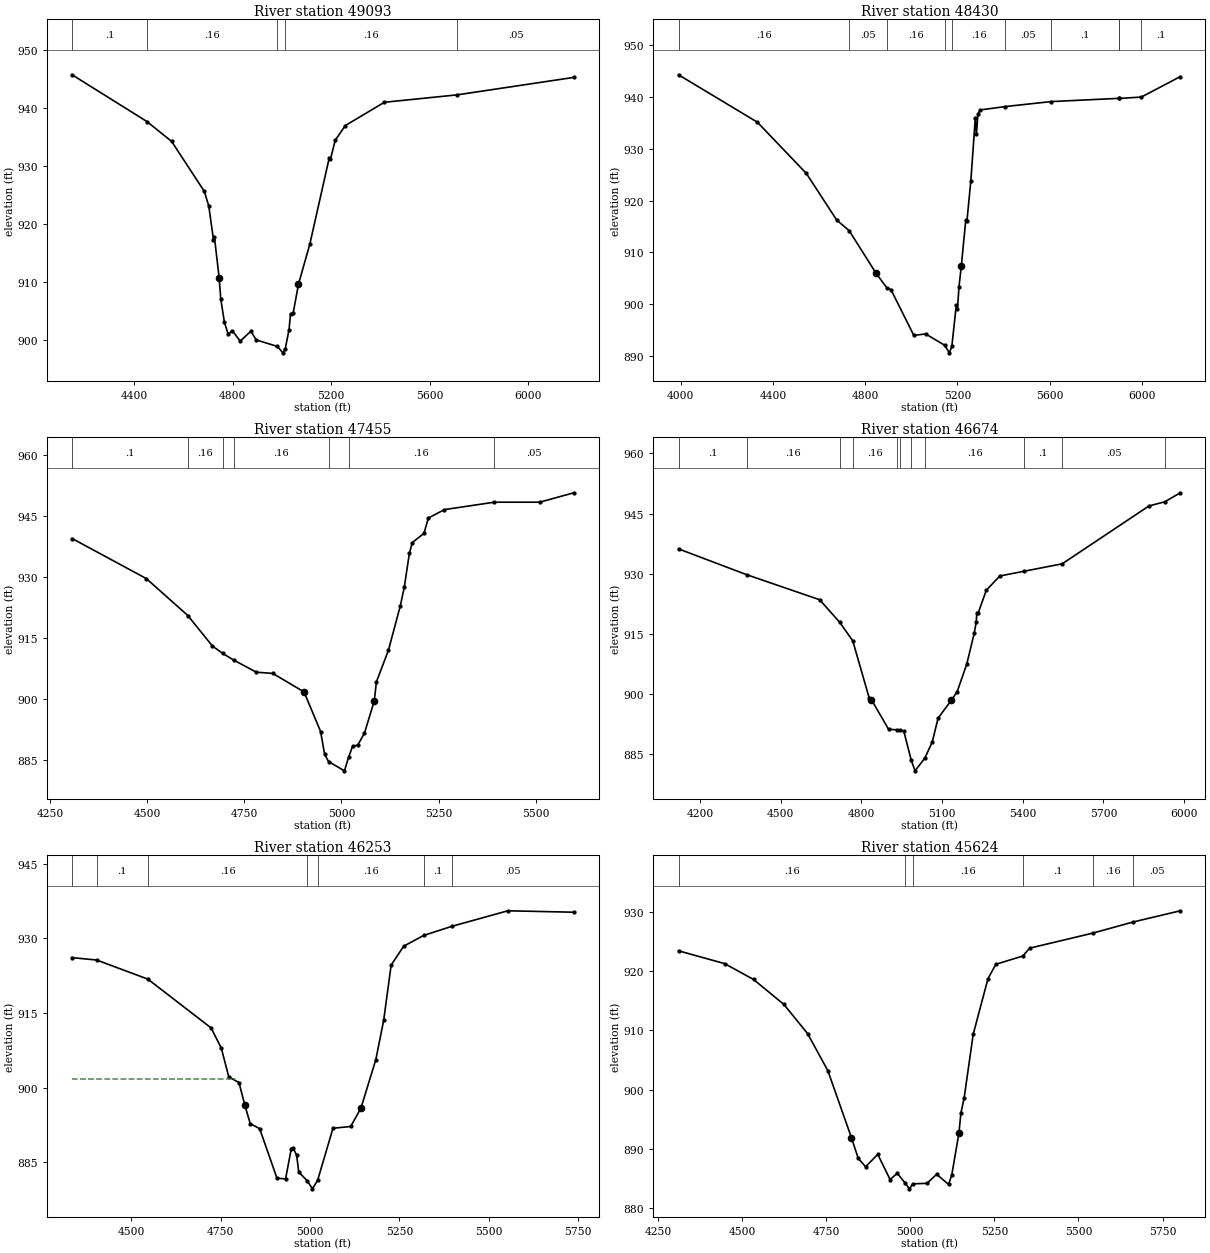
Type RM Length L Ch R = 1 ,49093   ,663,663,663
BEGIN DESCRIPTION:
CYPRESS CREEK 71.0
END DESCRIPTION:
XS GIS Cut Line= 4
      2961351.55     10109393.86      2961483.49     10108831.39
      2961295.99     10108352.23      2961698.62     10107498.37
#Sta/Elev= 30
  4148.3  945.75  4452.2  937.67  4552.5  934.23  4684.9  925.61  4703.1  923.08
  4722.2  917.25    4726  917.69    4745  910.71  4751.9  906.98  4766.5  902.99
  4781.8  900.92  4798.7  901.52  4830.7  899.73  4873.9  901.45  4895.7  899.94
  4981.2  898.82    5004  897.71  5013.5  898.41  5028.8  901.72  5034.9  904.48
  5045.7  904.61  5067.1  909.57  5112.9  916.45  5191.6  931.33    5197  931.17
  5216.1  934.42  5256.8  936.97  5415.8     941  5710.7  942.28  6184.6   945.3
#Mann= 5 ,-1 , 0
  4148.3      .1       0  4452.2     .16       0  4981.2     .07       0
  5013.5     .16       0  5710.7     .05       0
Bank Sta=4745,5067.1
XS Rating Curve= 0 ,0
Exp/Cntr=0.3,0.1

Type RM Length L Ch R = 1 ,48430   ,975,975,975
BEGIN DESCRIPTION:
CYPRESS CREEK 70.0
END DESCRIPTION:
XS GIS Cut Line= 4
      2961559.86     10109359.19      2962059.88     10108886.95
      2961872.38     10108136.95      2961914.04     10107421.71
#Sta/Elev= 30
  3990.1   944.3  4332.3  935.14  4544.7  925.25  4676.6  916.24  4730.2  914.22
  4846.1  906.05    4895  903.09  4911.8  902.81    5011  893.98  5062.6  894.26
    5145  892.07  5165.4  890.61    5176  891.86  5195.2  899.78  5200.4  899.03
  5206.9  903.28  5217.2  907.45  5236.5  916.27  5241.6  916.09  5258.4  923.83
  5277.7  935.89  5282.9  932.94  5289.3  936.78  5299.7  937.51  5407.1  938.16
  5605.4  939.12  5900.2  939.75  5903.3  939.73  5998.4     940  6167.4  943.95
#Mann= 10 ,-1 , 0
  3990.1     .16       0  4730.2     .05       0    4895     .16       0
    5145     .07       0    5176     .16       0  5407.1     .05       0
  5605.4      .1       0  5900.2     .05       0  5903.3     .16       0
  5998.4      .1       0
Bank Sta=4846.1,5217.2
XS Rating Curve= 0 ,0
Exp/Cntr=0.3,0.1

Type RM Length L Ch R = 1 ,47455   ,781,781,781
BEGIN DESCRIPTION:
CYPRESS CREEK 69.0
END DESCRIPTION:
XS GIS Cut Line= 4
      2962167.06     10109402.27      2962536.84     10109001.24
      2962984.76     10108897.08      2963156.32     10108668.33
#Sta/Elev= 30
  4306.8  939.46  4497.7  929.61  4604.7   920.5  4667.8  913.01  4694.7  911.15
  4723.8  909.47  4780.9  906.55  4823.2  906.25  4903.8  901.69  4946.4  891.93
  4956.7  886.31  4966.9  884.54  5007.7  882.26  5018.2  885.55  5028.5  888.28
  5041.9   888.6  5059.3  891.55  5084.5   899.5  5090.1   904.2  5120.9  911.93
  5151.7  922.96    5162  927.64  5174.9  935.85  5182.5  938.47  5212.4  940.73
  5223.6   944.5  5265.2  946.58  5393.5   948.4  5510.1   948.4  5598.1  950.72
#Mann= 7 ,-1 , 0
  4306.8      .1       0  4604.7     .16       0  4694.7      .1       0
  4723.8     .16       0  4966.9     .07       0  5018.2     .16       0
  5393.5     .05       0
Bank Sta=4903.8,5084.5
XS Rating Curve= 0 ,0
Exp/Cntr=0.3,0.1

Type RM Length L Ch R = 1 ,46674   ,421,421,421
BEGIN DESCRIPTION:
CYPRESS CREEK 68.0
END DESCRIPTION:
XS GIS Cut Line= 4
      2962333.69     10109584.57      2963036.84     10109699.16
      2963297.26     10109397.08      2963396.11     10108647.94
#Sta/Elev= 30
  4119.3   936.2  4373.6  929.75  4644.2  923.53  4718.7  917.92  4767.5  913.28
  4828.7  899.02  4837.1   898.6  4900.7  891.23  4933.3  891.09  4944.9  891.09
  4957.7  890.69  4985.2  883.48  4999.2  880.87  5035.7  884.05  5063.3  888.08
    5085  894.02  5134.4  898.46  5155.8  900.58  5191.5  907.44    5220  915.35
  5226.6  917.94  5229.5  920.33  5234.8  920.33  5264.2  925.88  5314.6  929.45
  5405.7  930.64  5546.7  932.48  5869.4   946.9  5928.6  947.95  5986.2  950.19
#Mann= 11 ,-1 , 0
  4119.3      .1       0  4373.6     .16       0  4718.7      .1       0
  4767.5     .16       0  4933.3      .1       0  4944.9     .16       0
  4985.2     .07       0  5035.7     .16       0  5405.7      .1       0
  5546.7     .05       0  5928.6      .1       0
Bank Sta=4837.1,5134.4
XS Rating Curve= 0 ,0
Exp/Cntr=0.3,0.1

Type RM Length L Ch R = 1 ,46253   ,629,629,629
BEGIN DESCRIPTION:
CYPRESS CREEK 67.0
END DESCRIPTION:
XS GIS Cut Line= 4
      2963069.82     10110413.14      2963377.12     10110053.76
      2963418.79     10109897.51      2963913.54     10109309.01
#Sta/Elev= 30
  4334.6  926.12  4403.3  925.64  4546.4  921.81  4723.4  912.01    4752  907.95
  4772.8  902.18  4801.4  901.03  4817.8  896.51  4832.7  892.81  4859.2  891.77
  4907.7  881.83  4931.7  881.68  4947.8  887.79    4953  887.84  4962.7  886.46
  4968.5  883.08  4992.8  881.26  5006.9  879.69  5021.4  881.41  5064.3  891.86
  5113.8  892.21  5142.4  895.88  5184.1  905.63  5206.1  913.53    5227  924.62
  5262.1  928.42  5318.1  930.58  5396.4   932.4  5553.4  935.53    5738  935.24
#Mann= 7 ,-1 , 0
  4334.6     .16       0  4403.3      .1       0  4546.4     .16       0
  4992.8     .07       0  5021.4     .16       0  5318.1      .1       0
  5396.4     .05       0
#XS Ineff= 2 , 0
         4790.78  901.73
Permanent Ineff=
       T       T
Bank Sta=4817.8,5142.4
XS Rating Curve= 0 ,0
Exp/Cntr=0.3,0.1

Type RM Length L Ch R = 1 ,45624   ,574,574,574
BEGIN DESCRIPTION:
CYPRESS CREEK 66.0
END DESCRIPTION:
XS GIS Cut Line= 4
      2963236.47     10110501.68      2963783.37     10110449.59
      2964059.41     10110001.68       2964100.9     10109586.86
#Sta/Elev= 30
  4310.5  923.39  4447.6  921.23  4533.5  918.56  4623.9  914.35  4694.2  909.44
  4754.5  903.19  4824.8  891.88  4844.9  888.41  4866.8  886.98    4903  889.07
  4939.7  884.83    4961  885.89  4984.2  884.25  4997.4  883.26  5007.2   884.1
  5049.7  884.19  5078.2  885.72  5113.6     884  5123.1  885.59  5144.4  892.62
  5150.3  896.05  5159.8  898.52  5186.9  909.32  5230.9  918.71  5254.4  921.12
  5334.2  922.51  5354.9  923.84  5543.1  926.38  5662.4  928.25  5802.9  930.14
#Mann= 6 ,-1 , 0
  4310.5     .16       0  4984.2     .07       0  5007.2     .16       0
  5334.2      .1       0  5543.1     .16       0  5662.4     .05       0
Bank Sta=4824.8,5144.4
XS Rating Curve= 0 ,0
Exp/Cntr=0.3,0.1

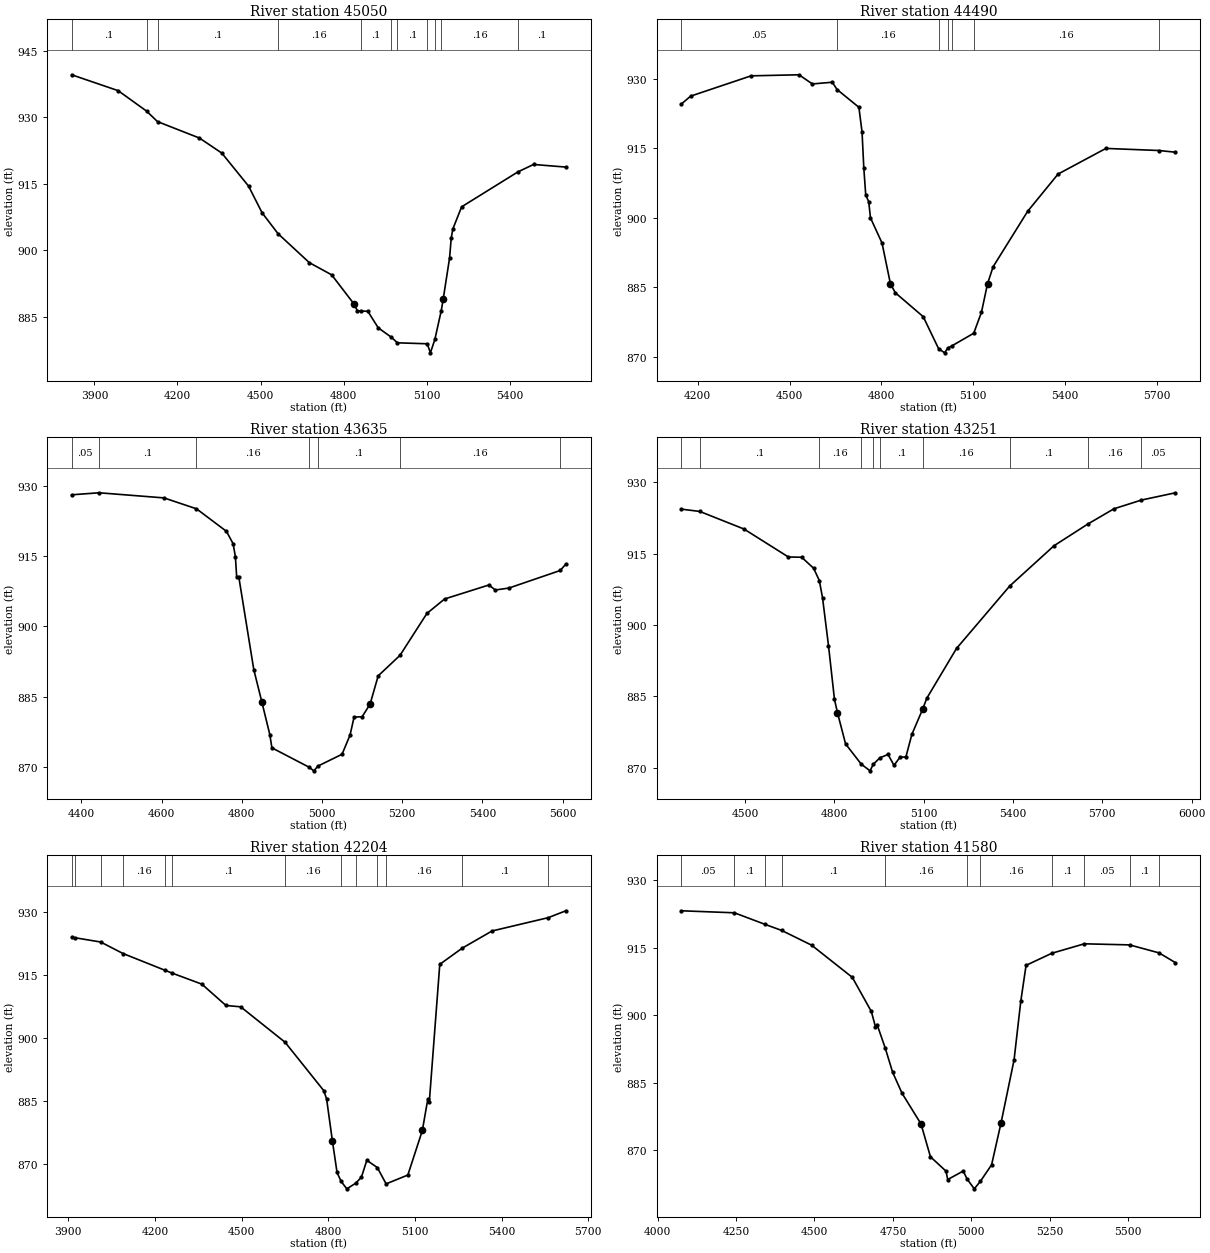
Type RM Length L Ch R = 1 ,45050   ,560,560,560
BEGIN DESCRIPTION:
CYPRESS CREEK 65.0
END DESCRIPTION:
XS GIS Cut Line= 3
      2963654.91      10111739.5      2964378.86     10110468.69
      2964358.12     10110147.21
#Sta/Elev= 30
  3817.9  939.57  3985.7  935.99  4088.4  931.38  4127.8  929.02  4279.4  925.31
  4360.1  921.92  4456.6  914.49  4505.6  908.46  4563.3  903.75  4676.2  897.23
  4756.7  894.49  4837.3  887.93  4849.9  886.36  4861.5  886.34  4887.4  886.27
  4924.9  882.55    4972  880.44  4994.2  879.17    5102  878.95  5113.4  876.91
  5129.5  879.94  5152.5  886.41  5159.6  889.02  5182.6  898.29  5188.5  902.74
  5194.3   904.8    5226  909.81  5429.5  917.69  5485.8  919.36  5602.6  918.77
#Mann= 11 ,-1 , 0
  3817.9      .1       0  4088.4     .05       0  4127.8      .1       0
  4563.3     .16       0  4861.5      .1       0    4972     .16       0
  4994.2      .1       0    5102     .07       0  5129.5      .1       0
  5152.5     .16       0  5429.5      .1       0
Bank Sta=4837.3,5159.6
XS Rating Curve= 0 ,0
Exp/Cntr=0.3,0.1

Type RM Length L Ch R = 1 ,44490   ,855,855,855
BEGIN DESCRIPTION:
CYPRESS CREEK 64.0
END DESCRIPTION:
XS GIS Cut Line= 4
      2965415.35     10111328.09      2964759.07     10110963.48
      2964748.65     10110692.65      2964494.07     10110157.52
#Sta/Elev= 30
  4145.9  924.55  4176.7  926.28    4374  930.66  4530.7  930.89  4574.2  928.91
  4639.4  929.28  4655.1   927.7  4726.3  923.87  4736.6  918.51  4742.3  910.81
  4748.6  904.95  4758.3  903.49  4764.1     900  4801.8  894.57  4829.3  885.76
  4845.3  883.82  4936.4  878.66  4986.5  871.77  5006.2  870.85  5016.5  871.88
  5029.4  872.33  5101.4  875.08  5126.6  879.59  5146.6  885.79  5164.7  889.43
  5277.8  901.43  5376.9  909.45  5533.2  914.99    5706  914.54  5760.3  914.17
#Mann= 7 ,-1 , 0
  4145.9     .05       0  4655.1     .16       0  4986.5     .07       0
  5016.5     .16       0  5029.4      .1       0  5101.4     .16       0
    5706      .1       0
Bank Sta=4829.3,5146.6
XS Rating Curve= 0 ,0
Exp/Cntr=0.3,0.1

Type RM Length L Ch R = 1 ,43635   ,384,384,384
BEGIN DESCRIPTION:
CYPRESS CREEK 63.0
END DESCRIPTION:
XS GIS Cut Line= 4
      2965597.59     10110333.27      2965227.82     10110145.77
       2964779.9      10110161.4      2964452.66     10109989.99
#Sta/Elev= 30
  4375.8  928.02    4444  928.45  4605.8  927.36  4686.9  925.04  4761.7  920.24
  4778.3   917.6    4784  914.84  4787.2  910.46  4792.6  910.46  4829.8  890.81
  4849.8  883.94  4869.8  876.95    4875  874.13  4967.6  870.01  4979.6  869.23
  4989.9  870.25  5049.9  872.76  5069.9  876.85  5079.9  880.69  5099.9  880.74
  5119.9  883.46    5140  889.46  5194.4  893.83  5261.5  902.75  5305.6  905.83
    5416  908.81  5432.1  907.74    5466  908.16  5593.9   911.9    5608  913.27
#Mann= 7 ,-1 , 0
  4375.8     .05       0    4444      .1       0  4686.9     .16       0
  4967.6     .07       0  4989.9      .1       0  5194.4     .16       0
  5593.9      .1       0
Bank Sta=4849.8,5119.9
XS Rating Curve= 0 ,0
Exp/Cntr=0.3,0.1

Type RM Length L Ch R = 1 ,43251   ,1047,1047,1047
BEGIN DESCRIPTION:
CYPRESS CREEK 62.0
END DESCRIPTION:
XS GIS Cut Line= 4
      2965535.09     10110072.83      2965321.57     10109781.19
      2964503.86     10109770.77      2964223.05     10109380.77
#Sta/Elev= 30
  4285.7  924.39  4348.1   923.9  4496.5   920.2  4645.5  914.32  4690.2  914.26
  4730.3  911.95  4749.5  909.36  4760.3  905.72  4780.3  895.68  4800.3  884.38
  4810.3  881.58  4837.7  874.97  4890.3  870.72    4920  869.31  4930.3  870.66
  4952.9  872.05  4980.3  872.76  5000.3  870.47  5020.3  872.16  5040.3  872.25
  5060.3  876.98  5097.2  882.38  5110.3  884.57  5210.3  895.07  5388.7  908.19
  5537.7  916.68  5651.8  921.27    5739  924.46  5830.9  926.29  5945.5  927.83
#Mann= 10 ,-1 , 0
  4285.7     .16       0  4348.1      .1       0  4749.5     .16       0
  4890.3     .07       0  4930.3     .16       0  4952.9      .1       0
  5097.2     .16       0  5388.7      .1       0  5651.8     .16       0
  5830.9     .05       0
Bank Sta=4810.3,5097.2
XS Rating Curve= 0 ,0
Exp/Cntr=0.3,0.1

Type RM Length L Ch R = 1 ,42204   ,624,624,624
BEGIN DESCRIPTION:
CYPRESS CREEK 61.0
END DESCRIPTION:
XS GIS Cut Line= 3
      2965634.07     10109999.94      2965347.61     10109400.98
      2965248.65     10108359.31
#Sta/Elev= 30
  3912.2  923.91  3922.3  923.84  4012.5  922.81  4089.8  920.08    4235   916.1
  4260.8   915.4  4362.5  912.81  4446.1  907.74    4497  907.42  4650.6  899.01
  4784.3  887.54  4794.4  885.56  4814.5  875.56  4830.5   868.1  4844.6  865.96
  4864.4  864.19  4894.8  865.51  4914.9  866.95  4933.6  870.97    4970  869.24
  5000.4  865.37  5075.6  867.47  5125.8  878.05  5144.8  885.55  5149.8  884.77
  5186.1  917.51  5263.7  921.35  5366.9  925.43  5561.2  928.59  5622.5  930.23
#Mann= 13 ,-1 , 0
  3912.2     .05       0  3922.3     .16       0  4012.5      .1       0
  4089.8     .16       0    4235     .05       0  4260.8      .1       0
  4650.6     .16       0  4844.6     .07       0  4894.8     .16       0
    4970      .1       0  5000.4     .16       0  5263.7      .1       0
  5561.2     .05       0
Bank Sta=4814.5,5125.8
XS Rating Curve= 0 ,0
Exp/Cntr=0.3,0.1

Type RM Length L Ch R = 1 ,41580   ,534,534,534
BEGIN DESCRIPTION:
CYPRESS CREEK 60.0
END DESCRIPTION:
XS GIS Cut Line= 3
      2965691.36      10110083.3      2965738.23     10109479.11
        2966082.     10108572.82
#Sta/Elev= 30
  4075.2  923.26  4244.7  922.81    4343  920.22  4395.2  918.89  4490.7  915.61
  4620.5  908.45  4681.2  900.85  4694.1  897.51  4699.5  897.95  4725.5  892.71
  4749.1  887.32  4779.2  882.64  4839.5  875.83  4869.6  868.52  4919.2  865.33
  4924.6  863.46  4974.2  865.35  4986.4  863.56  5009.4  861.39  5029.1  863.09
  5064.6  866.75  5094.7  876.08  5136.2   890.1  5157.5  903.09  5174.4  911.12
  5256.6  913.81  5360.1  915.91  5504.3  915.67  5598.4  913.89  5650.5  911.72
#Mann= 11 ,-1 , 0
  4075.2     .05       0  4244.7      .1       0    4343     .05       0
  4395.2      .1       0  4725.5     .16       0  4986.4     .07       0
  5029.1     .16       0  5256.6      .1       0  5360.1     .05       0
  5504.3      .1       0  5598.4     .05       0
Bank Sta=4839.5,5094.7
XS Rating Curve= 0 ,0
Exp/Cntr=0.3,0.1

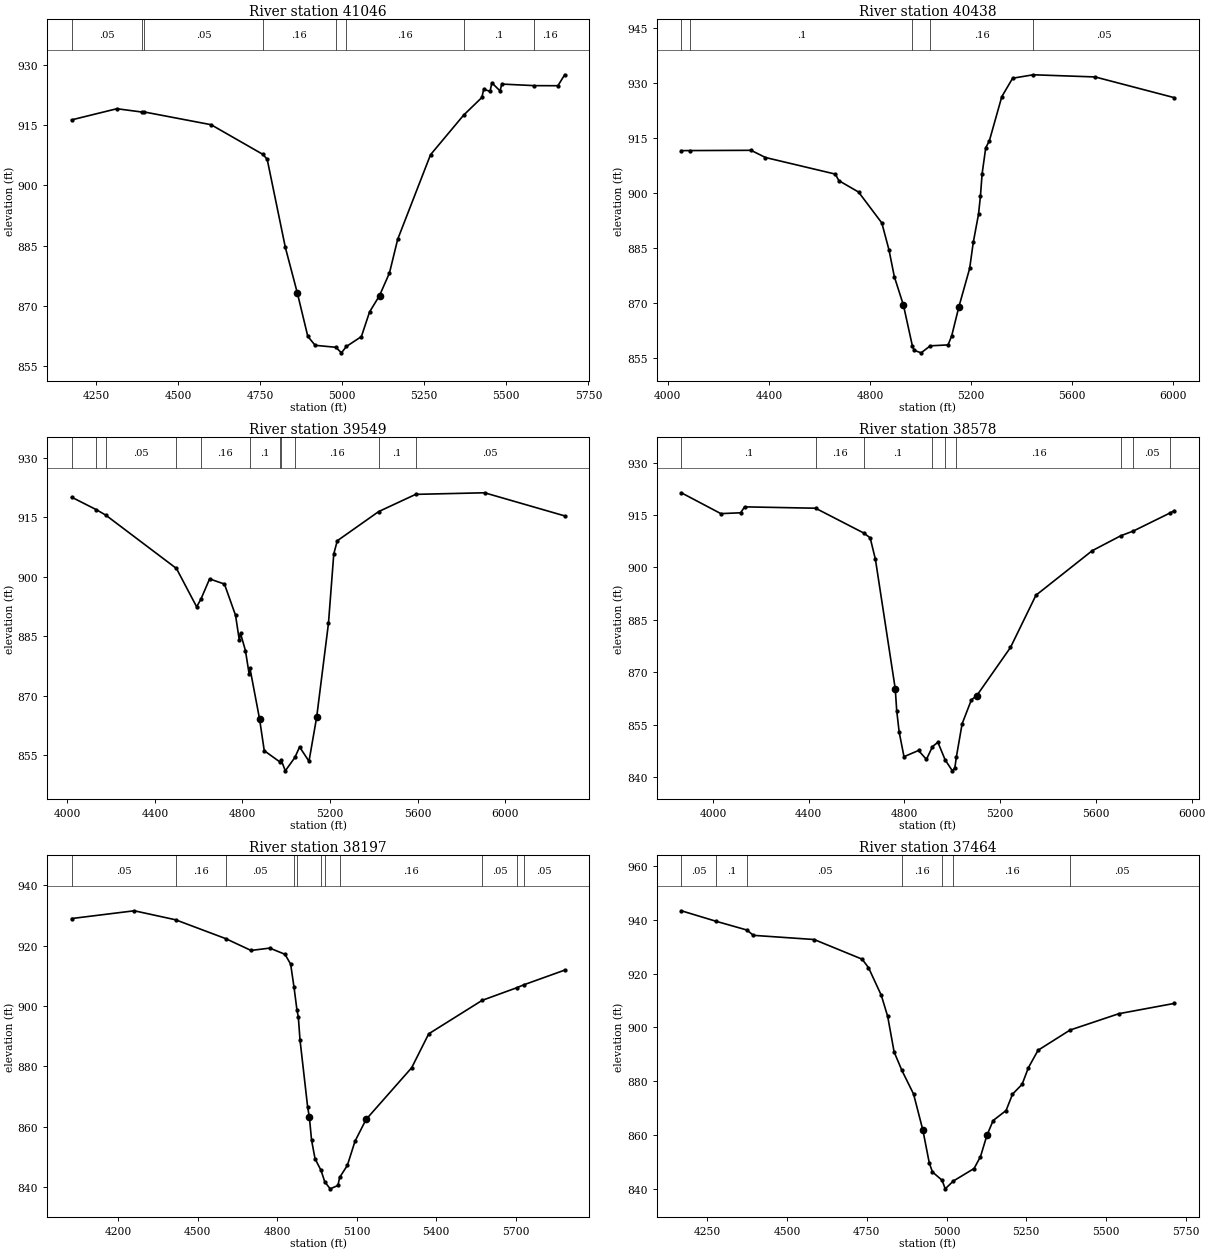
Type RM Length L Ch R = 1 ,41046   ,608,608,608
BEGIN DESCRIPTION:
CYPRESS CREEK 59.0
END DESCRIPTION:
XS GIS Cut Line= 2
      2966035.09     10110187.48      2966561.16     10108781.16
#Sta/Elev= 30
    4176  916.29  4313.8  919.06  4388.9  918.25  4397.4  918.25  4600.6  915.09
  4758.5  907.71  4771.6  906.49  4826.9  884.58  4863.3  873.28  4895.3  862.46
  4917.7  860.24  4980.8  859.75  4997.7  858.37  5012.8  859.95  5058.5  862.41
  5083.4  868.54  5113.7   872.6    5144  878.23    5169  886.59    5269  907.62
    5370  917.48  5425.5  921.86  5430.9  923.88  5450.5  923.39  5455.8  925.51
  5480.8  923.48  5486.1  925.19  5585.3   924.8  5657.1  924.78  5677.5   927.5
#Mann= 8 ,-1 , 0
    4176     .05       0  4388.9      .1       0  4397.4     .05       0
  4758.5     .16       0  4980.8     .07       0  5012.8     .16       0
    5370      .1       0  5585.3     .16       0
Bank Sta=4863.3,5113.7
XS Rating Curve= 0 ,0
Exp/Cntr=0.3,0.1

Type RM Length L Ch R = 1 ,40438   ,889,889,889
BEGIN DESCRIPTION:
CYPRESS CREEK 58.0
END DESCRIPTION:
XS GIS Cut Line= 3
      2966102.84     10110317.63      2967165.32     10109395.77
      2967691.39     10109255.14
#Sta/Elev= 30
  4053.6  911.57  4089.8  911.59  4329.5  911.66  4386.5   909.7  4662.9  905.18
  4677.1  903.39    4755  900.29  4847.1  891.86  4875.6  884.47  4896.5  877.24
  4932.6  869.47  4967.7  858.46  4974.6  857.18  5002.6  856.48  5038.9  858.39
  5109.2  858.64  5123.4  861.06  5151.9  868.99  5194.7  879.49  5208.9  886.55
  5229.8  894.27  5237.4  899.24    5244  905.27  5258.3  912.37  5272.5  914.22
  5321.9  926.28  5364.7   931.3  5446.5  932.24  5691.2  931.65  6004.8     926
#Mann= 5 ,-1 , 0
  4053.6     .05       0  4089.8      .1       0  4967.7     .07       0
  5038.9     .16       0  5446.5     .05       0
Bank Sta=4932.6,5151.9
XS Rating Curve= 0 ,0
Exp/Cntr=0.3,0.1

Type RM Length L Ch R = 1 ,39549   ,971,971,971
BEGIN DESCRIPTION:
CYPRESS CREEK 57.0
END DESCRIPTION:
XS GIS Cut Line= 4
      2965884.07     10110791.61      2966618.44     10110437.44
      2967076.78     10110619.73        2967945.     10110250.61
#Sta/Elev= 30
  4019.8  920.09  4132.8  916.93  4175.4  915.57  4498.6  902.09  4590.9  892.41
  4610.5  894.37    4650  899.46  4717.8  898.16  4768.6  890.26  4785.6  884.04
  4791.2  885.69  4813.8  881.36  4830.9  875.34  4834.2  876.95  4878.2  864.12
  4899.7  856.09    4971  853.26  4977.2  853.72  4995.8  851.01  5039.6  854.38
  5061.1  857.04    5104  853.42  5139.1  864.54    5193  888.25  5217.3  905.79
  5233.3  909.09  5422.2  916.45  5591.3   920.8  5906.1   921.2  6271.8  915.37
#Mann= 11 ,-1 , 0
  4019.8     .05       0  4132.8      .1       0  4175.4     .05       0
  4498.6      .1       0  4610.5     .16       0  4834.2      .1       0
    4971     .16       0  4977.2     .07       0  5039.6     .16       0
  5422.2      .1       0  5591.3     .05       0
Bank Sta=4878.2,5139.1
XS Rating Curve= 0 ,0
Exp/Cntr=0.3,0.1

Type RM Length L Ch R = 1 ,38578   ,381,381,381
BEGIN DESCRIPTION:
CYPRESS CREEK 56.0
END DESCRIPTION:
XS GIS Cut Line= 4
      2965623.67     10111833.26      2966363.23     10111447.86
      2966894.48     10111364.52      2967326.48     10110828.43
#Sta/Elev= 30
  3867.5  921.36  4032.6  915.39  4115.3  915.63  4131.8  917.33  4428.3  916.94
  4630.4  909.81  4656.5  908.46  4678.5   902.3  4761.4  865.22  4767.5  858.96
  4777.6  852.91  4797.9  845.78  4858.6  847.56  4891.7     845    4917  848.68
  4939.6  849.91  4969.9  844.87  5000.1  841.73  5010.4  842.57    5017  845.79
  5040.8   855.2  5079.6  862.07  5101.5  863.22  5242.9  877.06  5349.3  892.02
  5584.4  904.77  5703.5  909.04  5756.7  910.42  5907.5   915.5  5927.7  916.24
#Mann= 9 ,-1 , 0
  3867.5      .1       0  4428.3     .16       0  4630.4      .1       0
    4917     .16       0  4969.9     .07       0    5017     .16       0
  5703.5      .1       0  5756.7     .05       0  5907.5      .1       0
Bank Sta=4761.4,5101.5
XS Rating Curve= 0 ,0
Exp/Cntr=0.3,0.1

Type RM Length L Ch R = 1 ,38197   ,733,733,733
BEGIN DESCRIPTION:
CYPRESS CREEK 55.0
END DESCRIPTION:
XS GIS Cut Line= 3
      2966644.48      10112630.1      2966644.48     10111963.48
      2967372.34     10111017.26
#Sta/Elev= 30
  4024.2  928.93  4260.6   931.5  4416.3  928.52  4605.6  922.28  4701.2  918.36
  4771.8  919.14  4829.3  917.09  4850.7  913.82  4863.5  906.11  4874.4  898.69
  4879.7  896.29    4886  888.72    4915  866.37  4921.3  863.22  4929.5  855.59
  4942.8  849.35  4965.4  845.51  4979.4  841.73  4999.9  839.41  5029.2  840.53
  5035.5  843.18  5064.5  847.15  5093.6  855.18  5135.2  862.38  5307.4  879.52
  5371.7  890.75  5573.5  901.84  5704.5  906.03    5731     907  5884.6  911.84
#Mann= 11 ,-1 , 0
  4024.2     .05       0  4416.3     .16       0  4605.6     .05       0
  4863.5      .1       0  4874.4     .05       0  4965.4     .16       0
  4979.4     .07       0  5035.5     .16       0  5573.5     .05       0
  5704.5      .1       0    5731     .05       0
Bank Sta=4921.3,5135.2
XS Rating Curve= 0 ,0
Exp/Cntr=0.3,0.1

Type RM Length L Ch R = 1 ,37464   ,811,811,811
BEGIN DESCRIPTION:
CYPRESS CREEK 54.0
END DESCRIPTION:
XS GIS Cut Line= 2
       2967467.4     10112718.69      2967587.13     10111177.83
#Sta/Elev= 30
  4168.6  943.33  4276.3  939.47  4374.5  936.17  4394.2  934.21  4584.8  932.66
  4735.3  925.36  4755.3  922.22  4795.4  911.95  4815.5  904.09  4835.6  890.91
  4860.1  884.04  4896.5  875.31  4925.8  861.86  4945.9  849.67  4955.9  846.34
    4986  843.27  4995.8  840.09  5021.3  842.99  5086.3  847.64  5106.4  852.06
  5126.4  859.91    5146  865.45  5186.6  869.17  5206.7  875.23  5236.8   878.9
  5256.8  885.13  5286.9  891.55  5387.1  899.04  5540.2  905.12  5714.1  908.94
#Mann= 7 ,-1 , 0
  4168.6     .05       0  4276.3      .1       0  4374.5     .05       0
  4860.1     .16       0    4986     .07       0  5021.3     .16       0
  5387.1     .05       0
Bank Sta=4925.8,5126.4
XS Rating Curve= 0 ,0
Exp/Cntr=0.3,0.1