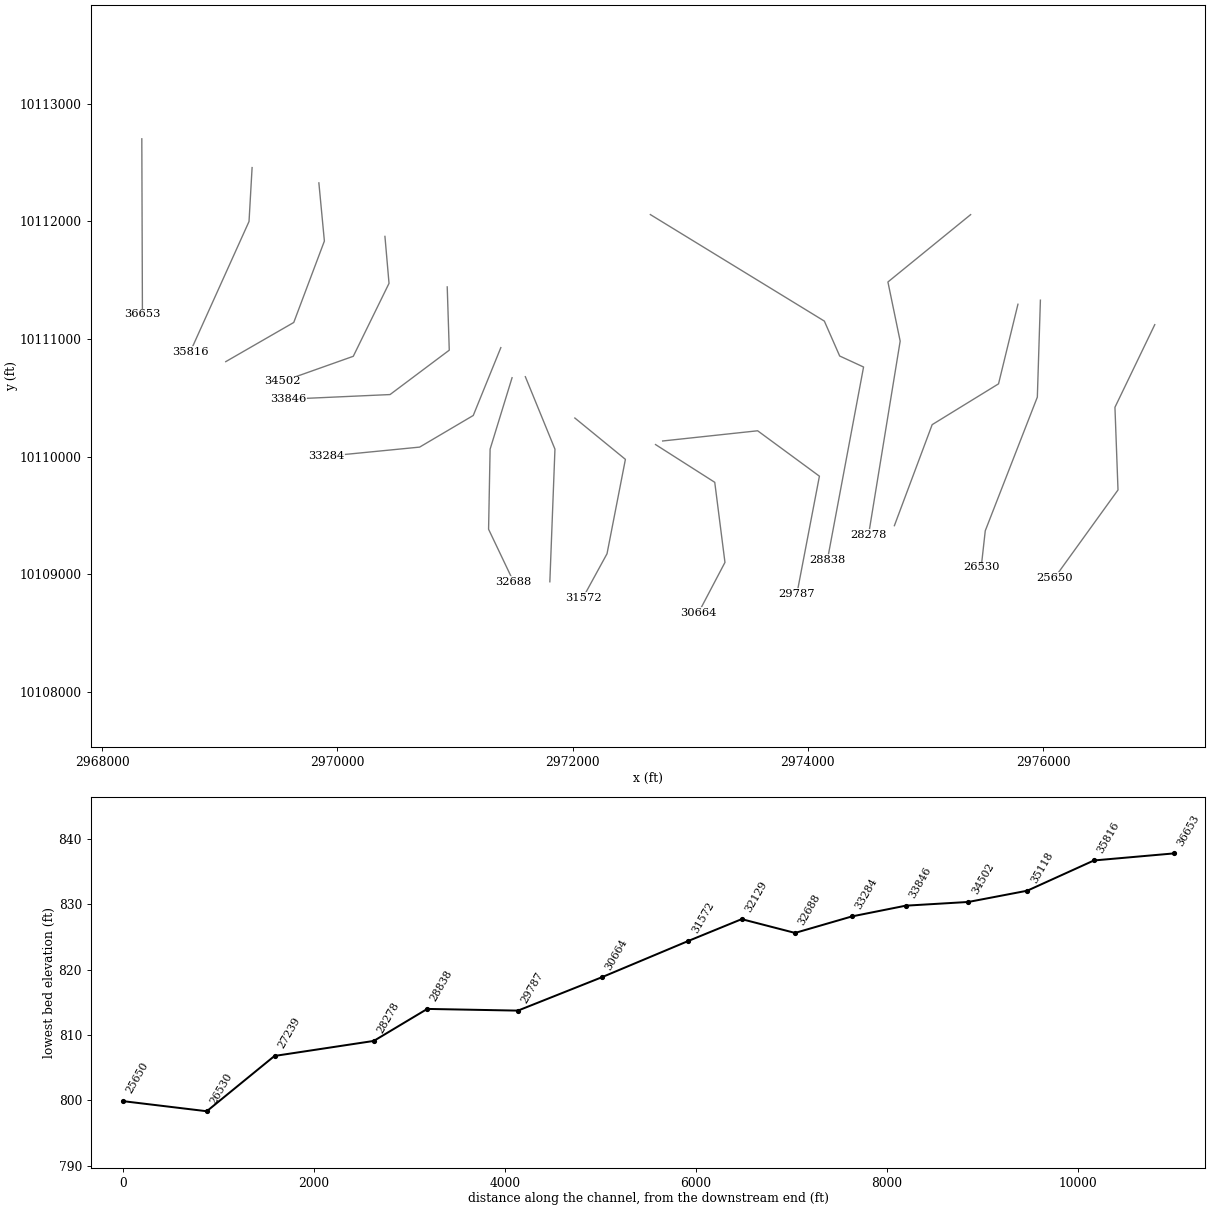
HEC-RAS study CYPRESS CREEK.prj: CYPRESS CREEK Base Level Engineering

--- CYPRESS CREEK.g01 (geometry) --- (continued)

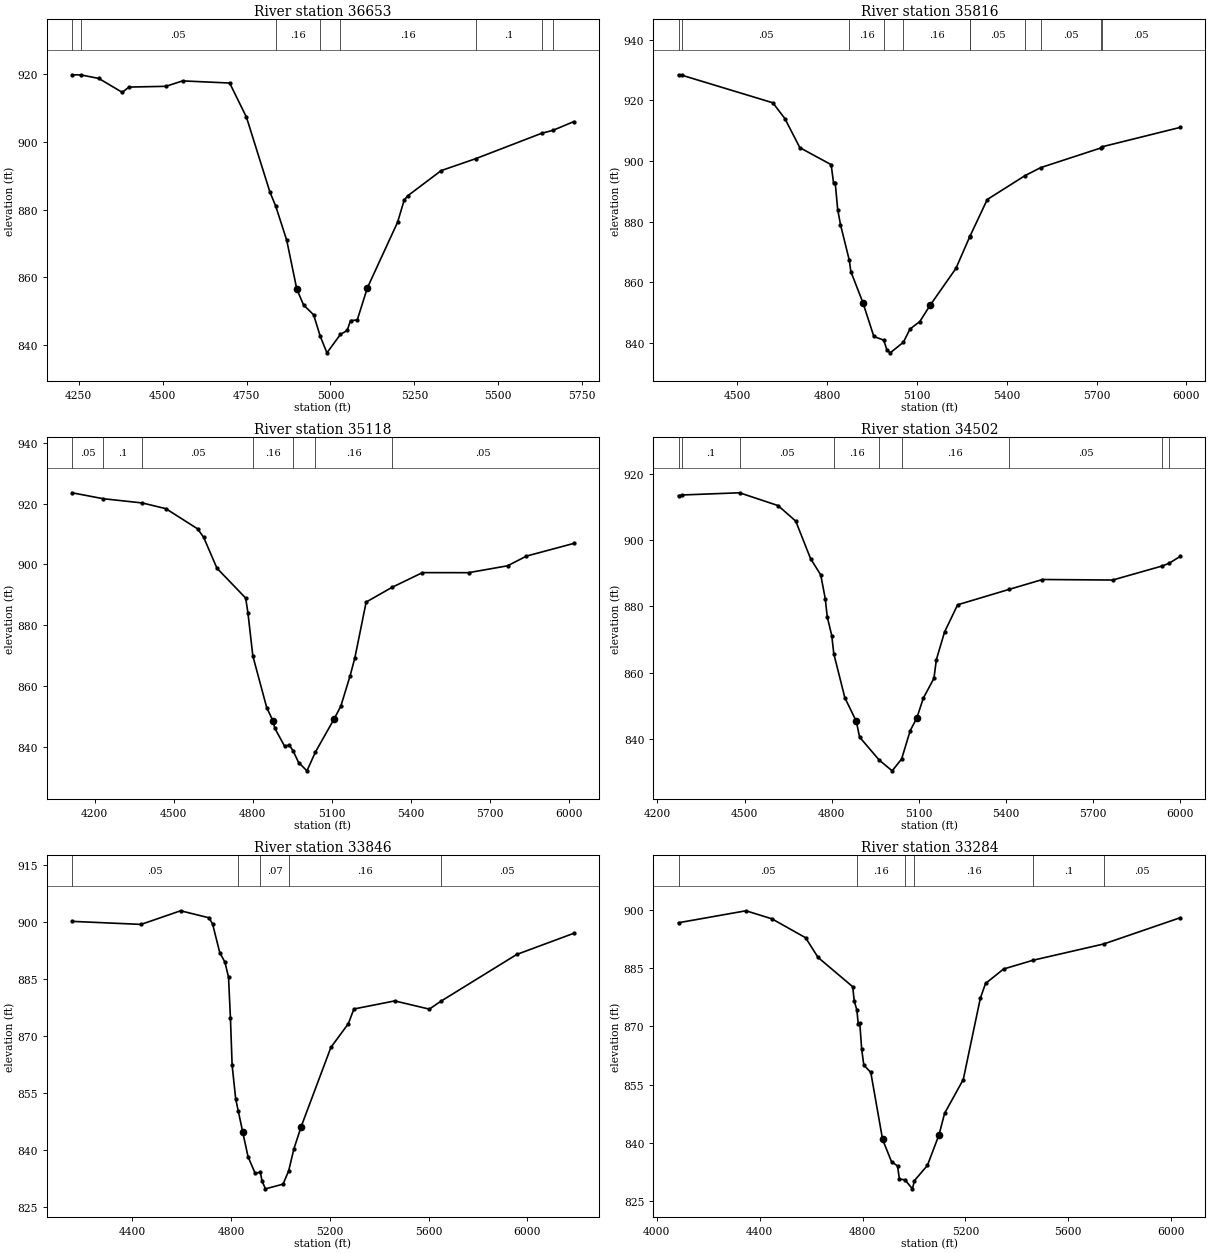
Type RM Length L Ch R = 1 ,36653   ,837,837,837
BEGIN DESCRIPTION:
CYPRESS CREEK 53.0
END DESCRIPTION:
XS GIS Cut Line= 2
      2968337.19     10112703.12       2968342.4     10111208.52
#Sta/Elev= 30
  4230.4   919.7  4256.7  919.66  4309.8  918.63  4379.8  914.53  4399.8  916.08
  4509.8   916.3  4559.8   917.9  4699.8  917.27  4749.8  907.21  4819.8  885.13
  4837.2  880.96  4869.8  870.94  4899.8  856.57  4919.8  851.93  4949.8  849.01
  4969.8  842.64  4989.5  837.81  5029.8  843.24  5049.8   844.4  5059.8  847.31
  5079.8  847.48  5109.8  856.91  5199.8  876.24  5219.8  882.84  5229.8  884.03
  5329.8  891.48  5432.9     895  5629.5  902.49  5662.5  903.33    5725  905.92
#Mann= 8 ,-1 , 0
  4230.4      .1       0  4256.7     .05       0  4837.2     .16       0
  4969.8     .07       0  5029.8     .16       0  5432.9      .1       0
  5629.5     .05       0  5662.5      .1       0
Bank Sta=4899.8,5109.8
XS Rating Curve= 0 ,0
Exp/Cntr=0.3,0.1

Type RM Length L Ch R = 1 ,35816   ,698,698,698
BEGIN DESCRIPTION:
CYPRESS CREEK 52.0
END DESCRIPTION:
XS GIS Cut Line= 3
      2969274.69     10112458.23      2969248.65     10111999.94
      2968748.64     10110890.54
#Sta/Elev= 30
  4303.6  928.42  4314.6  928.28  4618.6  919.18  4658.7  913.99  4708.7  904.39
  4813.3  898.78  4821.4  892.73  4826.8  892.87  4835.2  883.95  4844.5  879.01
    4874  867.22  4879.1  863.53  4919.4  853.28  4955.9  842.13  4988.8  840.92
  4999.8  837.62  5010.5  836.73  5054.6  840.22  5076.6  844.57  5109.5  847.06
  5144.1  852.45  5230.1  864.58  5275.5  874.87  5277.3  875.26  5334.7  887.29
  5459.7   895.1  5512.9   897.8  5713.3  904.26  5717.9  904.67  5979.5  911.08
#Mann= 11 ,-1 , 0
  4303.6      .1       0  4314.6     .05       0    4874     .16       0
  4988.8     .07       0  5054.6     .16       0  5275.5     .12       0
  5277.3     .05       0  5459.7     .16       0  5512.9     .05       0
  5713.3      .1       0  5717.9     .05       0
Bank Sta=4919.4,5144.1
XS Rating Curve= 0 ,0
Exp/Cntr=0.3,0.1

Type RM Length L Ch R = 1 ,35118   ,616,616,616
BEGIN DESCRIPTION:
CYPRESS CREEK 51.0
END DESCRIPTION:
XS GIS Cut Line= 4
       2969842.4     10112328.05      2969889.28     10111833.27
      2969628.86     10111140.57      2969050.71     10110807.22
#Sta/Elev= 30
  4114.2  923.55  4232.3   921.6  4380.1  920.21  4470.1  918.33  4590.6  911.69
  4613.6   908.9  4664.1  898.74    4773  888.93  4781.6   884.1  4800.3  869.87
  4853.1  852.84  4877.8  848.34  4883.3  846.18  4920.5  840.25  4938.4  840.56
  4952.6  838.75    4974  834.83  5005.7   832.1    5038  838.32  5109.1  849.23
    5134  853.32  5169.6  863.41  5187.6  869.31  5230.3  887.61  5328.3  892.44
    5444  897.29  5619.1  897.27  5767.2  899.54  5838.8  902.73  6018.6   906.9
#Mann= 7 ,-1 , 0
  4114.2     .05       0  4232.3      .1       0  4380.1     .05       0
  4800.3     .16       0  4952.6     .07       0    5038     .16       0
  5328.3     .05       0
Bank Sta=4877.8,5109.1
XS Rating Curve= 0 ,0
Exp/Cntr=0.3,0.1

Type RM Length L Ch R = 1 ,34502   ,656,656,656
BEGIN DESCRIPTION:
CYPRESS CREEK 50.0
END DESCRIPTION:
XS GIS Cut Line= 4
      2970404.03     10111872.81      2970438.75     10111473.46
      2970134.93     10110852.81      2969535.95     10110640.12
#Sta/Elev= 30
  4272.5  913.45  4285.8  913.63  4482.5  914.29  4615.1  910.43    4676  905.74
    4727  894.43  4762.1  889.49  4777.6  882.33  4784.4  876.88  4800.1  871.14
    4807  865.72  4845.1  852.43  4884.6  845.32  4895.7  840.58  4963.2  833.64
    5008  830.38  5040.5  833.96  5070.2  842.54  5092.7   846.3  5115.2  852.31
  5151.8  858.31  5160.2  863.96  5188.3  872.27  5233.3  880.49  5410.8  885.14
  5525.5  888.12  5767.1  887.96  5936.8  892.18  5960.4  892.97    6000  895.11
#Mann= 9 ,-1 , 0
  4272.5     .05       0  4285.8      .1       0  4482.5     .05       0
    4807     .16       0  4963.2     .07       0  5040.5     .16       0
  5410.8     .05       0  5936.8     .16       0  5960.4     .05       0
Bank Sta=4884.6,5092.7
XS Rating Curve= 0 ,0
Exp/Cntr=0.3,0.1

Type RM Length L Ch R = 1 ,33846   ,562,562,562
BEGIN DESCRIPTION:
CYPRESS CREEK 49.0
END DESCRIPTION:
XS GIS Cut Line= 4
      2970933.55     10111443.09      2970950.91     10110904.89
      2970447.43     10110527.28      2969583.73     10110488.22
#Sta/Elev= 30
  4155.7  900.08  4435.2  899.28  4595.3  902.86  4710.2  901.02  4724.8   899.4
    4754  891.84  4774.8  889.37  4789.4  885.43  4797.2  874.58    4804  862.26
  4818.5   853.4  4829.2  850.15  4847.2  844.63  4868.5  838.24  4897.2  833.91
  4918.5  834.18  4924.8  831.88  4939.1  829.81  5010.2  831.04  5033.1  834.56
    5054  840.28  5083.1  846.06    5204  866.97  5274.8  873.21  5297.2  877.06
  5462.6  879.18  5602.8  877.02    5648  879.03  5956.8  891.39  6188.1  896.95
#Mann= 5 ,-1 , 0
  4155.7     .05       0  4829.2     .16       0  4918.5     .07       0
  5033.1     .16       0    5648     .05       0
Bank Sta=4847.2,5083.1
XS Rating Curve= 0 ,0
Exp/Cntr=0.3,0.1

Type RM Length L Ch R = 1 ,33284   ,596,596,596
BEGIN DESCRIPTION:
CYPRESS CREEK 48.0
END DESCRIPTION:
XS GIS Cut Line= 4
      2971389.27     10110926.58       2971154.9     10110349.33
      2970699.17     10110080.24      2969904.87     10110002.11
#Sta/Elev= 30
  4084.8  896.72  4346.9   899.8  4447.6  897.73  4578.8  892.85    4627  887.79
  4761.7  880.24  4767.8  876.54    4778  874.23  4783.4  870.54  4789.2  870.94
  4796.6   864.2  4804.9  860.05  4832.1  858.16  4877.9   840.9  4912.7  835.15
  4935.9  834.07  4943.4  830.68  4964.8   830.5  4993.8  828.17  5001.9   830.3
  5052.1   834.2  5097.5  842.14    5119  847.63  5191.4  856.31  5257.9  877.27
    5278  881.07  5348.3   884.8  5463.4  887.07  5737.7  891.25  6035.2  898.02
#Mann= 6 ,-1 , 0
  4084.8     .05       0    4778     .16       0  4964.8     .07       0
  5001.9     .16       0  5463.4      .1       0  5737.7     .05       0
Bank Sta=4877.9,5097.5
XS Rating Curve= 0 ,0
Exp/Cntr=0.3,0.1

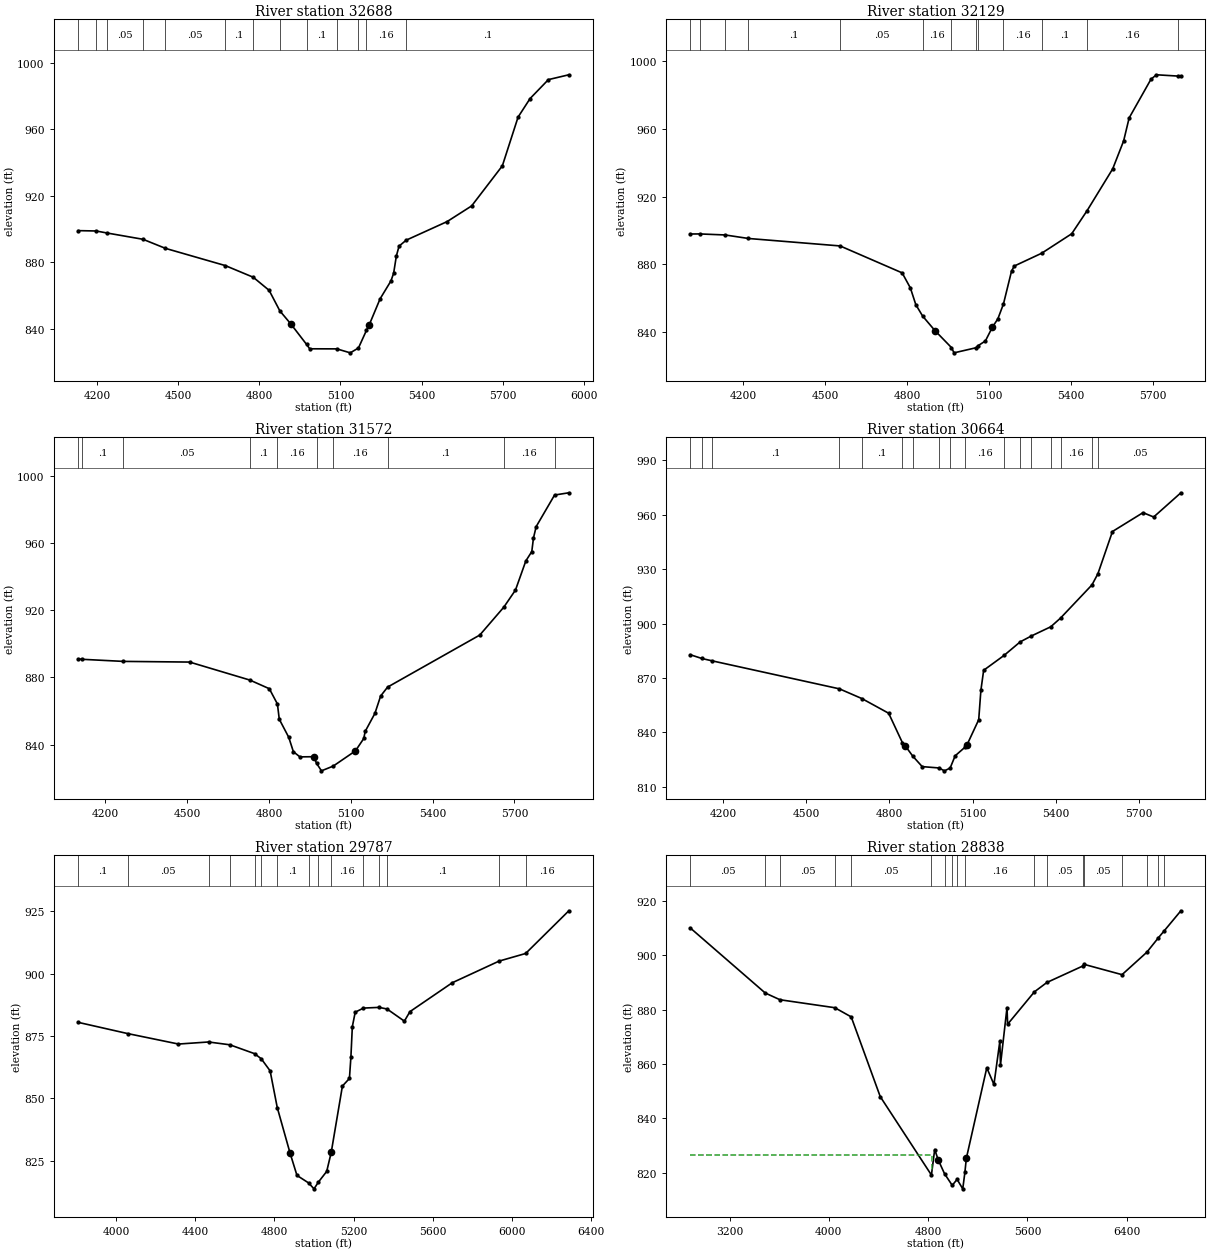
Type RM Length L Ch R = 1 ,32688   ,559,559,559
BEGIN DESCRIPTION:
CYPRESS CREEK 47.0
END DESCRIPTION:
XS GIS Cut Line= 4
      2971484.76     10110670.51      2971298.13     10110062.87
      2971285.11     10109381.45       2971497.8     10108934.36
#Sta/Elev= 30
  4131.7  899.06  4197.5  898.85  4237.1  897.65  4370.5  893.86  4453.5  888.41
  4674.3  878.08  4777.8  871.06  4836.5  863.19  4876.3   850.8  4916.5  843.04
  4974.7  830.74  4986.5  828.07  5086.6  828.02  5136.3  825.64  5166.6  828.56
  5196.1  839.12  5206.6  842.54  5246.6  858.11  5286.6  868.83  5296.6  873.47
  5306.6   883.8  5316.6  889.75    5343  893.33  5493.9  904.47  5584.8  913.91
  5698.3     938  5756.4  967.28  5800.7  978.41  5868.4  989.79    5944   992.7
#Mann= 13 ,-1 , 0
  4131.7     .05       0  4197.5      .1       0  4237.1     .05       0
  4370.5      .1       0  4453.5     .05       0  4674.3      .1       0
  4777.8     .05       0  4876.3     .16       0  4974.7      .1       0
  5086.6     .07       0  5166.6      .1       0  5196.1     .16       0
    5343      .1       0
Bank Sta=4916.5,5206.6
XS Rating Curve= 0 ,0
Exp/Cntr=0.3,0.1

Type RM Length L Ch R = 1 ,32129   ,557,557,557
BEGIN DESCRIPTION:
CYPRESS CREEK 46.0
END DESCRIPTION:
XS GIS Cut Line= 3
      2971597.62     10110679.17      2971849.34     10110062.87
      2971805.94     10108934.43
#Sta/Elev= 30
  4006.5  897.92  4040.1  897.97  4133.5  897.36    4219  895.28  4554.2  890.88
  4781.4  874.97  4811.5  866.07  4831.5  856.15  4856.5  849.43  4901.5  840.86
  4961.6  830.89  4971.3  827.75  5051.6  830.74  5058.4  831.88    5086  834.75
  5111.7  842.92  5131.7  847.84  5152.2  856.64  5181.7  876.01  5191.7  879.01
  5291.9  886.56  5401.9  898.07  5458.1  911.68    5552  936.41    5592  952.93
  5612.1  966.47  5692.1  989.35  5712.1  991.95  5789.1   991.2  5801.5  991.16
#Mann= 13 ,-1 , 0
  4006.5     .05       0  4040.1      .1       0  4133.5     .05       0
    4219      .1       0  4554.2     .05       0  4856.5     .16       0
  4961.6     .07       0  5051.6     .16       0  5058.4     .05       0
  5152.2     .16       0  5291.9      .1       0  5458.1     .16       0
  5789.1      .1       0
Bank Sta=4901.5,5111.7
XS Rating Curve= 0 ,0
Exp/Cntr=0.3,0.1

Type RM Length L Ch R = 1 ,31572   ,908,908,908
BEGIN DESCRIPTION:
CYPRESS CREEK 45.0
END DESCRIPTION:
XS GIS Cut Line= 4
      2972018.59     10110327.65       2972448.3     10109976.07
      2972292.05     10109173.12      2972088.06     10108799.85
#Sta/Elev= 30
  4100.8  890.98  4115.3  890.75  4265.4  889.51  4508.7  889.11  4729.7   878.4
    4801  873.26  4830.7  864.18  4837.5  855.11  4872.3  844.35  4889.2   835.8
  4913.1  832.73    4964  832.82  4974.2  828.91  4992.2  824.42  5035.3  827.24
  5116.8  836.28  5147.4  843.67  5152.5  847.86  5188.2  858.58  5209.2  868.91
  5234.7  874.22  5572.8  905.17    5661  921.78  5703.7  931.94  5741.7  949.28
  5763.5  954.82  5769.6  962.86  5779.6  969.68    5847  988.44  5899.4  989.79
#Mann= 10 ,-1 , 0
  4100.8     .05       0  4115.3      .1       0  4265.4     .05       0
  4729.7      .1       0  4830.7     .16       0  4974.2     .07       0
  5035.3     .16       0  5234.7      .1       0    5661     .16       0
    5847      .1       0
Bank Sta=4964,5116.8
XS Rating Curve= 0 ,0
Exp/Cntr=0.3,0.1

Type RM Length L Ch R = 1 ,30664   ,877,877,877
BEGIN DESCRIPTION:
CYPRESS CREEK 44.0
END DESCRIPTION:
XS GIS Cut Line= 4
      2972704.36     10110101.95      2973207.85     10109780.76
      2973294.66     10109099.33      2973068.96     10108669.65
#Sta/Elev= 30
  4082.2  882.85  4123.5   880.8  4158.5  879.57    4620  864.05  4700.8   858.7
  4797.4  850.61  4846.8  834.43  4857.9  832.49  4884.5  826.93  4918.4  821.18
  4978.8  820.44  4998.8  818.85  5019.2   820.4  5037.3  827.13  5073.7  832.01
  5079.7  833.07  5122.3  847.04  5130.1  863.21  5140.1  874.29  5213.4  882.45
    5272  889.97    5312  893.19  5382.2  898.28  5417.4  903.07  5530.9  921.38
  5552.2  927.49  5604.8  950.81  5715.1  961.22  5753.5  958.81  5851.7  972.17
#Mann= 17 ,-1 , 0
  4082.2      .1       0  4123.5     .16       0  4158.5      .1       0
    4620     .05       0  4700.8      .1       0  4846.8     .05       0
  4884.5      .1       0  4978.8     .07       0  5019.2      .1       0
  5073.7     .16       0  5213.4     .05       0    5272      .1       0
    5312     .05       0  5382.2      .1       0  5417.4     .16       0
  5530.9      .1       0  5552.2     .05       0
Bank Sta=4857.9,5079.7
XS Rating Curve= 0 ,0
Exp/Cntr=0.3,0.1

Type RM Length L Ch R = 1 ,29787   ,949,949,949
BEGIN DESCRIPTION:
CYPRESS CREEK 43.0
END DESCRIPTION:
XS GIS Cut Line= 4
       2972765.1     10110132.31      2973572.43     10110219.12
      2974097.61     10109832.84      2973906.63     10108834.57
#Sta/Elev= 30
  3808.5  880.48  4057.2  876.01  4314.8   871.8  4466.8  872.63  4574.6   871.5
  4699.3  867.95  4733.2  865.91  4778.1  861.06  4814.2  846.35  4878.4  828.24
  4913.9  819.13  4972.5  816.13  5000.1  813.75  5022.6  816.48  5064.3  820.74
  5087.2  828.39  5143.7  854.96  5179.2     858  5186.6   866.5  5193.9  878.79
  5208.5  884.58  5250.3  886.22  5329.4   886.5  5369.4  885.85    5457  880.98
  5485.3   884.8  5699.1  896.37  5935.8  905.05  6070.3  908.11  6288.8  925.23
#Mann= 15 ,-1 , 0
  3808.5      .1       0  4057.2     .05       0  4466.8      .1       0
  4574.6     .05       0  4699.3      .1       0  4733.2     .05       0
  4814.2      .1       0  4972.5     .07       0  5022.6      .1       0
  5087.2     .16       0  5250.3      .1       0  5329.4     .05       0
  5369.4      .1       0  5935.8     .05       0  6070.3     .16       0
Bank Sta=4878.4,5087.2
XS Rating Curve= 0 ,0
Exp/Cntr=0.3,0.1

Type RM Length L Ch R = 1 ,28838   ,560,560,560
BEGIN DESCRIPTION:
CYPRESS CREEK 42.0
END DESCRIPTION:
XS GIS Cut Line= 5
      2972660.48     10112058.43      2974139.62      10111152.2
      2974269.83     10110855.32      2974472.96     10110761.57
      2974165.67     10109120.98
#Sta/Elev= 30
  2885.1  910.05    3488  886.13  3606.8  883.65  4048.4  880.72  4180.6  877.34
  4414.5  847.97  4826.9  819.09  4853.1  828.49    4882  824.64  4932.3  819.59
  4994.4   815.3  5033.7  817.49  5079.3  814.01  5096.6   820.1    5108  825.21
  5272.9  858.59  5330.6  852.45  5378.1  868.39  5383.2  859.64  5435.8  880.78
  5440.9  874.64  5656.6  886.57  5757.4  890.02  6051.4  896.18  6059.1  896.66
  6362.5  892.89  6562.3  901.15  6655.5  906.48  6698.7  908.83  6836.8  916.42
#Mann= 18 ,-1 , 0
  2885.1     .05       0    3488      .1       0  3606.8     .05       0
  4048.4      .1       0  4180.6     .05       0  4826.9     .16       0
  4932.3      .1       0  4994.4     .16       0  5033.7     .07       0
  5096.6     .16       0  5656.6      .1       0  5757.4     .05       0
  6051.4      .1       0  6059.1     .05       0  6362.5      .1       0
  6562.3     .05       0  6655.5      .1       0  6698.7     .05       0
#XS Ineff= 2 , 0
         4832.39  826.43
Permanent Ineff=
       T       T
Bank Sta=4882,5108
XS Rating Curve= 0 ,0
Exp/Cntr=0.3,0.1

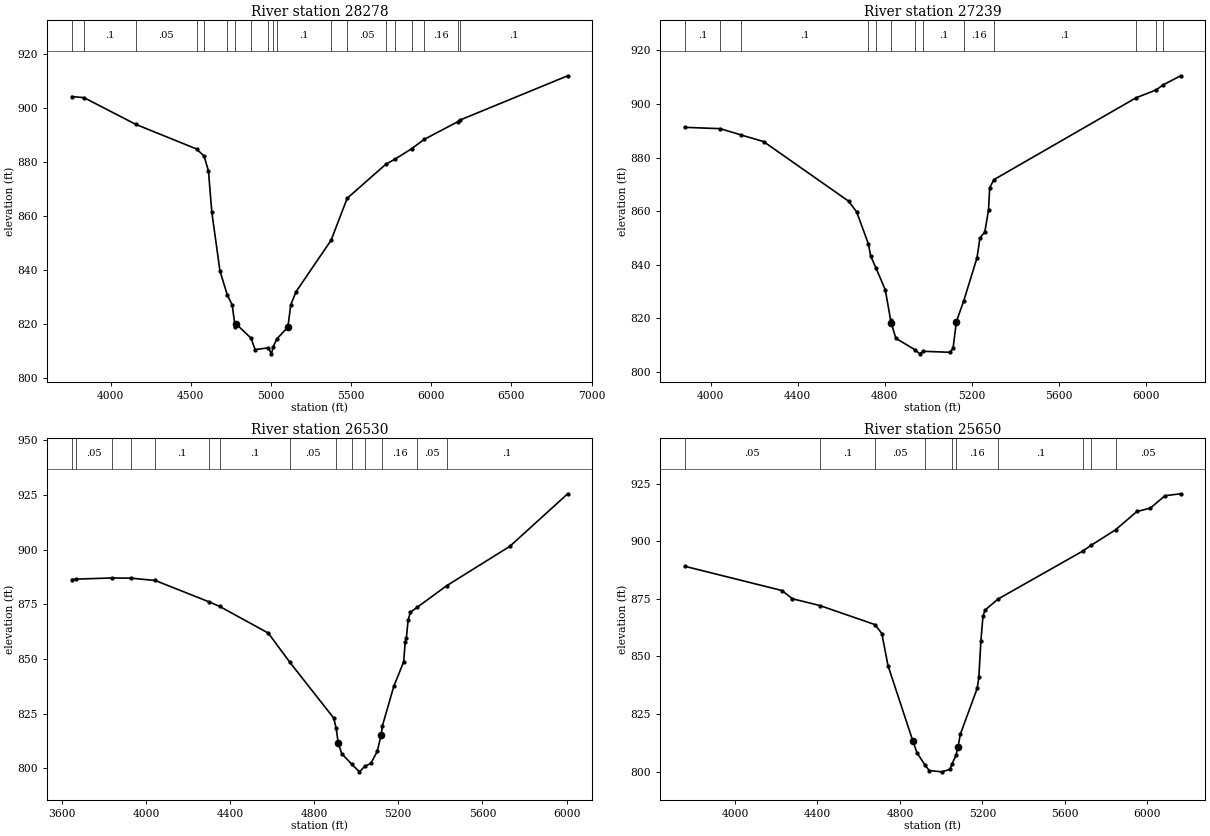
Type RM Length L Ch R = 1 ,28278   ,1039,1039,1039
BEGIN DESCRIPTION:
CYPRESS CREEK 41.0
END DESCRIPTION:
XS GIS Cut Line= 4
      2975383.08     10112057.99      2974679.99      10111485.1
      2974784.15     10110981.62      2974515.06     10109332.31
#Sta/Elev= 30
  3758.3  904.26  3834.2  903.87  4158.9  893.94  4536.2  884.88  4583.3  882.25
  4610.6  876.76  4631.4  861.55  4682.2  839.78  4727.8  830.92  4758.5  827.19
  4776.6   819.2  4782.6  820.18  4876.1  814.89  4901.5  810.68  4983.4  811.32
  5003.4  809.11  5013.8  811.68  5037.8  814.69  5105.7  818.98  5123.8  827.23
  5156.8   832.1  5375.3  851.13  5475.6  866.65  5716.2  879.22  5776.5  881.22
  5876.9  884.95  5955.1   888.4  6167.8  895.04  6179.9   895.6  6850.5  911.95
#Mann= 19 ,-1 , 0
  3758.3     .05       0  3834.2      .1       0  4158.9     .05       0
  4536.2      .1       0  4583.3     .16       0  4727.8      .1       0
  4776.6     .16       0  4876.1      .1       0  4983.4     .07       0
  5013.8     .16       0  5037.8      .1       0  5375.3     .16       0
  5475.6     .05       0  5716.2      .1       0  5776.5     .16       0
  5876.9      .1       0  5955.1     .16       0  6167.8     .05       0
  6179.9      .1       0
Bank Sta=4782.6,5105.7
XS Rating Curve= 0 ,0
Exp/Cntr=0.3,0.1

Type RM Length L Ch R = 1 ,27239   ,709,709,709
BEGIN DESCRIPTION:
CYPRESS CREEK 39.0
END DESCRIPTION:
XS GIS Cut Line= 4
      2975785.32     10111295.59      2975620.38     10110618.49
      2975056.14     10110271.27      2974734.95     10109411.84
#Sta/Elev= 30
  3881.4   891.3  4044.4   890.8  4138.8  888.49  4243.5  885.99  4634.2  863.74
  4670.9  859.75    4725  847.75  4734.8  843.38  4759.7  838.78  4802.3  830.72
  4826.9  819.36  4829.4  818.37  4850.7  812.62  4939.5  808.29  4960.6  806.81
  4976.2  807.76    5098  807.39  5113.4  808.82  5128.9  818.85  5162.5  826.58
  5223.5  842.63  5236.5   849.9  5259.5  852.37  5276.3  860.42  5281.6   868.8
  5301.5   871.8  5952.4  902.26  6044.9  905.23  6078.9  907.17  6158.3  910.53
#Mann= 13 ,-1 , 0
  3881.4      .1       0  4044.4     .05       0  4138.8      .1       0
    4725     .16       0  4759.7     .05       0  4826.9      .1       0
  4939.5     .07       0  4976.2      .1       0  5162.5     .16       0
  5301.5      .1       0  5952.4     .05       0  6044.9      .1       0
  6078.9     .05       0
Bank Sta=4829.4,5128.9
XS Rating Curve= 0 ,0
Exp/Cntr=0.3,0.1

Type RM Length L Ch R = 1 ,26530   ,880,880,880
BEGIN DESCRIPTION:
CYPRESS CREEK 38.0
END DESCRIPTION:
XS GIS Cut Line= 4
      2975976.28     10111330.27      2975950.24     10110505.64
      2975507.53     10109368.49      2975472.96     10109057.33
#Sta/Elev= 30
  3647.2  886.33    3668  886.51  3837.7  887.04  3929.2  886.95  4044.1  885.88
  4301.1  876.07  4350.9  873.99  4581.6  861.84  4684.4  848.44  4892.8  822.97
  4904.3  818.43  4914.3  811.64  4931.1  806.66  4978.6  801.85  5015.2  798.35
  5039.9  800.83  5069.8  802.24  5099.7  807.69  5118.2  815.08  5124.6  819.45
  5178.6  837.45  5225.5  848.68    5233  857.73  5238.4  859.54  5246.9  867.84
  5257.5  871.33  5288.7  873.54  5430.6  883.52  5730.9  901.54  6005.6  925.55
#Mann= 14 ,-1 , 0
  3647.2      .1       0    3668     .05       0  3837.7      .1       0
  3929.2     .05       0  4044.1      .1       0  4301.1     .05       0
  4350.9      .1       0  4684.4     .05       0  4904.3      .1       0
  4978.6     .07       0  5039.9      .1       0  5124.6     .16       0
  5288.7     .05       0  5430.6      .1       0
Bank Sta=4914.3,5118.2
XS Rating Curve= 0 ,0
Exp/Cntr=0.3,0.1

Type RM Length L Ch R = 1 ,25650   ,517,517,517
BEGIN DESCRIPTION:
CYPRESS CREEK 37.0
END DESCRIPTION:
XS GIS Cut Line= 4
      2976948.52     10111121.99      2976609.96     10110418.84
      2976636.01     10109715.71      2976097.82      10108969.2
#Sta/Elev= 30
  3756.5  889.16  4227.7  878.63  4278.5  875.05  4411.1  872.12  4678.8  863.83
  4712.1  859.95  4742.2     846  4862.2   813.4  4882.3  808.28  4922.3  802.72
  4942.3  800.47  5002.1   799.9  5042.4  800.95  5052.4  803.33  5071.8  807.04
  5082.4   810.9  5092.4  816.12  5174.7  836.17  5182.5  840.92  5192.5  856.88
  5202.5  867.39  5212.5  870.12  5275.8  874.94    5686  895.74  5728.2  898.34
  5845.2  904.97  5948.9  912.94  6013.9   914.4  6085.1   919.8  6160.8  920.63
#Mann= 10 ,-1 , 0
  3756.5     .05       0  4411.1      .1       0  4678.8     .05       0
  4922.3     .07       0  5052.4      .1       0  5071.8     .16       0
  5275.8      .1       0    5686     .05       0  5728.2      .1       0
  5845.2     .05       0
Bank Sta=4862.2,5082.4
XS Rating Curve= 0 ,0
Exp/Cntr=0.3,0.1