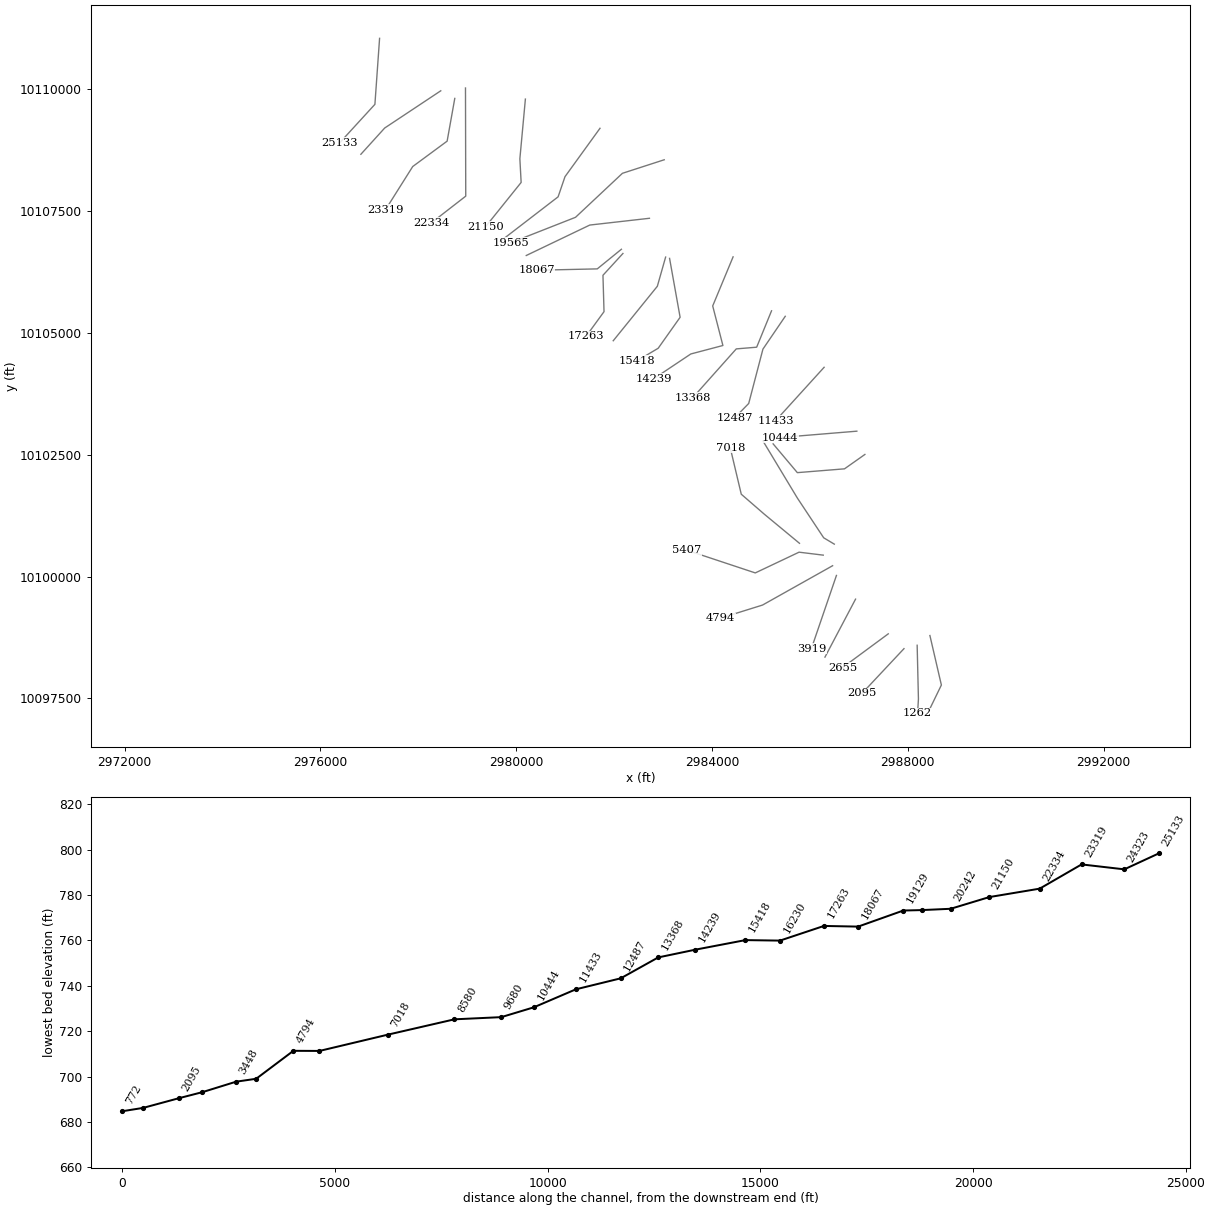
HEC-RAS study CYPRESS CREEK.prj: CYPRESS CREEK Base Level Engineering

--- CYPRESS CREEK.g01 (geometry) --- (continued)

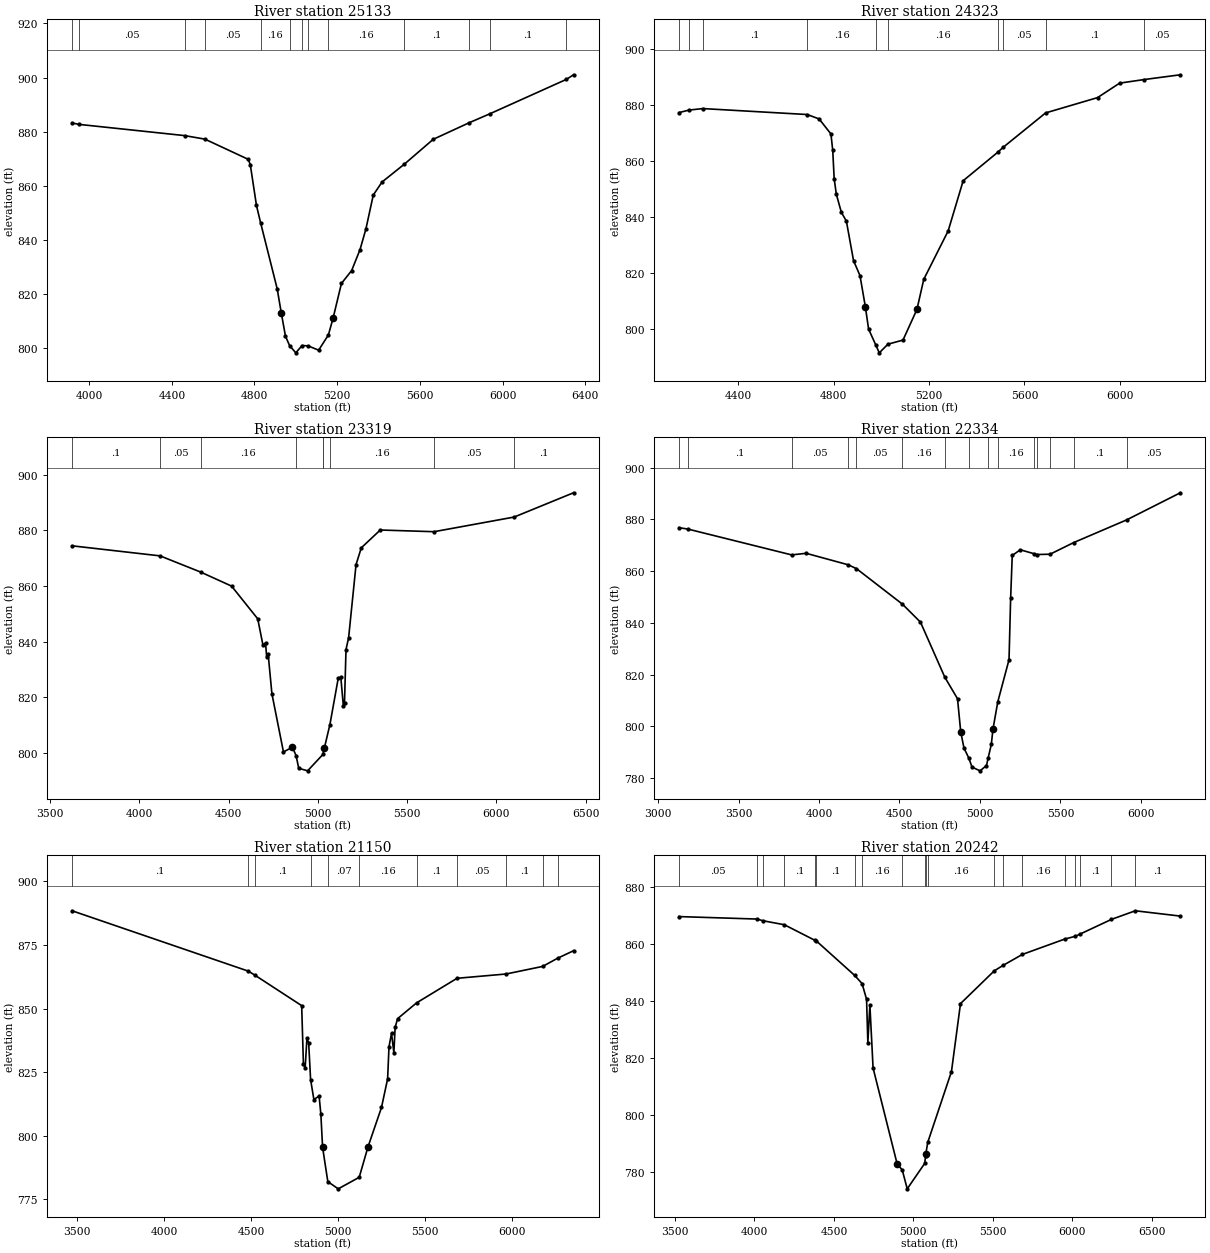
Type RM Length L Ch R = 1 ,25133   ,810,810,810
BEGIN DESCRIPTION:
CYPRESS CREEK 36.0
END DESCRIPTION:
XS GIS Cut Line= 3
      2977208.92     10111043.86      2977113.44     10109689.67
      2976393.23     10108900.04
#Sta/Elev= 30
  3917.3  883.22  3951.6   882.7  4462.1  878.56    4560  877.26  4769.5  869.81
  4779.6  867.88  4809.6  852.75  4829.5  846.39  4909.9  821.96  4929.9  812.93
    4950  804.45    4970  800.98  4999.9  798.32  5030.2  801.02  5058.6   800.9
  5110.4  799.31  5157.5  804.91  5180.6  811.22  5220.7  823.96  5270.1  828.71
  5310.6  836.44    5339  844.04  5374.8  856.62  5417.3  861.43  5525.7  868.05
  5664.6  877.18  5838.7  883.31  5939.2  886.63  6309.4  899.34  6343.6  901.03
#Mann= 13 ,-1 , 0
  3917.3      .1       0  3951.6     .05       0  4462.1      .1       0
    4560     .05       0  4829.5     .16       0    4970     .07       0
  5030.2     .16       0  5058.6      .1       0  5157.5     .16       0
  5525.7      .1       0  5838.7     .05       0  5939.2      .1       0
  6309.4     .05       0
Bank Sta=4929.9,5180.6
XS Rating Curve= 0 ,0
Exp/Cntr=0.3,0.1

Type RM Length L Ch R = 1 ,24323   ,1004,1004,1004
BEGIN DESCRIPTION:
CYPRESS CREEK 35.0
END DESCRIPTION:
XS GIS Cut Line= 3
      2978458.94     10109967.46      2977313.09     10109203.56
      2976826.96     10108665.34
#Sta/Elev= 30
  4151.2  877.24  4193.7  878.14  4251.8  878.68  4689.4  876.55  4739.2  874.97
  4788.7   869.6  4796.3  863.69  4802.3  853.55  4811.4  848.02  4832.4  841.55
  4853.4  838.44  4883.5  824.27  4910.5  818.93    4933  807.79  4946.6  799.79
  4976.6  794.13  4991.4   791.3  5027.7   794.4  5090.8  795.86  5149.3  806.84
  5177.9   817.6  5280.1   834.9  5343.2  852.88  5487.2  862.99  5510.2  864.78
  5688.6  877.12  5906.4   882.6  5999.1  887.78  6102.4  889.07  6253.6  890.77
#Mann= 10 ,-1 , 0
  4151.2      .1       0  4193.7     .05       0  4251.8      .1       0
  4689.4     .16       0  4976.6     .07       0  5027.7     .16       0
  5487.2      .1       0  5510.2     .05       0  5688.6      .1       0
  6102.4     .05       0
Bank Sta=4933,5149.3
XS Rating Curve= 0 ,0
Exp/Cntr=0.3,0.1

Type RM Length L Ch R = 1 ,23319   ,985,985,985
BEGIN DESCRIPTION:
CYPRESS CREEK 33.0
END DESCRIPTION:
XS GIS Cut Line= 4
      2978745.38     10109811.18      2978589.13     10108934.46
      2977886.01     10108413.63      2977330.63     10107528.49
#Sta/Elev= 30
  3622.2  874.46  4115.6  870.84  4343.3     865  4516.3  859.96  4662.9  848.18
  4692.2  838.71  4706.8  839.51    4713  834.31  4721.4   835.4  4742.3  821.22
    4807  800.27  4857.1  801.97  4877.9  798.96  4892.5   794.4  4942.4  793.47
  5028.2  799.38  5036.2  801.65  5067.3  810.09  5113.8  826.71  5128.4  827.24
    5143  816.63  5149.2  818.06  5157.6  837.13  5172.2  841.37  5213.9   867.7
  5243.2  873.73  5349.6  880.15  5650.9  879.54  6099.9  884.81  6432.7  893.55
#Mann= 9 ,-1 , 0
  3622.2      .1       0  4115.6     .05       0  4343.3     .16       0
  4877.9    .033       0  5028.2     .16       0  5028.2     .05       0
  5067.3     .16       0  5650.9     .05       0  6099.9      .1       0
Bank Sta=4857.1,5036.2
XS Rating Curve= 0 ,0
Exp/Cntr=0.3,0.1

Type RM Length L Ch R = 1 ,22334   ,1184,1184,1184
BEGIN DESCRIPTION:
CYPRESS CREEK 31.0
END DESCRIPTION:
XS GIS Cut Line= 3
      2978964.13     10110024.76      2978969.34     10107805.99
      2978262.23     10107254.86
#Sta/Elev= 30
  3129.5  876.79  3186.4  876.23  3829.8  866.26  3920.5  866.87  4180.5  862.45
  4232.5  860.96  4518.4  847.21  4630.5  840.25  4781.4     819  4860.5  810.66
  4880.5  797.86  4900.5  791.64    4931  787.67  4950.5  784.24  5000.3  782.79
  5040.5  784.83  5050.5  787.68  5070.5  793.02  5080.5  798.79  5110.6  809.45
  5180.5  825.75  5190.5  849.43  5200.5  866.03  5250.5  868.24  5334.3  866.74
  5351.3   866.4  5435.2  866.52  5581.6     871  5910.8  879.78  6244.8  890.27
#Mann= 15 ,-1 , 0
  3129.5     .05       0  3186.4      .1       0  3829.8     .05       0
  4180.5     .16       0  4232.5     .05       0  4518.4     .16       0
  4781.4     .05       0    4931     .07       0  5050.5      .1       0
  5110.6     .16       0  5334.3     .05       0  5351.3      .1       0
  5435.2     .05       0  5581.6      .1       0  5910.8     .05       0
Bank Sta=4880.5,5080.5
XS Rating Curve= 0 ,0
Exp/Cntr=0.3,0.1

Type RM Length L Ch R = 1 ,21150   ,908,908,908
BEGIN DESCRIPTION:
CYPRESS CREEK 30.0
END DESCRIPTION:
XS GIS Cut Line= 4
      2980188.09     10109797.33      2980075.24     10108573.35
      2980101.28     10108087.24      2979373.94     10107178.06
#Sta/Elev= 30
  3471.9  888.47  4484.5  864.72  4521.4  863.17  4790.8  851.15  4800.8  828.24
  4810.8   826.6  4820.9  838.25  4830.9  836.57  4842.1  822.05  4860.9  814.22
    4891  815.57    4901  808.39    4911  795.39    4941   781.9  5000.9  779.08
  5121.3  783.62  5171.4  795.52  5249.2  811.08  5284.4  822.34  5292.4  835.01
  5306.8  840.25  5320.4  832.64  5327.6  842.66  5342.1  846.05  5450.9  852.25
  5683.2  861.91    5965   863.6  6175.4  866.59  6260.7   869.8  6352.2  872.75
#Mann= 11 ,-1 , 0
  3471.9      .1       0  4484.5     .05       0  4521.4      .1       0
  4842.1     .16       0    4941     .07       0  5121.3     .16       0
  5450.9      .1       0  5683.2     .05       0    5965      .1       0
  6175.4     .05       0  6260.7      .1       0
Bank Sta=4911,5171.4
XS Rating Curve= 0 ,0
Exp/Cntr=0.3,0.1

Type RM Length L Ch R = 1 ,20242   ,677,677,677
BEGIN DESCRIPTION:
CYPRESS CREEK 29.0
END DESCRIPTION:
XS GIS Cut Line= 4
      2981712.39     10109198.35      2980997.12     10108205.29
      2980856.49      10107792.1       2979674.1     10106878.23
#Sta/Elev= 30
  3524.9  869.66  4016.6  868.79  4052.8  868.21  4188.4  866.79  4379.8  861.34
  4388.9  861.13  4629.8  849.02  4677.4   846.1  4705.6  840.57  4713.7  825.35
  4726.5  838.51  4746.6  816.42  4898.3  782.61    4930  780.59  4961.4  773.92
  5071.5  782.87    5077  785.57  5077.9  786.01  5090.5  790.26  5239.7  815.15
  5296.5  839.05  5509.4   850.6  5564.6   852.5  5685.4  856.34  5951.2  861.73
  6019.7  862.74  6047.7  863.48  6246.1  868.67  6396.3   871.7  6679.6  869.83
#Mann= 20 ,-1 , 0
  3524.9     .05       0  4016.6      .1       0  4052.8     .05       0
  4188.4      .1       0  4379.8     .16       0  4388.9      .1       0
  4629.8     .05       0  4677.4     .16       0    4930     .07       0
  5071.5     .16       0    5077     .12       0  5090.5     .16       0
  5509.4     .05       0  5564.6     .16       0  5685.4     .16       0
  5951.2      .1       0  6019.7     .05       0  6047.7      .1       0
  6246.1     .05       0  6396.3      .1       0
Bank Sta=4898.3,5077.9
XS Rating Curve= 0 ,0
Exp/Cntr=0.3,0.1

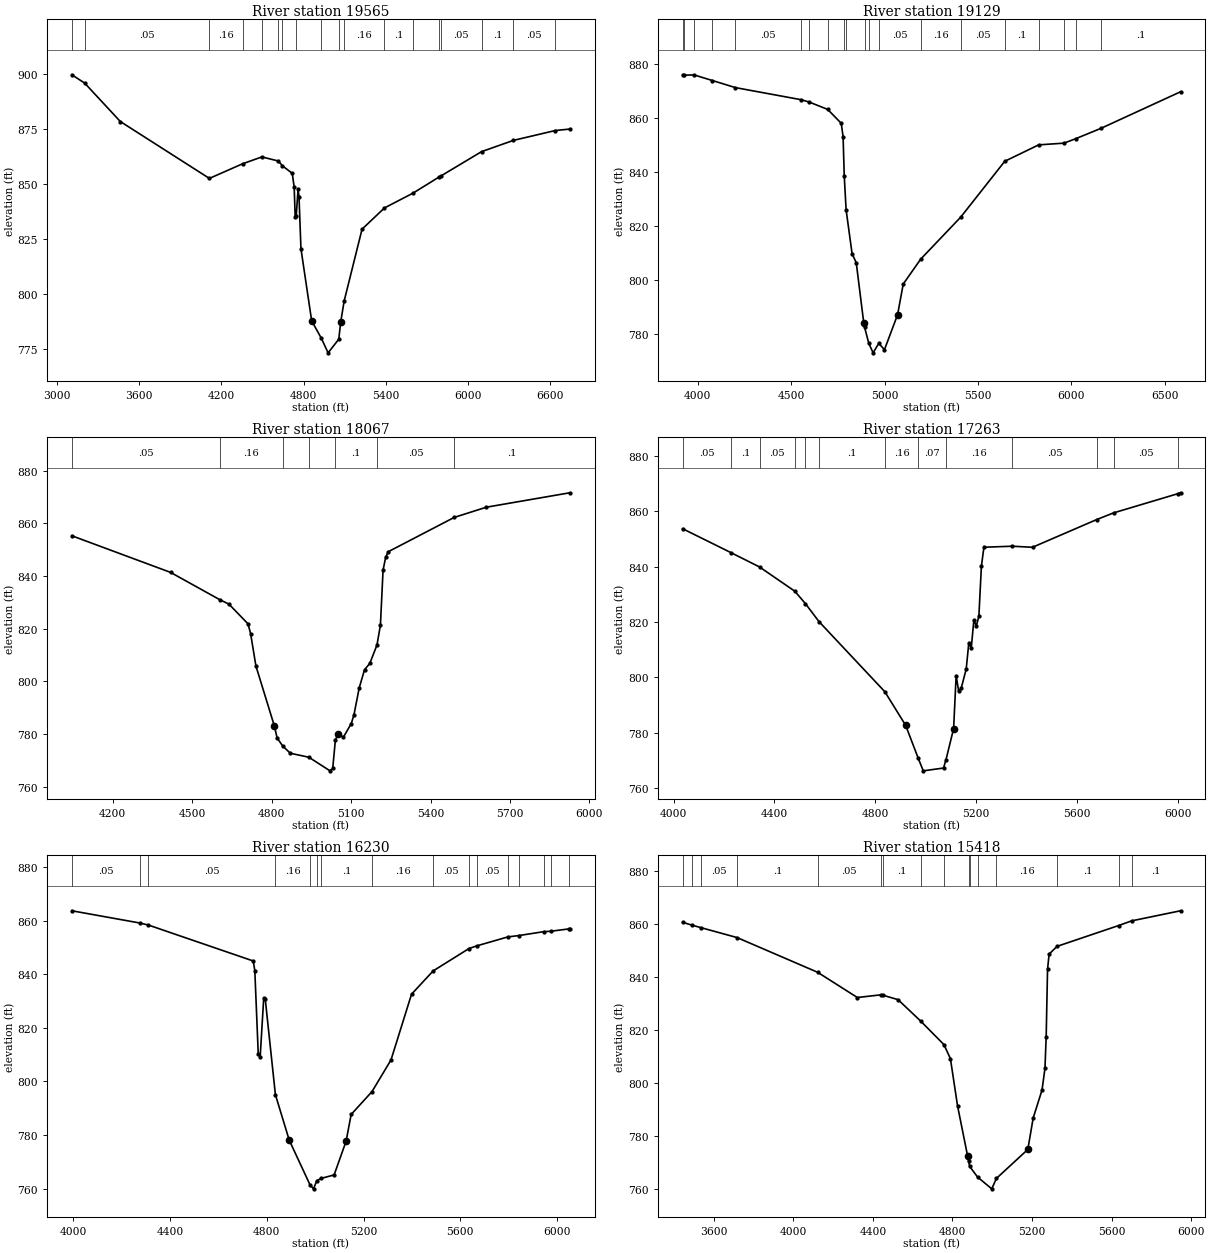
Type RM Length L Ch R = 1 ,19565   ,436,436,436
BEGIN DESCRIPTION:
CYPRESS CREEK 28.0
END DESCRIPTION:
XS GIS Cut Line= 4
      2983024.86      10108552.5      2982170.73     10108274.74
      2981212.39     10107371.96       2979893.2     10106851.23
#Sta/Elev= 30
  3108.6  899.51  3202.1  895.73  3462.3  878.29    4112  852.49  4354.3  859.13
  4494.8  862.24    4615  860.39  4644.9  858.21  4716.5  854.79  4730.6  848.51
  4737.9  835.12  4745.4  835.35  4758.9  847.63  4765.8   844.2    4780  820.59
  4858.1  787.89  4928.9  779.94    4978  773.35  5055.9  779.53  5070.1  787.37
  5095.3  796.88  5225.8  829.46  5389.5   839.1  5598.5  845.84    5789  853.18
  5799.9  853.55  6097.7  864.64  6330.6  869.75    6635  874.21  6741.6  874.88
#Mann= 18 ,-1 , 0
  3108.6      .1       0  3202.1     .05       0    4112     .16       0
  4354.3     .05       0  4494.8      .1       0    4615     .05       0
  4644.9      .1       0  4745.4     .16       0  4928.9     .07       0
  5055.9      .1       0  5095.3     .16       0  5389.5      .1       0
  5598.5     .05       0    5789      .1       0  5799.9     .05       0
  6097.7      .1       0  6330.6     .05       0    6635      .1       0
Bank Sta=4858.1,5070.1
XS Rating Curve= 0 ,0
Exp/Cntr=0.3,0.1

Type RM Length L Ch R = 1 ,19129   ,1062,1062,1062
BEGIN DESCRIPTION:
CYPRESS CREEK 27.0
END DESCRIPTION:
XS GIS Cut Line= 3
      2982722.58     10107351.85      2981503.84     10107212.96
      2980206.06     10106588.36
#Sta/Elev= 30
  3918.4  876.17  3928.6  876.04  3980.1  876.11  4077.7  874.05  4201.2  871.42
  4554.4  866.92  4596.6  866.06  4695.5  863.34    4768  858.21    4778   853.3
  4784.2  838.73  4794.3   826.1  4826.2  809.89  4848.5  806.54  4888.8  784.19
  4893.2  782.63  4915.7  776.66  4938.8  773.15  4969.3  776.68  4999.5   774.3
  5069.9  787.28  5100.1  798.64  5193.5  807.85  5408.2  823.44  5643.9  844.12
  5825.6   850.2  5961.3  850.84    6026  852.55  6157.8  856.28  6585.3  869.87
#Mann= 20 ,-1 , 0
  3918.4     .05       0  3928.6      .1       0  3980.1     .05       0
  4077.7      .1       0  4201.2     .05       0  4554.4      .1       0
  4596.6     .05       0  4695.5      .1       0  4784.2     .05       0
  4794.3     .16       0  4893.2     .05       0  4915.7    .035       0
  4969.3     .05       0  5193.5     .16       0  5408.2     .05       0
  5643.9      .1       0  5825.6     .05       0  5961.3      .1       0
    6026     .05       0  6157.8      .1       0
Bank Sta=4888.8,5069.9
XS Rating Curve= 0 ,0
Exp/Cntr=0.3,0.1

Type RM Length L Ch R = 1 ,18067   ,804,804,804
BEGIN DESCRIPTION:
CYPRESS CREEK 26.0
END DESCRIPTION:
XS GIS Cut Line= 3
      2982149.71     10106716.46      2981656.62     10106313.66
      2980413.53     10106285.88
#Sta/Elev= 30
  4045.8  855.25  4418.5  841.36    4604  831.02  4638.9  829.32  4710.7  821.86
  4720.7  818.14  4740.7  805.86  4810.7  782.98  4820.7  778.57  4841.7   775.5
  4870.7  772.74  4940.7  771.23  5020.5  766.07  5030.7     767  5040.7  777.67
  5050.7  780.07  5070.8   778.8  5100.8  784.02  5110.8  787.28  5130.8  797.56
  5150.8  804.43  5170.8  806.84  5197.8  813.82  5210.8  821.34  5220.8  842.22
  5230.8  847.18  5240.8  849.23  5489.6  862.23  5610.9   866.1  5925.9  871.57
#Mann= 7 ,-1 , 0
  4045.8     .05       0    4604     .16       0  4841.7      .1       0
  4940.7     .07       0  5040.7      .1       0  5197.8     .05       0
  5489.6      .1       0
Bank Sta=4810.7,5050.7
XS Rating Curve= 0 ,0
Exp/Cntr=0.3,0.1

Type RM Length L Ch R = 1 ,17263   ,1033,1033,1033
BEGIN DESCRIPTION:
CYPRESS CREEK 24.0
END DESCRIPTION:
XS GIS Cut Line= 4
      2982180.95     10106629.66      2981772.94     10106182.58
      2981794.64     10105436.05      2981430.08      10104932.6
#Sta/Elev= 30
  4035.8  853.62  4228.6  844.95  4340.7  839.84  4480.7  831.09  4522.5  826.64
  4576.9   820.1  4837.6  794.86    4920  782.75  4970.1  770.83  4989.8  766.36
  5070.1  767.37  5080.1  770.44  5110.1  781.59  5120.1  800.71  5130.1  795.09
  5140.1  796.08  5160.1  803.11  5170.1  812.29  5180.1  810.68  5190.2   820.6
  5200.2  818.61  5210.2  822.06  5220.2  840.07  5230.2  846.95  5342.9  847.31
  5422.8  846.93  5676.8   856.9  5744.3  859.33  5999.3  866.25  6009.5  866.57
#Mann= 13 ,-1 , 0
  4035.8     .05       0  4228.6      .1       0  4340.7     .05       0
  4480.7      .1       0  4522.5     .16       0  4576.9      .1       0
  4837.6     .16       0  4970.1     .07       0  5080.1     .16       0
  5342.9     .05       0  5676.8      .1       0  5744.3     .05       0
  5999.3      .1       0
Bank Sta=4920,5110.1
XS Rating Curve= 0 ,0
Exp/Cntr=0.3,0.1

Type RM Length L Ch R = 1 ,16230   ,812,812,812
BEGIN DESCRIPTION:
CYPRESS CREEK 23.0
END DESCRIPTION:
XS GIS Cut Line= 3
      2983053.32     10106555.82      2982884.05     10105956.88
      2981983.01     10104839.25
#Sta/Elev= 30
  3994.4  863.63  4275.1  859.07  4310.9   858.3    4744   844.9  4750.5  841.31
  4764.8  810.02  4772.8  809.26  4787.2  830.96  4793.6  830.73  4835.6  795.03
  4892.8  778.05  4979.1  761.31  4993.1   759.9  5006.4  762.91  5023.6  763.77
  5078.3  765.09  5127.9  777.71  5148.7  787.65  5234.8  796.17  5313.4  807.99
  5398.2   832.5  5487.5  841.19  5635.8  849.55  5666.8  850.51  5796.7  853.89
  5842.1  854.39  5946.1  855.86  5972.8  855.98  6050.9   856.9  6052.4  856.85
#Mann= 16 ,-1 , 0
  3994.4     .05       0  4275.1      .1       0  4310.9     .05       0
  4835.6     .16       0  4979.1     .07       0  5006.4     .16       0
  5023.6      .1       0  5234.8     .16       0  5487.5     .05       0
  5635.8     .16       0  5666.8     .05       0  5796.7      .1       0
  5842.1     .05       0  5946.1      .1       0  5972.8     .05       0
  6050.9      .1       0
Bank Sta=4892.8,5127.9
XS Rating Curve= 0 ,0
Exp/Cntr=0.3,0.1

Type RM Length L Ch R = 1 ,15418   ,1179,1179,1179
BEGIN DESCRIPTION:
CYPRESS CREEK 22.0
END DESCRIPTION:
XS GIS Cut Line= 4
      2983134.05     10106528.93      2983349.33      10105320.6
      2982901.41     10104685.18      2982472.57     10104429.61
#Sta/Elev= 30
  3442.9  860.75  3489.6   859.7  3535.6  858.73  3716.7     855  4121.9  841.89
  4321.7  832.36  4440.9  833.38  4448.4  833.27  4526.4  831.55  4640.6  823.43
  4757.1  814.58  4789.7   809.3  4825.5  791.49  4875.9  772.64  4881.1  770.62
  4886.7  768.57  4926.4  764.56  4997.6  760.12  5021.2  764.06    5179  774.99
    5206  786.88  5250.4  797.41  5265.2   805.6  5271.3  817.46  5278.2  843.01
  5286.1  848.74  5325.6  851.66  5635.3  859.53  5700.9   861.3  5946.9  865.11
#Mann= 16 ,-1 , 0
  3442.9     .05       0  3489.6      .1       0  3535.6     .05       0
  3716.7      .1       0  4121.9     .05       0  4440.9     .16       0
  4448.4      .1       0  4640.6     .05       0  4757.1     .16       0
  4881.1      .1       0  4886.7     .16       0  4926.4     .07       0
  5021.2     .16       0  5325.6      .1       0  5635.3     .05       0
  5700.9      .1       0
Bank Sta=4875.9,5179
XS Rating Curve= 0 ,0
Exp/Cntr=0.3,0.1

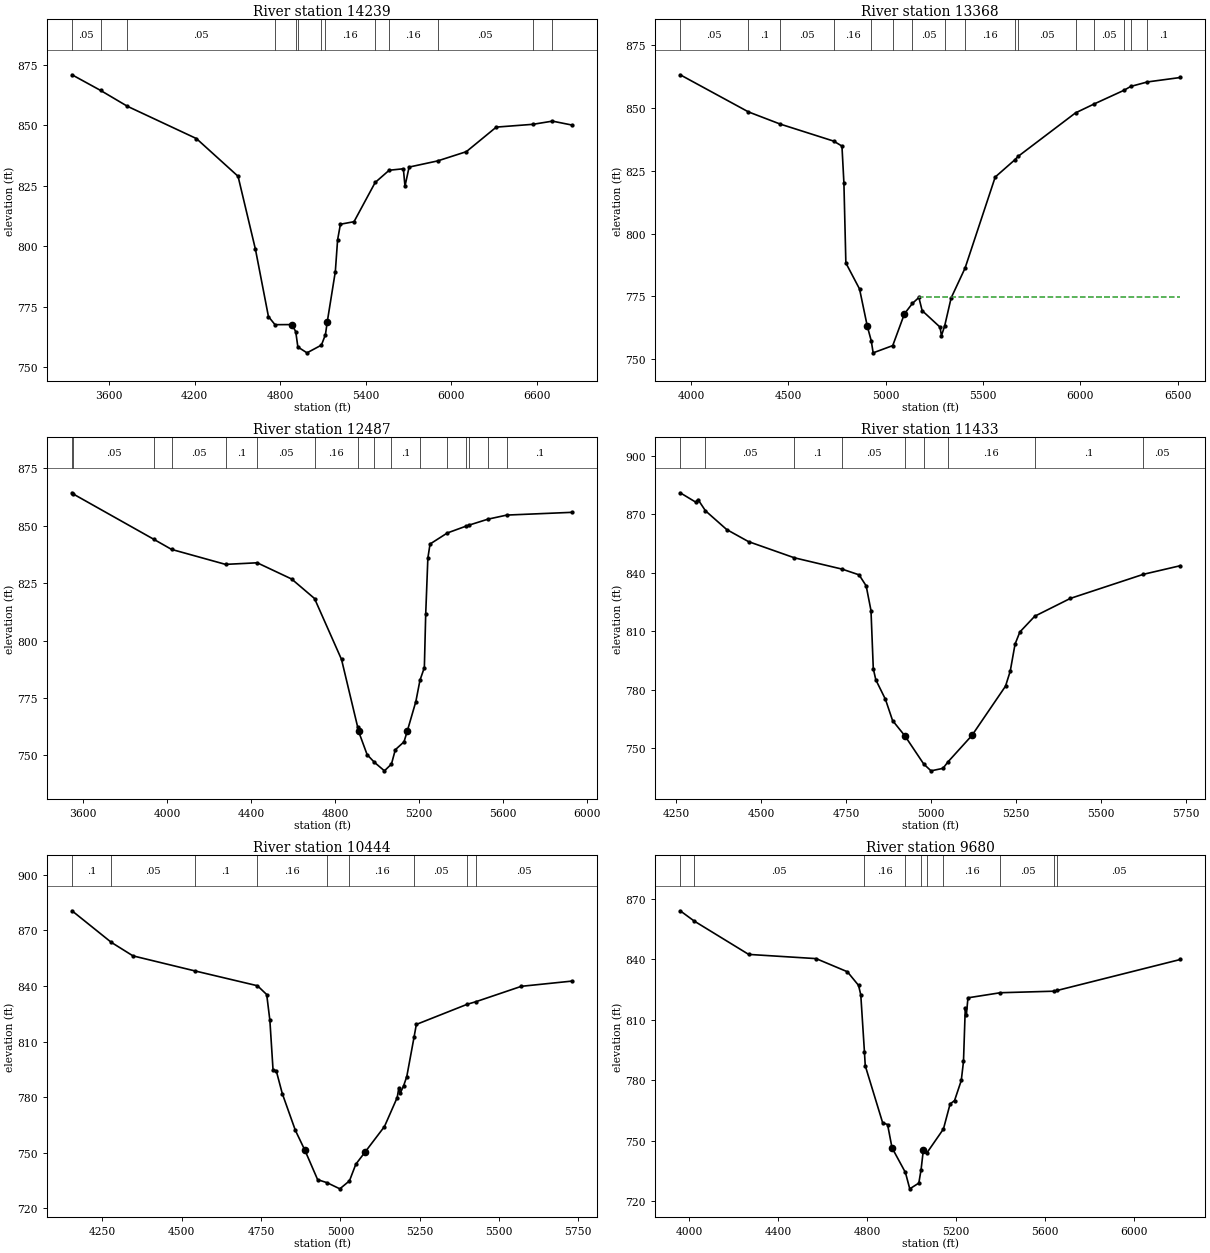
Type RM Length L Ch R = 1 ,14239   ,871,871,871
BEGIN DESCRIPTION:
CYPRESS CREEK 21.0
END DESCRIPTION:
XS GIS Cut Line= 5
       2984431.8     10106560.18      2984015.13     10105553.24
      2984223.46     10104741.61      2983568.08       10104568.
      2982817.23     10104064.53
#Sta/Elev= 30
  3339.4  870.83  3540.1  864.36  3728.2  857.81  4212.2  844.47  4504.5  828.88
  4626.8  798.62  4717.7   770.9  4763.8  767.54  4882.9  767.58  4909.3  764.64
  4924.2  758.32  4988.2   755.9  5089.4  759.09  5117.7  763.44  5130.7  768.79
  5187.1   789.5    5203   802.6  5222.7  809.06  5318.1   810.1  5466.6  826.31
  5564.8  831.37  5664.5  831.98  5675.7  824.77  5704.7  832.68  5904.5  835.22
  6106.3  839.05  6316.3   849.2  6573.9  850.36  6710.5  851.67  6849.1  850.03
#Mann= 13 ,-1 , 0
  3339.4     .05       0  3540.1      .1       0  3728.2     .05       0
  4763.8      .1       0  4909.3     .16       0  4924.2     .07       0
  5089.4      .1       0  5117.7     .16       0  5466.6     .05       0
  5564.8     .16       0  5904.5     .05       0  6573.9      .1       0
  6710.5     .05       0
Bank Sta=4882.9,5130.7
XS Rating Curve= 0 ,0
Exp/Cntr=0.3,0.1

Type RM Length L Ch R = 1 ,13368   ,881,881,881
BEGIN DESCRIPTION:
CYPRESS CREEK 19.0
END DESCRIPTION:
XS GIS Cut Line= 4
       2985217.4     10105453.45      2984913.57     10104706.88
       2984496.9     10104672.16      2983603.16     10103665.62
#Sta/Elev= 30
  3943.8   863.2  4294.8  848.41  4458.5  843.55  4732.4  836.79    4775  834.81
    4785  820.19  4795.1  788.27  4865.3  777.93  4905.5  762.99  4925.5  757.29
  4935.3  752.49  5035.9  755.37  5096.1  768.04  5137.3  772.18  5170.2  774.53
    5187   769.3    5279  762.72  5286.2   759.3  5302.7  763.18  5335.9  774.33
  5407.6  786.24  5562.5  822.49  5661.6  829.23  5681.2  830.77  5975.1  848.03
  6071.4   851.6  6224.5  857.04  6258.8  858.56  6344.6  860.35    6514  862.12
#Mann= 16 ,-1 , 0
  3943.8     .05       0  4294.8      .1       0  4458.5     .05       0
  4732.4     .16       0  4925.5     .07       0  5035.9      .1       0
  5137.3     .05       0  5302.7      .1       0  5407.6     .16       0
  5661.6      .1       0  5681.2     .05       0  5975.1      .1       0
  6071.4     .05       0  6224.5      .1       0  6258.8     .05       0
  6344.6      .1       0
#XS Ineff= 2 , 0
                         5170.97          774.67
Permanent Ineff=
       T       T
Bank Sta=4905.5,5096.1
XS Rating Curve= 0 ,0
Exp/Cntr=0.3,0.1

Type RM Length L Ch R = 1 ,12487   ,1054,1054,1054
BEGIN DESCRIPTION:
CYPRESS CREEK 18.0
END DESCRIPTION:
XS GIS Cut Line= 4
      2985497.35     10105340.59       2985041.6     10104667.82
      2984750.81     10103552.37      2984459.99     10103252.87
#Sta/Elev= 30
  3547.2  864.37  3554.3  863.78  3937.7  844.07  4021.3  839.72  4278.5  833.19
  4429.5  833.88  4593.4  826.82  4702.5  818.33  4831.2  791.77    4908  762.36
  4912.1  760.53  4953.1  750.32    4988  746.97  5035.5  743.28  5068.9  746.22
  5087.4  752.48  5128.8  755.91  5144.7  760.71  5185.2  773.46  5204.7   782.7
  5225.7  788.27  5232.1  811.45  5242.4  835.93  5252.8  842.06  5335.2  846.87
  5421.7  849.75  5439.1   850.3  5529.1  852.89  5618.6  854.66    5930  855.86
#Mann= 16 ,-1 , 0
  3547.2      .1       0  3554.3     .05       0  3937.7      .1       0
  4021.3     .05       0  4278.5      .1       0  4429.5     .05       0
  4702.5     .16       0    4908      .1       0    4988     .07       0
  5068.9      .1       0  5204.7     .16       0  5335.2      .1       0
  5421.7     .05       0  5439.1      .1       0  5529.1     .05       0
  5618.6      .1       0
Bank Sta=4912.1,5144.7
XS Rating Curve= 0 ,0
Exp/Cntr=0.3,0.1

Type RM Length L Ch R = 1 ,11433   ,989,989,989
BEGIN DESCRIPTION:
CYPRESS CREEK 16.0
END DESCRIPTION:
XS GIS Cut Line= 2
      2986291.63     10104294.58      2985302.77     10103201.64
#Sta/Elev= 30
  4260.9  881.11  4306.1  876.37  4313.5  877.64  4335.3  871.88    4398  862.24
  4462.2  856.05  4597.3  847.75  4738.2  841.93    4788     839  4808.9  833.34
  4823.1  820.69  4829.9  790.85  4837.3  785.16  4865.7  775.13  4886.7  764.25
  4922.5  756.49  4923.2  756.34  4978.6  741.92    5000  738.44  5035.3  739.72
  5049.5  742.95  5120.5  756.59  5219.5  781.89  5233.4  789.59  5247.6  803.46
  5261.8  809.69  5305.6  817.77  5410.5  826.91  5625.8  839.28  5734.8   843.7
#Mann= 9 ,-1 , 0
  4260.9      .1       0  4335.3     .05       0  4597.3      .1       0
  4738.2     .05       0  4923.2     .16       0  4978.6     .07       0
  5049.5     .16       0  5305.6      .1       0  5625.8     .05       0
Bank Sta=4922.5,5120.5
XS Rating Curve= 0 ,0
Exp/Cntr=0.3,0.1

Type RM Length L Ch R = 1 ,10444   ,764,764,764
BEGIN DESCRIPTION:
CYPRESS CREEK 15.0
END DESCRIPTION:
XS GIS Cut Line= 2
      2986960.03      10102983.8      2985388.81     10102853.59
#Sta/Elev= 30
    4154  880.59    4278  863.54  4346.2  856.25  4541.2  848.14  4738.6  840.12
  4767.7  835.38  4777.7  821.44  4787.7  794.66  4797.8  794.23  4816.8  781.92
    4858  762.08  4888.1  751.32  4928.2  735.46  4958.3  733.79  4998.2   730.5
  5028.5   734.8  5048.6  743.79  5078.7  750.57  5138.9  764.14    5179  779.78
    5184  784.86  5189.1  782.31  5199.1  786.06  5209.2  791.11    5232  812.27
  5239.3  819.24  5399.8  830.13  5426.9   831.5  5570.4  839.82  5730.6  842.65
#Mann= 9 ,-1 , 0
    4154      .1       0    4278     .05       0  4541.2      .1       0
  4738.6     .16       0  4958.3     .07       0  5028.5     .16       0
    5232     .05       0  5399.8      .1       0  5426.9     .05       0
Bank Sta=4888.1,5078.7
XS Rating Curve= 0 ,0
Exp/Cntr=0.3,0.1

Type RM Length L Ch R = 1 ,9680    ,1100,1100,1100
BEGIN DESCRIPTION:
CYPRESS CREEK 14.0
END DESCRIPTION:
XS GIS Cut Line= 4
      2987124.93     10102506.36      2986708.27     10102211.23
      2985744.73      10102133.1      2985249.95     10102723.36
#Sta/Elev= 30
  3959.9     864    4023   858.9  4267.6  842.38  4570.6  840.29  4711.1  833.78
  4761.3  827.03  4771.3  822.36  4787.8  794.01  4791.4  787.19  4869.6  758.92
  4891.7  758.05  4911.7  746.52  4971.9  734.28  4991.4  726.18  5032.1  729.03
  5042.2  735.67  5052.2   745.2  5066.6  743.72  5142.7  755.84  5172.6  768.24
  5192.7  769.95  5222.8  779.88  5232.8   789.3  5240.8  815.65  5245.8   812.5
  5252.9  820.86  5398.4  823.38  5641.6  824.15  5653.4   824.5  6207.4  839.87
#Mann= 10 ,-1 , 0
  3959.9      .1       0    4023     .05       0  4787.8     .16       0
  4971.9     .07       0  5042.2     .16       0  5066.6     .12       0
  5142.7     .16       0  5398.4     .05       0  5641.6      .1       0
  5653.4     .05       0
Bank Sta=4911.7,5052.2
XS Rating Curve= 0 ,0
Exp/Cntr=0.3,0.1

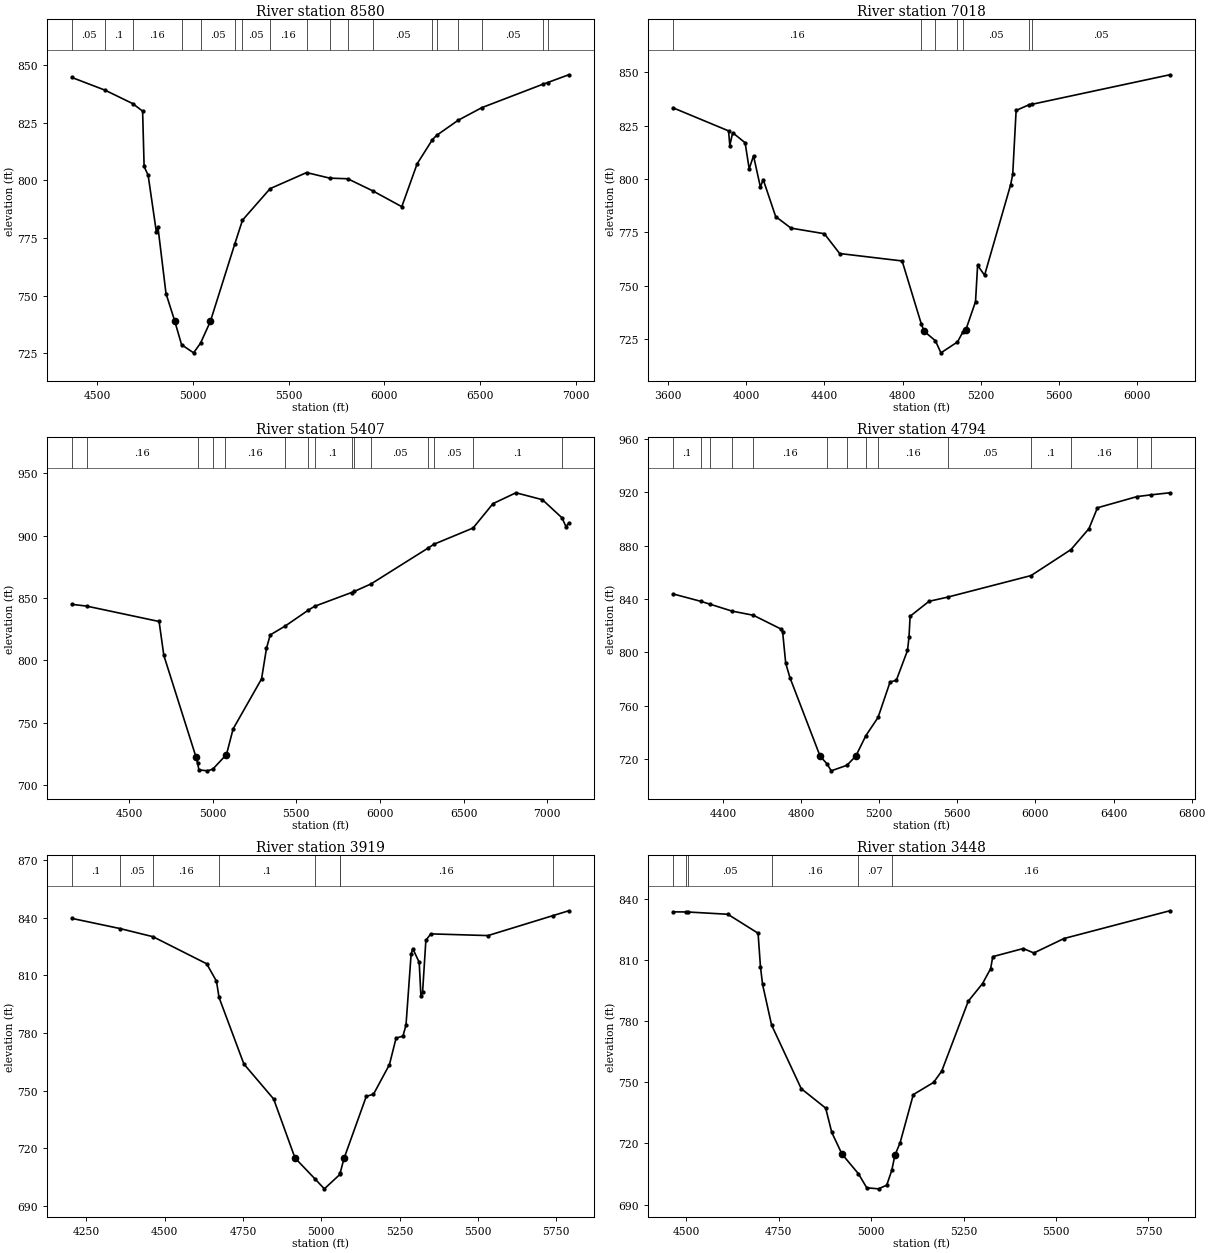
Type RM Length L Ch R = 1 ,8580    ,1562,1562,1562
BEGIN DESCRIPTION:
CYPRESS CREEK 12.0
END DESCRIPTION:
XS GIS Cut Line= 4
      2986499.97     10100666.07      2986282.92     10100796.29
      2985744.73     10101612.27      2985042.54     10102782.58
#Sta/Elev= 30
  4368.1  844.64    4542  839.11  4686.6  833.28  4737.9  830.04  4745.7  806.03
  4766.7  802.25  4809.8  777.55  4817.9  779.77    4860  750.94  4905.2  739.13
  4941.4  728.74  5004.3  725.22  5040.7  729.47  5091.9  738.87  5219.6  772.51
  5259.6  782.77  5403.8  796.42  5594.3  803.39  5715.2  800.98  5809.3  800.71
  5938.8  795.51  6091.6   788.6  6171.8  807.18  6251.8  817.71  6274.4  819.57
  6386.2  826.08  6509.8  831.55  6829.6  841.73  6853.8  842.44  6963.5   845.8
#Mann= 18 ,-1 , 0
  4368.1     .05       0    4542      .1       0  4686.6     .16       0
  4941.4     .07       0  5040.7     .05       0  5219.6      .1       0
  5259.6     .05       0  5403.8     .16       0  5594.3      .1       0
  5715.2     .05       0  5809.3     .16       0  5938.8     .05       0
  6251.8      .1       0  6274.4     .05       0  6386.2      .1       0
  6509.8     .05       0  6829.6      .1       0  6853.8     .05       0
Bank Sta=4905.2,5091.9
XS Rating Curve= 0 ,0
Exp/Cntr=0.3,0.1

Type RM Length L Ch R = 1 ,7018    ,1611,1611,1611
BEGIN DESCRIPTION:
CYPRESS CREEK 11.0
END DESCRIPTION:
XS GIS Cut Line= 4
      2985788.11     10100683.46      2985067.65     10101282.41
       2984598.9     10101690.39      2984373.34     10102644.65
#Sta/Elev= 30
  3626.6  833.33  3911.1  822.49  3917.6  815.63  3931.9  821.66  3995.7  816.92
  4016.5  804.72  4038.7  810.79  4073.8  796.16  4088.1  799.69  4151.9  782.33
  4230.1  776.92  4400.6   774.3  4478.7  765.02    4798  761.54  4896.1  731.97
    4911  728.54    4968  724.15  4996.2  718.48  5080.9  723.57  5109.3  728.41
  5123.7  729.33    5173  742.46  5183.7  759.51  5219.2  754.83  5352.8  797.34
  5363.1  802.23  5380.5  832.07  5448.4  834.81  5460.6  834.93  6165.5  848.78
#Mann= 7 ,-1 , 0
  3626.6     .16       0  4896.1      .1       0    4968     .07       0
  5080.9      .1       0  5109.3     .05       0  5448.4     .16       0
  5460.6     .05       0
Bank Sta=4911,5123.7
XS Rating Curve= 0 ,0
Exp/Cntr=0.3,0.1

Type RM Length L Ch R = 1 ,5407    ,613,613,613
BEGIN DESCRIPTION:
CYPRESS CREEK 8.0
END DESCRIPTION:
XS GIS Cut Line= 4
      2986274.25     10100440.39      2985779.45     10100501.16
      2984885.35     10100075.81      2983479.15     10100544.54
#Sta/Elev= 30
  4157.4  844.84  4245.7  843.43  4679.2  831.07  4707.5  803.88  4900.6  722.08
  4909.4  717.46  4917.4  712.09  4968.1  711.29  5000.3  712.65  5073.2  723.12
    5082  724.31  5121.8  744.91  5291.9  785.03  5321.4   809.6  5343.6  820.29
  5433.7  827.48  5571.1  840.13  5608.8  843.25  5830.1  854.32  5846.9  855.22
  5946.6  861.22  6286.4  889.86  6322.9  893.05  6556.4  906.04  6675.8  925.61
  6812.8  934.31  6970.9  928.77  7088.6  914.18  7111.6  907.25  7128.3  909.93
#Mann= 15 ,-1 , 0
  4157.4      .1       0  4245.7     .16       0  4909.4    .035       0
  5000.3     .05       0  5073.2     .16       0  5433.7      .1       0
  5571.1     .05       0  5608.8      .1       0  5830.1     .05       0
  5846.9      .1       0  5946.6     .05       0  6286.4      .1       0
  6322.9     .05       0  6556.4      .1       0  7088.6     .16       0
Bank Sta=4900.6,5082
XS Rating Curve= 0 ,0
Exp/Cntr=0.3,0.1

Type RM Length L Ch R = 1 ,4794    ,875,875,875
BEGIN DESCRIPTION:
CYPRESS CREEK 7.0
END DESCRIPTION:
XS GIS Cut Line= 3
       2986465.2     10100223.37      2985032.92     10099416.09
      2984173.58       10099147.
#Sta/Elev= 30
  4143.2  843.89  4285.4  838.35  4334.1  836.15  4444.7  831.05  4555.3  827.88
  4699.4  817.39  4705.1  815.61    4721  791.97  4742.7  781.14  4897.1  722.36
  4931.9  716.65  4954.2  711.34  5034.8  715.52  5080.7  722.55  5131.3  737.64
    5194  751.37  5255.5   777.9  5287.4  779.13  5344.7   801.5  5352.4  811.44
  5358.1  827.13  5454.9  838.32  5551.9  841.52  5977.7  857.62  6181.8  877.07
    6274  892.75  6317.5  908.39    6521   916.8    6590  918.04  6687.8  919.63
#Mann= 14 ,-1 , 0
  4143.2      .1       0  4285.4     .05       0  4334.1     .16       0
  4444.7     .05       0  4555.3     .16       0  4931.9    .033       0
  5034.8     .16       0  5131.3     .12       0    5194     .16       0
  5551.9     .05       0  5977.7      .1       0  6181.8     .16       0
    6521     .05       0    6590     .16       0
Bank Sta=4897.1,5080.7
XS Rating Curve= 0 ,0
Exp/Cntr=0.3,0.1

Type RM Length L Ch R = 1 ,3919    ,471,471,471
BEGIN DESCRIPTION:
CYPRESS CREEK 6.0
END DESCRIPTION:
XS GIS Cut Line= 2
      2986543.33     10100023.69       2986031.2     10098522.01
#Sta/Elev= 30
  4203.4  839.57  4357.3  834.28  4462.7  830.04    4634  815.98  4665.3  806.92
  4673.5  798.47  4752.8   763.9  4847.9   745.7    4916  715.07  4978.7  704.38
  5009.8  699.02  5059.2  706.48  5060.6  707.48  5072.7  714.89  5143.7  747.08
  5166.7   748.2  5217.6  763.58  5238.8  777.36  5260.7  778.39  5270.5  784.17
  5286.8  820.95  5292.1  823.87  5312.7  816.71  5318.1  799.11  5323.4  801.17
  5333.9  828.11  5349.5  831.52  5532.2  830.63  5738.6  840.95    5790  843.52
#Mann= 8 ,-1 , 0
  4203.4      .1       0  4357.3     .05       0  4462.7     .16       0
  4673.5      .1       0  4978.7     .07       0  5059.2      .1       0
  5060.6     .16       0  5738.6     .05       0
Bank Sta=4916,5072.7
XS Rating Curve= 0 ,0
Exp/Cntr=0.3,0.1

Type RM Length L Ch R = 1 ,3448    ,793,793,793
BEGIN DESCRIPTION:
CYPRESS CREEK 5.0
END DESCRIPTION:
XS GIS Cut Line= 2
      2986933.98     10099537.64      2986309.06     10098348.55
#Sta/Elev= 30
  4464.3  833.63  4499.8  833.57    4504  833.56  4612.9  832.44  4694.6  823.14
  4701.1  806.68  4706.7   798.1  4731.2  778.07  4811.3  746.89  4877.4  737.34
  4893.8  725.45  4921.5  714.78  4965.8  705.18  4988.4  698.25  5020.2  697.74
  5042.5  699.56  5056.2  706.91  5064.5  714.18  5078.7  720.41  5114.3  743.98
  5169.1  749.94  5191.2  755.52  5262.9   789.8  5301.4  798.43  5323.4  805.77
  5329.1  811.65  5411.6  815.63  5440.2  813.45  5521.8  820.55  5807.6  834.15
#Mann= 6 ,-1 , 0
  4464.3     .05       0  4499.8      .1       0    4504     .05       0
  4731.2     .16       0  4965.8     .07       0  5056.2     .16       0
Bank Sta=4921.5,5064.5
XS Rating Curve= 0 ,0
Exp/Cntr=0.3,0.1

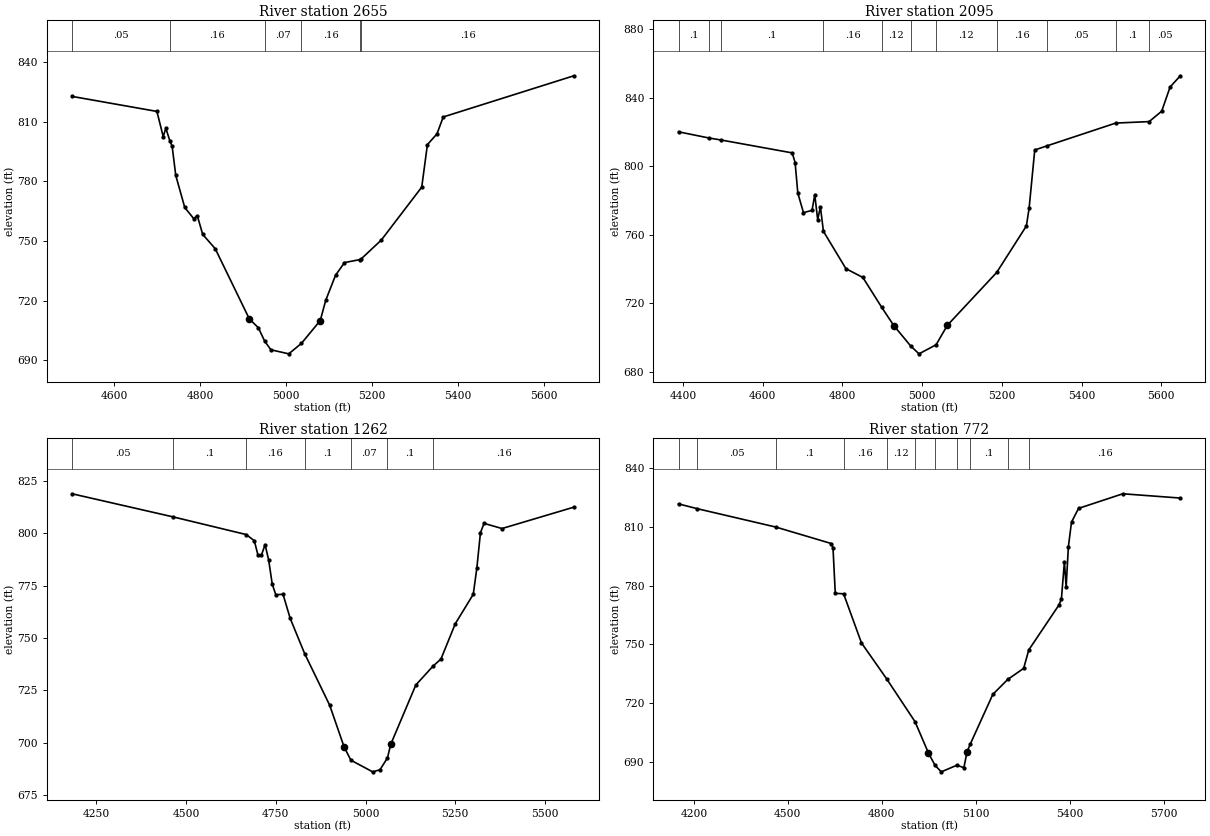
Type RM Length L Ch R = 1 ,2655    ,560,560,560
BEGIN DESCRIPTION:
CYPRESS CREEK 4.0
END DESCRIPTION:
XS GIS Cut Line= 2
      2987602.39     10098825.83      2986664.88     10098131.38
#Sta/Elev= 30
    4502  822.82  4699.3  815.25  4713.9  802.57  4720.1  806.75  4729.6  800.27
  4734.7  797.68  4743.1     783    4764  766.86  4784.8  761.26  4793.1  762.79
  4805.7  753.31  4834.9  746.09  4914.2   710.7  4935.1  706.29  4949.7  699.56
  4964.3  695.17  5005.8  693.13  5035.3   698.4  5079.1  709.91  5091.8  720.11
  5114.6  732.72  5135.4   739.1  5171.8  740.63  5174.6  741.04    5221  750.45
    5315  777.11  5328.2  798.54  5350.4  803.93    5365  812.46  5668.7  833.21
#Mann= 6 ,-1 , 0
    4502     .05       0  4729.6     .16       0  4949.7     .07       0
  5035.3     .16       0  5171.8     .12       0  5174.6     .16       0
Bank Sta=4914.2,5079.1
XS Rating Curve= 0 ,0
Exp/Cntr=0.3,0.1

Type RM Length L Ch R = 1 ,2095    ,833,833,833
BEGIN DESCRIPTION:
CYPRESS CREEK 3.0
END DESCRIPTION:
XS GIS Cut Line= 2
      2987923.56       10098522.      2987064.14     10097601.82
#Sta/Elev= 30
  4388.8  820.19  4466.3  816.52  4495.7   815.4    4674  807.87  4681.3  802.23
  4688.1  784.35  4702.3  772.96  4723.8  774.27  4730.6  783.47  4737.9  768.89
  4744.8  776.22  4752.4  762.01  4808.8   740.2  4851.3  735.07  4898.6  717.61
    4929  706.92  4971.5  694.96  4992.2  690.42    5035  695.71  5063.3  707.09
  5187.2  738.01  5261.6  765.16  5268.5  775.57  5282.6  809.57  5312.7  811.93
  5485.8   825.3  5569.7  826.16  5601.2  832.24  5622.2  846.38  5647.9  852.94
#Mann= 11 ,-1 , 0
  4388.8      .1       0  4466.3     .05       0  4495.7      .1       0
  4752.4     .16       0  4898.6     .12       0  4971.5     .07       0
    5035     .12       0  5187.2     .16       0  5312.7     .05       0
  5485.8      .1       0  5569.7     .05       0
Bank Sta=4929,5063.3
XS Rating Curve= 0 ,0
Exp/Cntr=0.3,0.1

Type RM Length L Ch R = 1 ,1262    ,490,490,490
BEGIN DESCRIPTION:
CYPRESS CREEK 2.0
END DESCRIPTION:
XS GIS Cut Line= 3
      2988192.65     10098591.39      2988218.69       10097489.
      2988201.33     10097193.91
#Sta/Elev= 30
  4182.1  818.84  4464.5  807.78  4667.4  799.39  4689.9  796.44  4699.9  789.73
  4709.9  789.57  4719.9   794.6  4729.9  787.26  4739.9  775.74  4749.9  770.65
  4769.9  770.92  4789.9   759.4  4830.2  742.59    4900  717.96    4940  698.15
 4959.09  691.74  5019.7  686.19    5040  687.17 5060.91  692.79    5070  699.27
    5140  727.62    5188  736.63    5210  739.99  5250.1  756.89  5300.1  770.87
  5310.1  783.47  5320.1  800.27  5330.1  804.72  5380.2  802.26  5580.4  812.46
#Mann= 7 ,-1 , 0
  4182.1     .05       0  4464.5      .1       0  4667.4     .16       0
  4830.2      .1       0 4959.09     .07       0 5060.91      .1       0
    5188     .16       0
Bank Sta=4940,5070
XS Rating Curve= 0 ,0
Exp/Cntr=0.3,0.1

Type RM Length L Ch R = 1 ,772     ,0,0,0
BEGIN DESCRIPTION:
CYPRESS CREEK 1.0
END DESCRIPTION:
XS GIS Cut Line= 3
      2988453.06     10098791.08      2988687.44     10097775.46
      2988444.37     10097271.97
#Sta/Elev= 30
  4151.2  821.88  4210.1  819.45  4461.6  810.02  4639.1  801.57  4644.2  799.27
  4651.4  776.09    4678  775.85  4734.9  750.74  4815.2  732.35  4905.9   710.4
  4948.7  694.38  4969.5  688.11  4989.8  684.72  5039.3  688.09  5061.9  686.88
  5072.1  695.06  5082.1  698.87  5154.2  724.36  5201.8  732.02  5252.6  737.68
  5268.9   747.1  5365.6  770.21  5373.1  773.25  5382.7  792.24  5388.2  779.38
  5395.3   799.9  5405.3  812.57  5427.9  819.57    5569  827.05  5752.6  824.86
#Mann= 11 ,-1 , 0
  4151.2      .1       0  4210.1     .05       0  4461.6      .1       0
    4678     .16       0  4815.2     .12       0  4905.9     .05       0
  4969.5    .035       0  5039.3     .05       0  5082.1      .1       0
  5201.8     .12       0  5268.9     .16       0
Bank Sta=4948.7,5072.1
XS Rating Curve= 0 ,0
Exp/Cntr=0.3,0.1

Chan Stop Cuts=-1
Use User Specified Reach Order=0
Composite Channel Slope=5