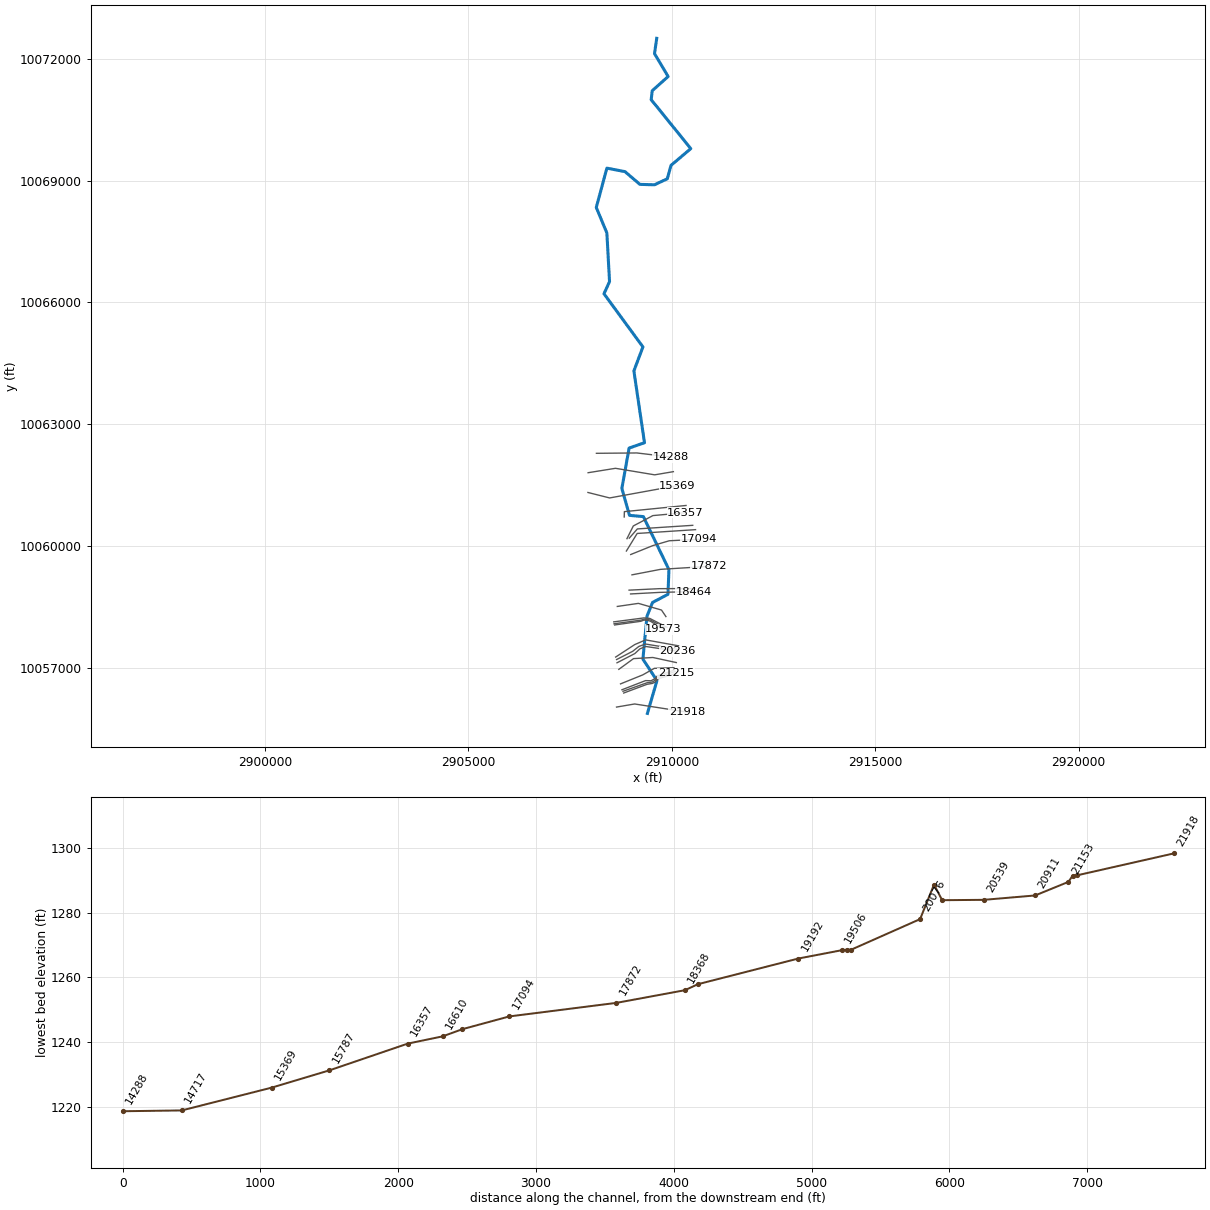
--- DEER CREEK.prj (project) ---

Proj Title=DEER CREEK Base Level Engineering
Current Plan=p01
Default Exp/Contr=0.3,0.1
English Units
Geom File=g01
Flow File=f01
Plan File=p01
Y Axis Title=Elevation
X Axis Title(PF)=Main Channel Distance
X Axis Title(XS)=Station
BEGIN DESCRIPTION:
DEER CREEK
END DESCRIPTION:
DSS Export Rating Curves= 0
DSS Export Rating Curve Sorted= 0
DSS Export Volume Flow Curves= 0
DXF OffsetX= 0
DXF OffsetY= 0
DXF ScaleX= 1
DXF ScaleY= 10

--- DEER CREEK.p01 (plan) ---

Plan Title=Multiple Run
Short Identifier=Multiple
Geom File=g01
Flow File=f01
Subcritical Flow
K Sum by GR= 0
Std Step Tol= 0.01
Critical Tol= 0.01
Num of Std Step Trials= 20
Max Error Tol= 0.3
Flow Tol Ratio= 0.001
Split Flow NTrial= 30
Split Flow Tol= 0.02
Split Flow Ratio= 0.02
Log Output Level= 0
Friction Slope Method= 1
Unsteady Friction Slope Method= 2
Unsteady Bridges Friction Slope Method= 1
Parabolic Critical Depth
Global Vel Dist=  1 , 1 , 1
Global Log Level= 0
CheckData=True
Encroach Param= -1, 0, 0, 0
BEGIN DESCRIPTION:
Multiple Run
END DESCRIPTION:

--- DEER CREEK.f01 (steady flow) ---

Flow Title=Multiple
Program Version=4.10
Number of Profiles= 7
Profile Names=10-year,25-year,50-year,1pct_min,100-year,1pct_plu,500-year
River Rch & RM=DEER CREEK,Reach-1         ,21918
    1380    2052    2652    2507    3390    4585    5563
River Rch & RM=DEER CREEK,Reach-1         ,15369
    2259    3436    4507    4317    5839    7896    9838
River Rch & RM=DEER CREEK,Reach-1         ,11528
    2550    3897    5128    4925    6660    9007   11284
River Rch & RM=DEER CREEK,Reach-1         ,9693
    2561    3907    5133    4923    6658    9004   11247
River Rch & RM=DEER CREEK,Reach-1         ,7075
    2916    4463    5876    5643    7632   10321   12929
River Rch & RM=DEER CREEK,Reach-1         ,6671
    2916    4463    5876    5643    7632   10321   12929
Boundary for River Rch & Prof#=DEER CREEK,Reach-1         , 1
Up Type= 0
Dn Type= 3
Dn Slope=0.005
Boundary for River Rch & Prof#=DEER CREEK,Reach-1         , 2
Up Type= 0
Dn Type= 3
Dn Slope=0.005
Boundary for River Rch & Prof#=DEER CREEK,Reach-1         , 3
Up Type= 0
Dn Type= 3
Dn Slope=0.005
Boundary for River Rch & Prof#=DEER CREEK,Reach-1         , 4
Up Type= 0
Dn Type= 3
Dn Slope=0.005
Boundary for River Rch & Prof#=DEER CREEK,Reach-1         , 5
Up Type= 0
Dn Type= 3
Dn Slope=0.005
Boundary for River Rch & Prof#=DEER CREEK,Reach-1         , 6
Up Type= 0
Dn Type= 3
Dn Slope=0.005
Boundary for River Rch & Prof#=DEER CREEK,Reach-1         , 7
Up Type= 0
Dn Type= 3
Dn Slope=0.005
DSS Import GetInterval= 0
DSS Import GetPeak= 0
DSS Import FillOption= 0

--- DEER CREEK.g01 (geometry) ---

Geom Title=Existing Conditions
Program Version=4.10

River Reach=DEER CREEK      ,Reach-1
Reach XY= 30
      2909398.96     10055892.01      2909634.25     10056698.92
      2909288.52      10057225.9      2909387.65     10058280.25
      2909525.02     10058620.56      2909904.71      10058820.9
      2909928.31     10059428.55      2909299.48     10060733.39
      2908958.95     10060763.64      2908770.92     10061424.91
       2908949.2     10062418.65      2909327.36     10062550.56
      2909066.74     10064316.12      2909288.82     10064907.29
       2908331.2     10066215.01      2908468.11     10066514.03
      2908402.44      10067710.5      2908141.97     10068337.54
      2908402.68     10069305.32       2908847.4     10069219.58
      2909214.62     10068905.78      2909572.61     10068895.75
      2909887.59     10069043.31      2909979.19     10069374.05
      2910465.93      10069784.8      2909491.97     10070989.81
      2909517.76     10071210.12      2909908.46     10071559.01
      2909573.73     10072123.21      2909627.84     10072498.63

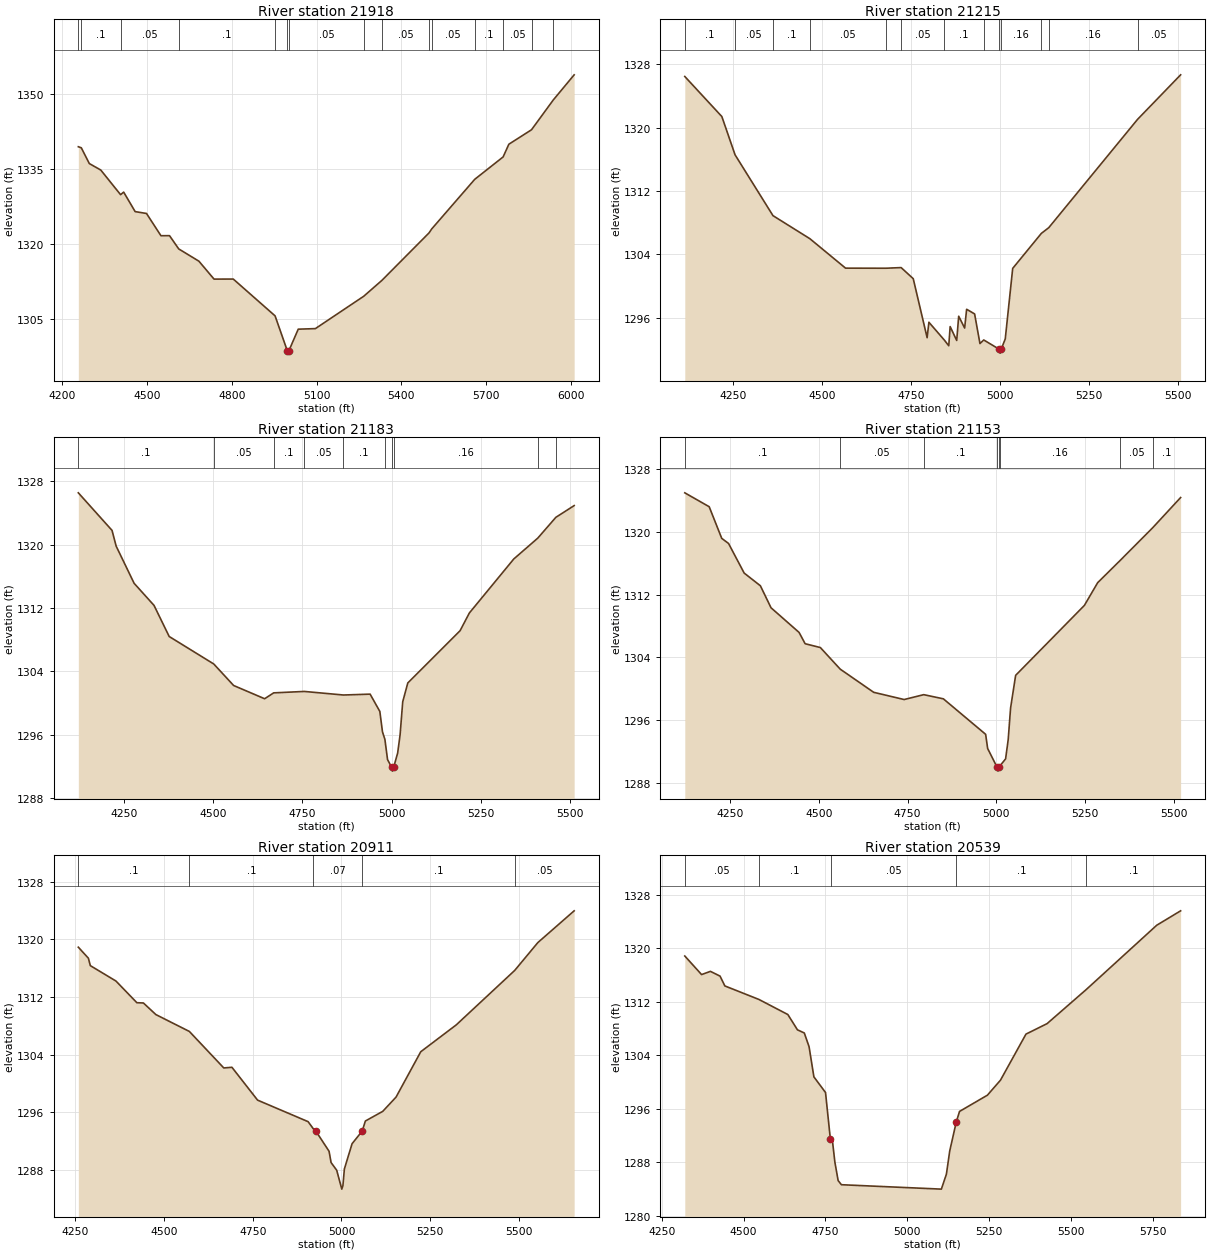
Type RM Length L Ch R = 1 ,21918   ,703,703,703
BEGIN DESCRIPTION:
DEER CREEK 48.0
END DESCRIPTION:
XS GIS Cut Line= 3
      2908640.14      10056047.3      2909085.05     10056123.26
      2910373.83     10055923.65
#Sta/Elev= 30
  4256.3  1339.4  4266.8 1339.19  4295.2 1336.05  4335.8 1334.76  4405.8 1329.86
  4416.9 1330.36  4457.5 1326.48  4497.7 1326.11  4548.8 1321.68  4579.2 1321.69
  4611.8 1319.05  4683.2 1316.61  4736.8 1313.04  4804.9 1313.05  4952.9 1305.72
    4996  1298.8  4998.8  1298.3    5002  1298.8  5034.9 1303.07  5095.6 1303.18
  5267.1 1309.64  5330.8 1312.77  5497.8 1322.23  5507.8 1323.05  5659.8 1332.91
  5760.3 1337.37  5780.6  1339.9  5860.8 1342.78  5937.7  1348.7  6011.8 1353.72
#Mann= 15 ,-1 , 0
  4256.3     .05       0  4266.8      .1       0  4405.8     .05       0
  4611.8      .1       0  4952.9     .05       0    4996    .035       0
    5002     .05       0  5267.1      .1       0  5330.8     .05       0
  5497.8      .1       0  5507.8     .05       0  5659.8      .1       0
  5760.3     .05       0  5860.8      .1       0  5937.7     .05       0
Bank Sta=4996,5002
XS Rating Curve= 0 ,0
Exp/Cntr=0.3,0.1

Type RM Length L Ch R = 1 ,21215   ,32,32,32
BEGIN DESCRIPTION:
Mapping XS 2b383745
END DESCRIPTION:
XS GIS Cut Line= 6
      2908815.92     10056392.35      2909391.04      10056607.2
      2909521.25      10056628.9      2909590.69     10056663.63
      2909662.31     10056743.92      2910105.34     10056873.59
#Sta/Elev= 30
  4115.4 1326.46  4219.5  1321.4  4256.6 1316.57  4363.1 1308.89  4466.7 1305.98
    4567 1302.26  4680.3 1302.25  4723.1 1302.33  4757.1 1300.93  4796.1 1293.48
  4801.1 1295.43  4844.8 1293.16  4856.9 1292.46  4860.8 1294.88  4879.2 1293.13
  4884.8 1296.19  4901.5  1294.7  4907.1 1297.07  4929.5 1296.48  4944.5 1292.74
  4955.2 1293.19  4998.3 1292.03  5001.1 1291.53  5004.3 1292.03  5015.6 1293.33
  5036.5 1302.23    5117 1306.65  5137.8 1307.37  5387.1 1321.04  5508.2 1326.67
#Mann= 13 ,-1 , 0
  4115.4      .1       0  4256.6     .05       0  4363.1      .1       0
  4466.7     .05       0  4680.3      .1       0  4723.1     .05       0
  4844.8      .1       0  4955.2     .16       0  4998.3     .07       0
  5004.3     .16       0    5117      .1       0  5137.8     .16       0
  5387.1     .05       0
Bank Sta=4998.3,5004.3
XS Rating Curve= 0 ,0
Exp/Cntr=0.3,0.1

Type RM Length L Ch R = 1 ,21183   ,30,30,30
BEGIN DESCRIPTION:
Mapping XS f2332b8e
END DESCRIPTION:
XS GIS Cut Line= 6
      2908798.64     10056435.78      2909393.21     10056646.26
      2909521.25     10056663.63      2909573.33     10056698.35
      2909657.97     10056776.47      2910083.34     10056924.05
#Sta/Elev= 30
  4122.7 1326.53  4217.1 1321.79  4228.6 1319.81  4278.9 1315.12  4334.7 1312.33
  4377.1 1308.41    4502 1304.94  4557.5 1302.23  4644.3 1300.56  4669.7  1301.3
  4755.3 1301.48  4865.1 1301.03  4939.7 1301.14  4966.9 1298.96  4974.3 1296.39
  4981.1 1295.43  4988.5 1292.89  4999.7 1291.93  5002.4 1291.43  5005.7 1291.93
  5016.8 1293.71  5023.6    1296    5031 1300.18  5045.2 1302.55  5191.6 1309.14
  5217.5 1311.37    5342 1318.19    5409 1320.81  5459.8 1323.44    5511 1324.92
#Mann= 10 ,-1 , 0
  4122.7      .1       0    4502     .05       0  4669.7      .1       0
  4755.3     .05       0  4865.1      .1       0  4981.1     .16       0
  4999.7     .07       0  5005.7     .16       0    5409     .05       0
  5459.8      .1       0
Bank Sta=4999.7,5005.7
XS Rating Curve= 0 ,0
Exp/Cntr=0.3,0.1

Type RM Length L Ch R = 1 ,21153   ,242,242,242
BEGIN DESCRIPTION:
Mapping XS 408ca68a
END DESCRIPTION:
XS GIS Cut Line= 6
      2908772.56     10056472.66      2909354.15     10056698.35
       2909488.7     10056694.01      2909582.01     10056746.09
      2909647.12     10056815.54      2910059.44     10056956.59
#Sta/Elev= 30
  4122.7 1324.97  4191.4  1323.2  4226.7 1319.17  4245.9 1318.52  4289.9 1314.75
  4335.6 1313.13  4365.5 1310.33  4444.5 1307.19  4461.6 1305.75  4504.5 1305.26
  4560.4 1302.51  4654.6 1299.56  4740.4 1298.64  4795.6 1299.26  4850.9 1298.73
  4969.9 1294.21  4975.6  1292.4  5002.1 1290.02  5004.8 1289.52  5008.1 1290.02
    5011 1290.23  5026.1 1291.08  5033.4 1293.52  5040.2 1297.58  5054.4 1301.72
    5248 1310.63  5285.5 1313.53  5348.6 1316.35  5440.5 1320.53    5519 1324.37
#Mann= 8 ,-1 , 0
  4122.7      .1       0  4560.4     .05       0  4795.6      .1       0
  5002.1     .07       0  5008.1      .1       0    5011     .16       0
  5348.6     .05       0  5440.5      .1       0
Bank Sta=5002.1,5008.1
XS Rating Curve= 0 ,0
Exp/Cntr=0.3,0.1

Type RM Length L Ch R = 1 ,20911   ,372,372,372
BEGIN DESCRIPTION:
Mapping XS 7ccc2781
END DESCRIPTION:
XS GIS Cut Line= 4
      2908738.26     10056617.62      2909286.87     10056839.84
      2909568.12     10056999.56      2910050.76     10057016.92
#Sta/Elev= 30
    4258 1318.92  4286.4 1317.39  4291.8 1316.36  4364.1 1314.22  4423.1 1311.21
  4441.6 1311.17  4476.7 1309.56  4571.1 1307.22  4668.2 1302.15  4691.2 1302.24
  4763.5 1297.68    4906 1294.69  4920.7  1293.7  4927.6  1293.4  4965.1 1290.58
  4970.8 1289.01  4986.7 1287.94    5001 1285.32  5004.2 1285.82  5008.3 1288.12
    5030 1291.63  5058.7 1293.39  5067.5 1294.78  5116.5 1296.12    5154  1298.1
  5223.7  1304.4  5323.8 1308.13  5488.6 1315.69  5553.9 1319.56  5656.3 1323.97
#Mann= 5 ,-1 , 0
    4258      .1       0  4571.1      .1       0  4920.7     .07       0
  5058.7      .1       0  5488.6     .05       0
Bank Sta=4927.6,5058.7
XS Rating Curve= 0 ,0
Exp/Cntr=0.3,0.1

Type RM Length L Ch R = 1 ,20539   ,303,303,303
BEGIN DESCRIPTION:
DEER CREEK 47.0
END DESCRIPTION:
XS GIS Cut Line= 4
      2908696.58     10056975.24      2909057.71     10057239.15
       2909533.4     10057266.92      2910109.82     10057141.92
#Sta/Elev= 30
  4320.7 1318.86  4371.9 1316.08    4399 1316.56  4428.3 1315.85    4443 1314.38
  4546.8 1312.36  4635.3  1310.1  4664.6 1307.81  4685.5 1307.34  4700.1 1305.28
  4714.8 1300.77  4750.3 1298.43    4765  1291.5  4767.6 1291.43  4770.9 1291.43
  4778.8 1288.03  4788.8 1285.25  4798.8 1284.63  5103.9 1283.97  5119.3 1286.21
  5129.4 1289.67  5149.4 1294.01  5159.4  1295.6  5244.5 1298.03  5284.3 1300.27
  5362.2 1307.17  5426.7 1308.74  5546.4 1313.85  5761.3 1323.46  5834.3 1325.62
#Mann= 5 ,-1 , 0
  4320.7     .05       0  4546.8      .1       0  4767.6     .05       0
  5149.4      .1       0  5546.4      .1       0
Bank Sta=4765,5149.4
XS Rating Curve= 0 ,0
Exp/Cntr=0.3,0.1

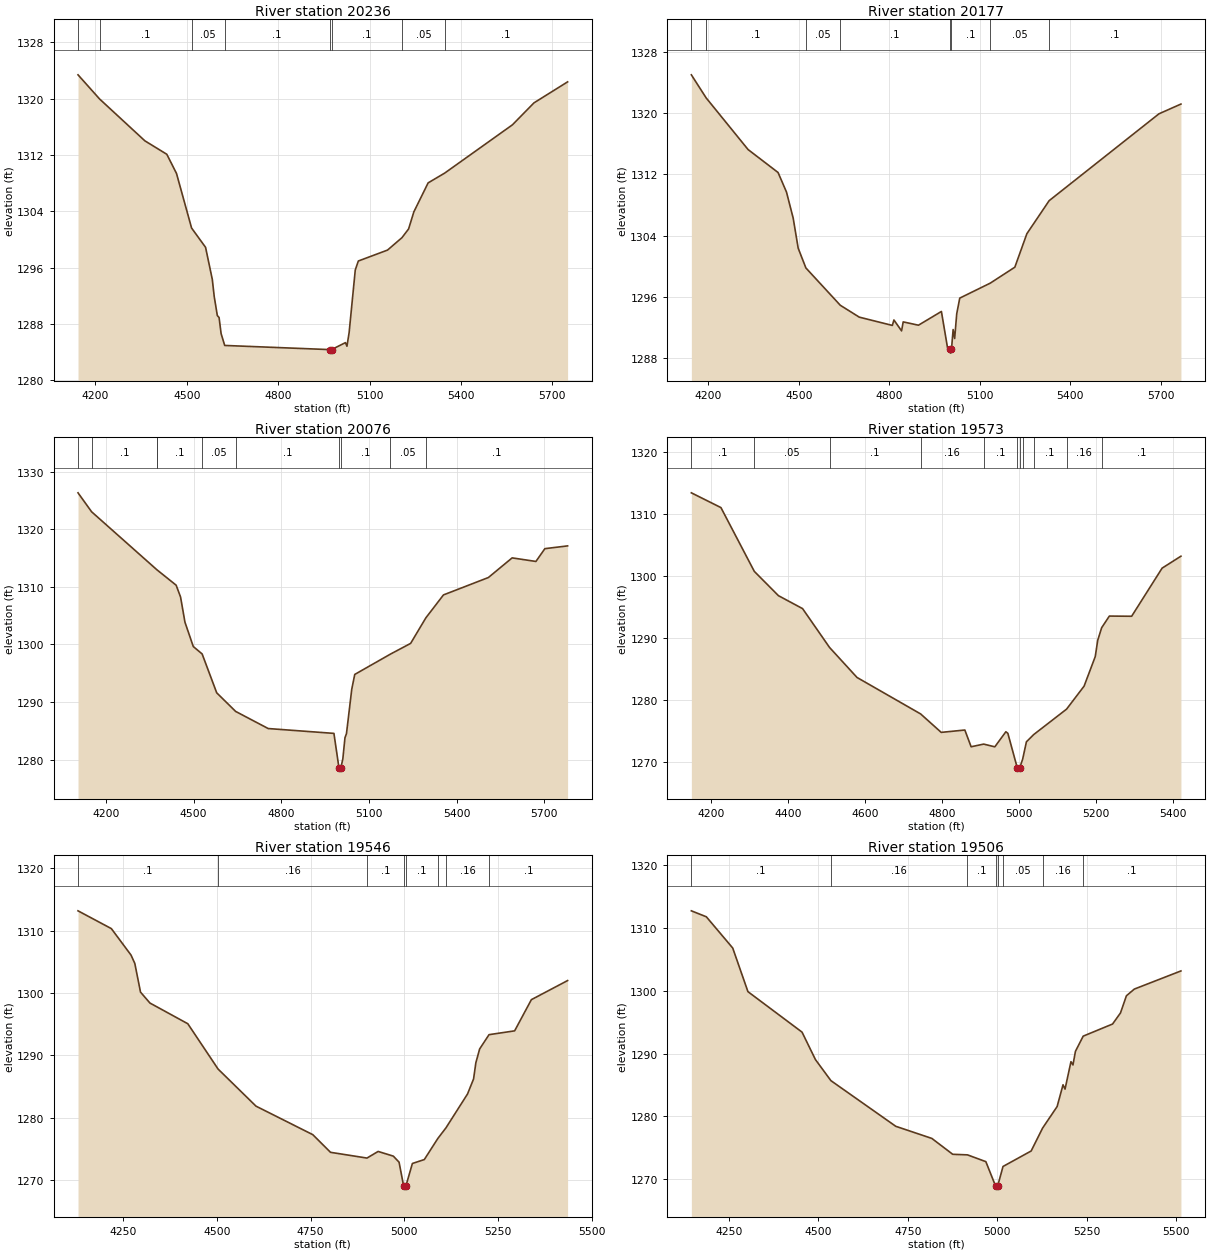
Type RM Length L Ch R = 1 ,20236   ,59,59,59
BEGIN DESCRIPTION:
DEER CREEK 46.0
END DESCRIPTION:
XS GIS Cut Line= 5
      2908651.49     10057136.39      2909090.69      10057363.8
      2909215.69     10057480.12      2909361.53     10057537.41
      2910137.54      10057421.1
#Sta/Elev= 30
  4143.1 1323.37  4213.9 1319.94  4362.5    1314  4434.5 1312.09  4466.3 1309.37
  4515.8 1301.62  4561.7 1298.88  4583.8 1294.33  4590.1 1291.89  4600.3 1289.19
    4606 1288.92  4612.7 1286.63  4624.5 1284.95  4969.1 1284.36  4971.9 1283.86
  4975.1 1284.36  5020.7 1285.35  5025.7 1284.84  5032.8 1286.77    5053 1295.67
  5063.1 1296.94  5158.9 1298.49  5206.4 1300.26    5228 1301.49  5245.2 1303.91
  5292.1 1308.03  5346.5 1309.42  5568.7 1316.27  5639.5 1319.39  5749.8 1322.37
#Mann= 8 ,-1 , 0
  4143.1     .05       0  4213.9      .1       0  4515.8     .05       0
  4624.5      .1       0  4969.1     .07       0  4975.1      .1       0
  5206.4     .05       0  5346.5      .1       0
Bank Sta=4969.1,4975.1
XS Rating Curve= 0 ,0
Exp/Cntr=0.3,0.1

Type RM Length L Ch R = 1 ,20177   ,101,101,101
BEGIN DESCRIPTION:
DEER CREEK 45.0
END DESCRIPTION:
XS GIS Cut Line= 5
      2908641.05     10057216.23      2909035.14     10057417.62
      2909189.65     10057539.15      2909352.85     10057598.17
      2910151.44     10057466.23
#Sta/Elev= 30
  4144.1 1324.96  4193.2 1321.95  4332.1 1315.22  4431.4 1312.23  4459.3 1309.68
  4481.5 1306.28  4498.1 1302.36  4523.6 1299.79  4637.5 1294.93  4700.4 1293.38
    4810  1292.3  4815.3 1293.01  4840.6 1291.59    4846 1292.76  4896.6 1292.33
  4972.6 1294.12  4992.9 1289.38    5000 1289.19  5002.8 1288.69    5006 1289.19
  5011.4 1291.76  5016.5  1290.6  5023.3 1293.81  5033.4 1295.86  5134.4 1297.81
  5215.9 1299.89  5255.7 1304.25  5329.6 1308.56  5693.4 1319.88  5766.2 1321.15
#Mann= 8 ,-1 , 0
  4144.1     .05       0  4193.2      .1       0  4523.6     .05       0
  4637.5      .1       0    5000     .07       0    5006      .1       0
  5134.4     .05       0  5329.6      .1       0
Bank Sta=5000,5006
XS Rating Curve= 0 ,0
Exp/Cntr=0.3,0.1

Type RM Length L Ch R = 1 ,20076   ,503,503,503
BEGIN DESCRIPTION:
DEER CREEK 44.0
END DESCRIPTION:
XS GIS Cut Line= 4
      2908618.44     10057277.67      2909087.38     10057584.45
      2909356.16     10057699.85      2910165.15     10057554.09
#Sta/Elev= 30
  4104.5 1326.32    4151 1323.03  4374.7 1312.95  4375.5 1312.92  4440.2 1310.29
  4455.3 1308.24  4470.4 1303.86  4498.9 1299.64  4529.1 1298.36    4579 1291.61
  4643.8 1288.38  4755.2 1285.41    4980 1284.57  4997.4 1278.52  5000.1 1278.02
  5003.4 1278.52  5010.5 1280.16  5017.8 1283.83  5022.9 1284.52    5041 1292.24
  5051.2  1294.8  5172.7 1298.31  5242.4 1300.19  5294.6 1304.63  5354.7  1308.6
  5508.4 1311.62  5589.7 1315.03    5671 1314.41  5701.7 1316.63  5779.4 1317.11
#Mann= 10 ,-1 , 0
  4104.5     .05       0    4151      .1       0  4374.7     .05       0
  4375.5      .1       0  4529.1     .05       0  4643.8      .1       0
  4997.4     .07       0  5003.4      .1       0  5172.7     .05       0
  5294.6      .1       0
Bank Sta=4997.4,5003.4
XS Rating Curve= 0 ,0
Exp/Cntr=0.3,0.1

Type RM Length L Ch R = 1 ,19573   ,27,27,27
BEGIN DESCRIPTION:
Mapping XS 55eb287c
END DESCRIPTION:
XS GIS Cut Line= 6
      2908592.38     10058066.92      2909236.53      10058157.2
      2909311.18     10058186.72      2909382.36     10058183.24
       2909470.9     10058160.67      2909792.06     10057961.04
#Sta/Elev= 30
  4149.5 1313.42  4226.3 1311.04    4313 1300.75  4375.7 1296.83  4438.4 1294.74
  4508.5 1288.47  4579.7 1283.64  4745.1 1277.75  4798.4 1274.78  4859.8 1275.16
  4876.1 1272.46  4908.7 1272.89  4937.6 1272.45  4966.3 1274.88  4971.5 1274.63
  4996.1 1269.03  4998.8 1268.53  5002.1 1269.03  5009.9 1270.45  5019.7 1273.26
  5038.7 1274.43    5124 1278.53  5169.5 1282.24  5198.5 1287.01  5204.8 1289.61
  5215.1 1291.66  5235.1 1293.54    5293 1293.51  5372.1 1301.27    5421  1303.2
#Mann= 11 ,-1 , 0
  4149.5      .1       0    4313     .05       0  4508.5      .1       0
  4745.1     .16       0  4908.7      .1       0  4996.1     .07       0
  5002.1      .1       0  5009.9     .05       0  5038.7      .1       0
    5124     .16       0  5215.1      .1       0
Bank Sta=4996.1,5002.1
XS Rating Curve= 0 ,0
Exp/Cntr=0.3,0.1

Type RM Length L Ch R = 1 ,19546   ,40,40,40
BEGIN DESCRIPTION:
Mapping XS a3a4022e
END DESCRIPTION:
XS GIS Cut Line= 6
      2908578.56     10058096.44      2909246.94     10058186.72
      2909316.39     10058209.29       2909384.1     10058205.81
       2909470.9     10058190.19      2909823.32     10057999.22
#Sta/Elev= 30
  4130.5 1313.19  4219.3 1310.34  4271.7  1306.1  4281.8 1304.76    4297 1300.16
  4322.1 1298.41    4423 1295.09  4503.6 1287.83  4604.7 1281.88    4756 1277.31
  4803.2 1274.48  4900.3 1273.56  4930.1 1274.62  4970.5 1273.87  4985.8  1272.9
    4998 1269.08  5000.8 1268.58    5004 1269.08  5021.3 1272.69  5053.1 1273.32
  5089.1  1276.7  5110.6 1278.39  5168.2 1283.83  5184.3 1286.24  5190.4 1288.84
  5200.5 1291.05  5225.5 1293.34  5293.7 1293.95  5338.3 1298.95  5434.8 1302.01
#Mann= 8 ,-1 , 0
  4130.5      .1       0  4503.6     .16       0  4900.3      .1       0
    4998     .07       0    5004      .1       0  5089.1      .1       0
  5110.6     .16       0  5225.5      .1       0
Bank Sta=4998,5004
XS Rating Curve= 0 ,0
Exp/Cntr=0.3,0.1

Type RM Length L Ch R = 1 ,19506   ,314,314,314
BEGIN DESCRIPTION:
DEER CREEK 43.0
END DESCRIPTION:
XS GIS Cut Line= 4
      2908571.63     10058143.32      2909312.92     10058240.54
      2909457.01     10058228.38      2909880.62     10058009.63
#Sta/Elev= 30
    4145 1312.76  4186.9 1311.81  4260.7 1306.83  4303.2 1299.88  4454.5 1293.43
    4492 1289.05  4535.2  1285.7  4716.7 1278.42  4817.5 1276.49  4875.9 1273.96
  4917.1 1273.87  4968.5 1272.79  4995.6 1268.91  4998.3 1268.41  5001.6 1268.91
  5016.5 1272.02  5095.2 1274.49  5127.1 1278.13  5167.8 1281.57  5184.3 1285.04
  5189.9 1284.35  5206.5 1288.72  5212.1  1288.2    5219 1290.37  5240.7 1292.79
  5322.8 1294.72    5345 1296.49  5361.5 1299.22  5383.7 1300.29    5514 1303.18
#Mann= 8 ,-1 , 0
    4145      .1       0  4535.2     .16       0  4917.1      .1       0
  4995.6     .07       0  5001.6      .1       0  5016.5     .05       0
  5127.1     .16       0  5240.7      .1       0
Bank Sta=4995.6,5001.6
XS Rating Curve= 0 ,0
Exp/Cntr=0.3,0.1

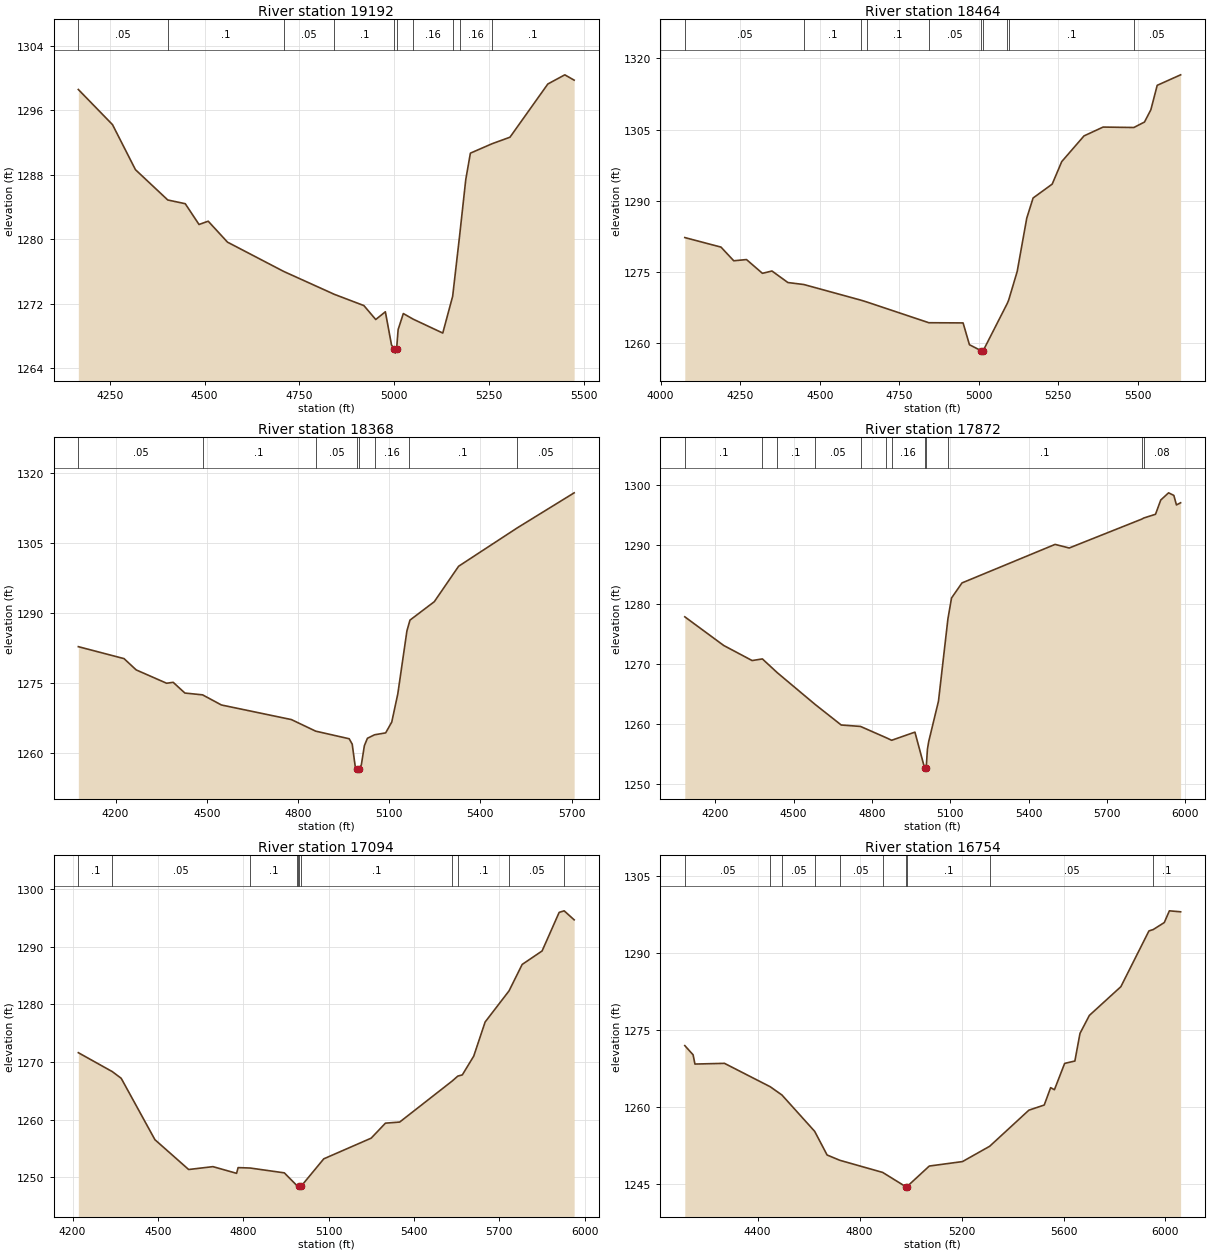
Type RM Length L Ch R = 1 ,19192   ,728,728,728
BEGIN DESCRIPTION:
DEER CREEK 42.0
END DESCRIPTION:
XS GIS Cut Line= 4
      2908659.24     10058522.65       2909177.5     10058598.17
      2909745.21     10058434.11      2909854.03     10058273.48
#Sta/Elev= 30
  4166.5 1298.56  4256.7  1294.2  4317.3 1288.61  4402.6 1284.85  4448.7 1284.39
  4485.1 1281.81  4509.3 1282.22  4560.2 1279.62  4708.4 1275.99  4842.5 1273.14
  4920.2 1271.75  4951.5 1270.02  4976.9 1270.98  4993.1 1266.87  5000.5 1266.35
  5003.3 1265.85  5006.5 1266.35  5010.6 1268.77  5024.3 1270.76  5050.5 1270.06
  5128.4 1268.34  5154.5  1272.9  5172.8 1280.39  5189.1 1287.38  5201.3 1290.66
  5258.5 1291.83  5305.8 1292.64  5405.7 1299.24  5450.5 1300.38  5475.2 1299.72
#Mann= 10 ,-1 , 0
  4166.5     .05       0  4402.6      .1       0  4708.4     .05       0
  4842.5      .1       0  5000.5     .07       0  5006.5      .1       0
  5050.5     .16       0  5154.5      .1       0  5172.8     .16       0
  5258.5      .1       0
Bank Sta=5000.5,5006.5
XS Rating Curve= 0 ,0
Exp/Cntr=0.3,0.1

Type RM Length L Ch R = 1 ,18464   ,96,96,96
BEGIN DESCRIPTION:
DEER CREEK 41.0
END DESCRIPTION:
XS GIS Cut Line= 3
      2908984.81     10058829.95      2909713.96     10058869.01
      2910542.06     10058887.24
#Sta/Elev= 30
    4076 1282.27  4189.8 1280.26  4229.9 1277.38  4269.9 1277.64    4320 1274.74
    4350 1275.23  4400.1  1272.8  4450.4 1272.38  4629.6 1269.09  4648.9 1268.69
  4843.1 1264.34  4950.7  1264.3  4970.7 1259.71  5007.8 1258.44  5010.5 1257.94
  5013.8 1258.44  5089.9 1268.44  5094.1 1269.13  5120.8 1275.13  5150.8 1286.34
  5170.8  1290.6  5230.8 1293.52  5260.8 1298.26  5330.8 1303.67  5390.8 1305.53
  5487.5 1305.44  5520.9 1306.59  5540.9 1309.17  5560.9 1314.32  5634.5 1316.53
#Mann= 10 ,-1 , 0
    4076     .05       0  4450.4      .1       0  4629.6     .05       0
  4648.9      .1       0  4843.1     .05       0  5007.8    .035       0
  5013.8     .05       0  5089.9     .16       0  5094.1      .1       0
  5487.5     .05       0
Bank Sta=5007.8,5013.8
XS Rating Curve= 0 ,0
Exp/Cntr=0.3,0.1

Type RM Length L Ch R = 1 ,18368   ,496,496,496
BEGIN DESCRIPTION:
DEER CREEK 40.0
END DESCRIPTION:
XS GIS Cut Line= 3
      2908948.37      10058923.7      2909695.73     10058960.15
      2910578.57     10058962.76
#Sta/Elev= 30
  4077.4 1282.75  4227.7 1280.19  4267.7 1277.77  4367.8 1274.91  4389.4 1275.11
  4427.9 1272.81  4486.2 1272.42  4548.1 1270.25  4778.3 1267.12  4858.2 1264.64
  4968.4 1263.01  4978.4 1261.85  4988.4 1257.01  4995.4 1256.57  4998.1 1256.07
  5001.4 1256.57  5008.4 1257.41  5018.4 1261.53  5028.4 1263.11  5051.8 1263.86
  5088.4 1264.27  5108.4 1266.58  5128.4 1272.65  5158.4 1286.15  5163.6 1287.34
  5168.4 1288.44  5248.4 1292.39  5328.4 1299.99  5521.7 1308.23  5708.5 1315.73
#Mann= 8 ,-1 , 0
  4077.4     .05       0  4486.2      .1       0  4858.2     .05       0
  4995.4    .035       0  5001.4     .05       0  5051.8     .16       0
  5163.6      .1       0  5521.7     .05       0
Bank Sta=4995.4,5001.4
XS Rating Curve= 0 ,0
Exp/Cntr=0.3,0.1

Type RM Length L Ch R = 1 ,17872   ,778,778,778
BEGIN DESCRIPTION:
DEER CREEK 39.0
END DESCRIPTION:
XS GIS Cut Line= 3
      2909020.02       10059300.      2909723.12     10059435.41
      2910904.45     10059508.27
#Sta/Elev= 30
  4083.1 1277.93  4232.1 1273.15    4341 1270.63  4380.4  1270.9  4437.8 1268.59
  4581.7 1263.33  4682.4 1259.87  4756.4 1259.63  4855.5 1257.73  4875.6 1257.32
  4964.8 1258.68  5001.9 1252.67  5004.6 1252.17  5007.9 1252.67  5012.7 1255.83
  5017.7 1257.13    5055 1263.85  5091.2  1277.6    5105 1281.07  5145.1 1283.59
  5501.8 1290.02  5555.9 1289.42  5833.7 1294.24  5841.1 1294.42  5886.5 1295.05
  5906.6 1297.43  5936.6 1298.63  5956.7  1298.2  5966.7 1296.61  5982.7 1296.97
#Mann= 12 ,-1 , 0
  4083.1      .1       0  4380.4     .05       0  4437.8      .1       0
  4581.7     .05       0  4756.4      .1       0  4855.5     .05       0
  4875.6     .16       0  5001.9     .07       0  5007.9     .16       0
  5091.2      .1       0  5833.7     .05       0  5841.1     .08       0
Bank Sta=5001.9,5007.9
XS Rating Curve= 0 ,0
Exp/Cntr=0.3,0.1

Type RM Length L Ch R = 1 ,17094   ,340,340,340
BEGIN DESCRIPTION:
DEER CREEK 38.0
END DESCRIPTION:
XS GIS Cut Line= 4
      2908988.75       10059800.      2909530.41     10060018.75
      2909936.66     10060138.54      2910671.05       10060175.
#Sta/Elev= 30
  4220.1 1271.64  4339.7 1268.35  4370.8  1267.2  4489.4 1256.55    4608 1251.38
  4693.2 1251.88  4776.4 1250.72  4781.8 1251.71  4823.9 1251.64  4944.3  1250.8
  4988.7 1248.58  4991.8 1248.53  4997.3 1248.48  5000.1 1247.98  5003.3 1248.48
  5082.8 1253.23  5249.6 1256.82  5299.7 1259.42  5349.8 1259.61  5533.7  1266.7
  5554.1 1267.58    5570 1267.79  5610.1 1271.05  5650.1 1276.96  5734.2 1282.36
  5780.3 1286.94  5850.4 1289.28  5910.4 1295.97    5928 1296.24  5963.1 1294.68
#Mann= 11 ,-1 , 0
  4220.1      .1       0  4339.7     .05       0  4823.9      .1       0
  4988.7     .05       0  4991.8      .1       0  4997.3     .07       0
  5003.3      .1       0  5533.7     .05       0  5554.1      .1       0
  5734.2     .05       0    5928      .1       0
Bank Sta=4997.3,5003.3
XS Rating Curve= 0 ,0
Exp/Cntr=0.3,0.1

Type RM Length L Ch R = 1 ,16754   ,144,144,144
BEGIN DESCRIPTION:
Mapping XS 18d548ea
END DESCRIPTION:
XS GIS Cut Line= 3
      2908881.98     10059885.95       2909147.6     10060318.23
      2910582.47     10060411.98
#Sta/Elev= 30
  4114.2 1271.97  4146.8 1270.18    4154 1268.38  4269.9 1268.52  4449.3 1263.97
  4495.4 1262.36  4623.8 1255.29  4672.5 1250.69  4722.4 1249.66  4890.6  1247.3
  4980.2 1244.55    4983 1244.05  4986.2 1244.55  5073.4 1248.54  5203.7 1249.41
  5310.4 1252.39  5464.2 1259.41  5524.4 1260.41  5549.5 1263.79  5564.4 1263.39
  5604.5 1268.51  5644.6 1268.97  5664.7 1274.35  5701.4 1277.84    5825 1283.43
  5935.2 1294.28    5952 1294.55  5995.4 1295.91  6015.4 1298.19  6059.5    1298
#Mann= 10 ,-1 , 0
  4114.2     .05       0  4449.3      .1       0  4495.4     .05       0
  4623.8      .1       0  4722.4     .05       0  4890.6      .1       0
  4980.2     .07       0  4986.2      .1       0  5310.4     .05       0
    5952      .1       0
Bank Sta=4980.2,4986.2
XS Rating Curve= 0 ,0
Exp/Cntr=0.3,0.1

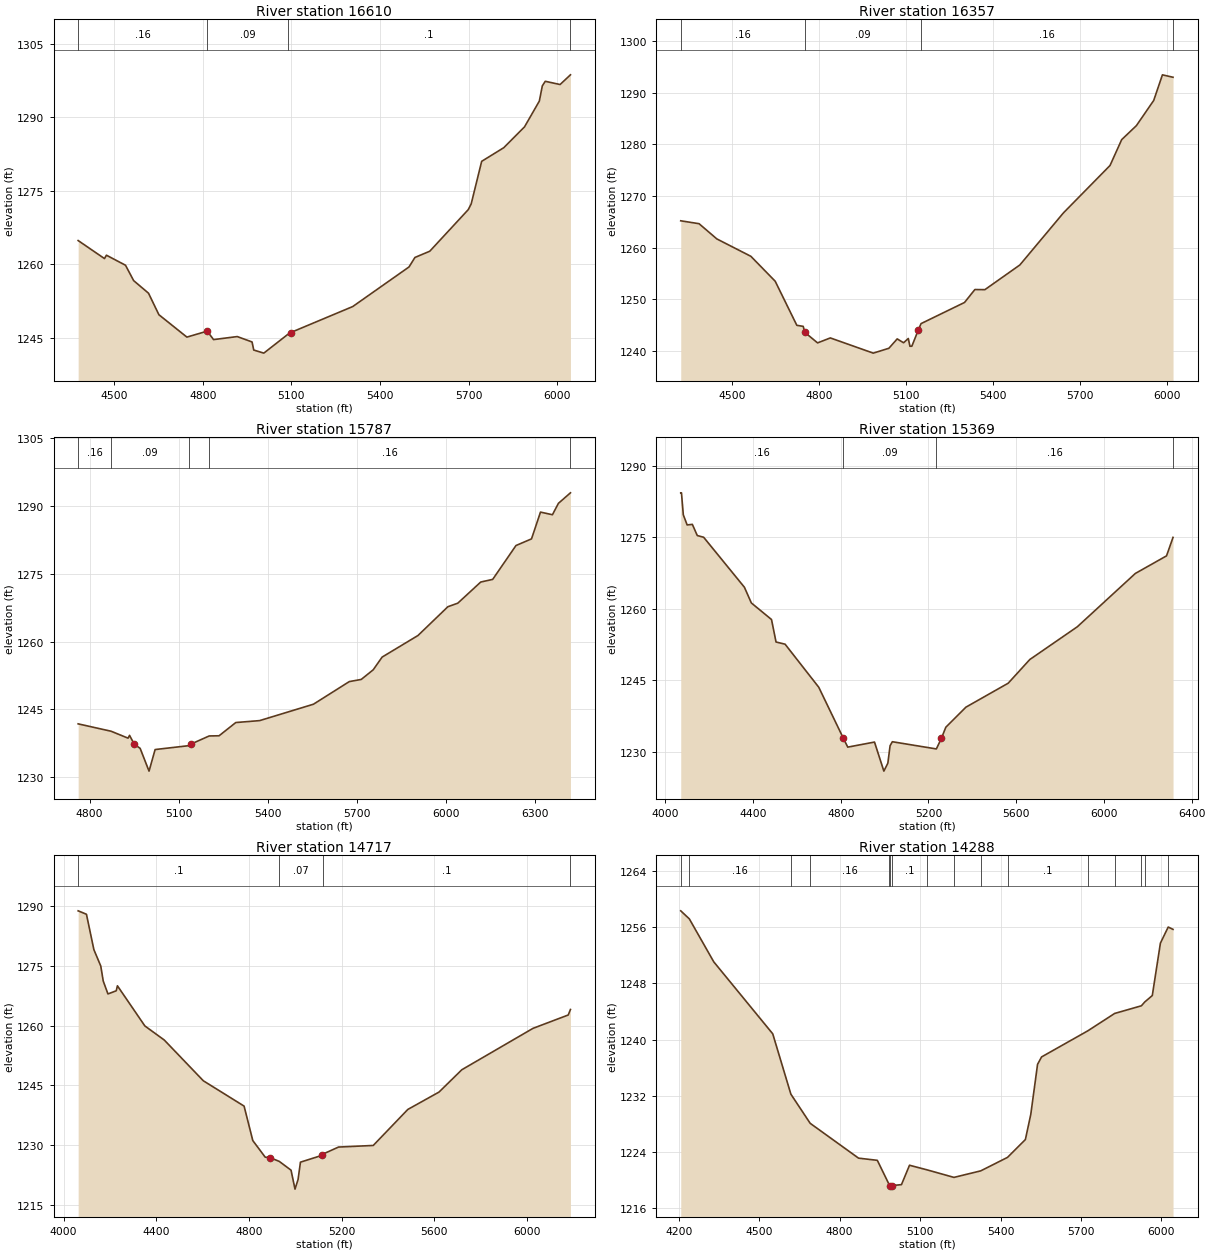
Type RM Length L Ch R = 1 ,16610   ,253,253,253
BEGIN DESCRIPTION:
DEER CREEK 37.0
END DESCRIPTION:
XS GIS Cut Line= 3
       2908953.6     10060203.11       2909151.5     10060429.66
      2910513.51     10060518.21
#Sta/Elev= 30
  4378.6 1264.81  4467.7 1261.13  4474.3 1261.82  4538.8 1259.77  4566.4 1256.63
  4616.7 1254.06  4651.8 1249.67  4746.5  1245.1  4815.4 1246.32  4836.7 1244.59
  4916.9 1245.21    4967 1244.11  4972.7 1242.46  5006.8 1241.83  5087.2 1245.62
  5097.3 1246.02  5307.7 1251.34  5498.1 1259.42  5518.1 1261.36  5568.3 1262.63
  5698.5 1271.12  5708.5  1272.3  5743.9 1280.98  5818.8 1283.77  5888.9 1288.02
    5939 1293.28  5949.1 1296.38  5959.1 1297.32  6009.2 1296.66  6044.3 1298.64
#Mann= 4 ,-1 , 0
  4378.6     .16       0  4815.4     .09       0  5087.2      .1       0
  6044.3      .1       0
Bank Sta=4815.4,5097.3
XS Rating Curve= 0 ,0
Exp/Cntr=0.3,0.1

Type RM Length L Ch R = 1 ,16357   ,570,570,570
BEGIN DESCRIPTION:
DEER CREEK 36.0
END DESCRIPTION:
XS GIS Cut Line= 4
       2908896.3     10060190.08      2909052.54     10060502.58
      2909534.31     10060757.79      2910334.94     10060830.57
#Sta/Elev= 30
  4321.8 1265.19    4385 1264.63  4446.5 1261.68  4563.8 1258.32  4647.7  1253.5
  4722.3 1244.97  4744.3 1244.77  4749.9 1243.61  4793.9 1241.57  4837.9 1242.53
    4986 1239.59    5040 1240.53  5068.6 1242.34  5090.6  1241.6  5106.9 1242.42
  5112.6 1240.92  5119.2 1240.93  5141.9 1244.12  5150.9  1245.3  5300.9 1249.39
  5336.6 1251.89  5371.2 1251.87  5491.7 1256.64  5642.3 1266.73  5802.9 1275.89
  5843.1 1280.89  5893.9  1283.6  5953.6 1288.47  5983.7 1293.43  6020.3 1292.96
#Mann= 4 ,-1 , 0
  4321.8     .16       0  4749.9     .09       0  5150.9     .16       0
  6020.3     .05       0
Bank Sta=4749.9,5141.9
XS Rating Curve= 0 ,0
Exp/Cntr=0.3,0.1

Type RM Length L Ch R = 1 ,15787   ,418,418,418
BEGIN DESCRIPTION:
DEER CREEK 35.0
END DESCRIPTION:
XS GIS Cut Line= 3
      2908829.08     10060722.58      2908832.38     10060854.72
       2910348.8      10061006.7
#Sta/Elev= 30
  4761.5 1241.79  4872.7 1240.15  4929.4 1238.62  4934.4 1239.24    4950 1237.31
  4970.1 1236.36    5000 1231.32  5020.4  1236.1  5135.2 1236.97    5141 1237.31
  5202.4 1239.11  5235.6 1239.15  5291.8 1242.08  5372.2 1242.51  5553.1 1246.14
  5673.7 1251.15  5713.9 1251.63  5754.1 1253.76  5784.2 1256.58  5904.8 1261.36
  6005.3 1267.73  6038.7 1268.52  6115.9  1273.2  6156.1 1273.79  6234.5 1281.29
  6286.7 1282.76  6316.9 1288.69  6357.1 1288.11  6377.2 1290.63  6417.7 1292.96
#Mann= 5 ,-1 , 0
  4761.5     .16       0  4872.7     .09       0  5135.2      .1       0
  5202.4     .16       0  6417.7      .1       0
Bank Sta=4950,5141
XS Rating Curve= 0 ,0
Exp/Cntr=0.3,0.1

Type RM Length L Ch R = 1 ,15369   ,652,652,652
BEGIN DESCRIPTION:
DEER CREEK 34.0
END DESCRIPTION:
XS GIS Cut Line= 3
       2907937.1     10061326.36      2908470.95     10061191.82
      2910137.64     10061495.64
#Sta/Elev= 30
  4070.4 1284.32  4073.7 1284.32  4082.1 1279.71  4099.6 1277.59  4123.4 1277.71
  4145.8 1275.37  4174.9 1275.01  4360.6 1264.54  4392.4 1261.24  4484.3 1257.77
  4504.9 1253.06  4546.2  1252.6  4699.7 1243.58  4811.6 1232.91  4831.9 1231.03
  4953.9 1232.09  4996.6    1226  5014.8 1227.67    5025 1231.33  5035.2 1232.16
  5235.9 1230.65  5258.8 1232.85  5279.1  1235.2  5370.6  1239.4  5563.7 1244.43
  5661.8 1249.38  5878.9 1256.26  6143.1 1267.42  6285.4 1271.11  6315.1 1274.98
#Mann= 4 ,-1 , 0
  4070.4     .16       0  4811.6     .09       0  5235.9     .16       0
  6315.1      .1       0
Bank Sta=4811.6,5258.8
XS Rating Curve= 0 ,0
Exp/Cntr=0.3,0.1

Type RM Length L Ch R = 1 ,14717   ,429,429,429
BEGIN DESCRIPTION:
DEER CREEK 32.0
END DESCRIPTION:
XS GIS Cut Line= 4
      2907941.47     10061812.48      2908614.18     10061920.98
      2909577.72     10061760.39       2910037.8     10061838.52
#Sta/Elev= 30
  4062.8 1288.76  4098.6  1287.9  4130.7 1279.02  4160.4 1274.92  4171.2 1271.12
  4191.4 1267.92  4227.3 1268.71  4232.3 1269.96  4350.8 1259.89  4434.5 1256.36
  4603.1 1246.14    4779 1239.79  4816.6 1231.15  4870.2 1226.98  4890.5 1226.89
    4931 1225.92  4981.7 1223.72  4998.8 1218.97  5012.1 1221.41  5022.3 1225.73
  5113.5 1227.41  5120.7 1227.79  5186.6 1229.52  5336.5 1229.92  5485.7 1238.95
  5620.4 1243.31  5718.9 1248.91  6026.1 1259.29  6178.2 1262.64  6187.7 1264.02
#Mann= 4 ,-1 , 0
  4062.8      .1       0    4931     .07       0  5120.7      .1       0
  6187.7      .1       0
Bank Sta=4890.5,5113.5
XS Rating Curve= 0 ,0
Exp/Cntr=0.3,0.1

Type RM Length L Ch R = 1 ,14288   ,792,792,792
BEGIN DESCRIPTION:
DEER CREEK 31.0
END DESCRIPTION:
XS GIS Cut Line= 3
      2908145.38     10062289.91      2909139.35     10062298.59
      2909975.23     10062198.97
#Sta/Elev= 30
  4207.3 1258.34  4239.4 1257.19  4330.4 1251.08  4550.4 1240.83    4618 1232.24
    4690 1228.09  4870.4 1223.13  4940.4 1222.82  4985.1 1219.32  4987.4 1219.22
  4990.2 1218.72  4993.4 1219.22  5030.4 1219.36  5060.4 1222.12  5127.2 1221.45
  5226.1 1220.39    5326 1221.32  5425.9 1223.24  5492.5 1225.78  5512.6 1229.35
  5537.9 1236.49  5552.9 1237.54  5725.5 1241.26  5825.4 1243.73  5925.1 1244.82
  5937.8 1245.37  5965.8 1246.28    5996 1253.74  6025.1 1256.03  6043.1  1255.7
#Mann= 16 ,-1 , 0
  4207.3      .1       0  4239.4     .16       0    4618      .1       0
    4690     .16       0  4985.1      .1       0  4987.4     .07       0
  4993.4      .1       0  5127.2     .05       0  5226.1      .1       0
    5326     .05       0  5425.9      .1       0  5725.5     .16       0
  5825.4     .05       0  5925.1      .1       0  5937.8     .05       0
  6025.1      .1       0
Bank Sta=4987.4,4993.4
XS Rating Curve= 0 ,0
Exp/Cntr=0.3,0.1