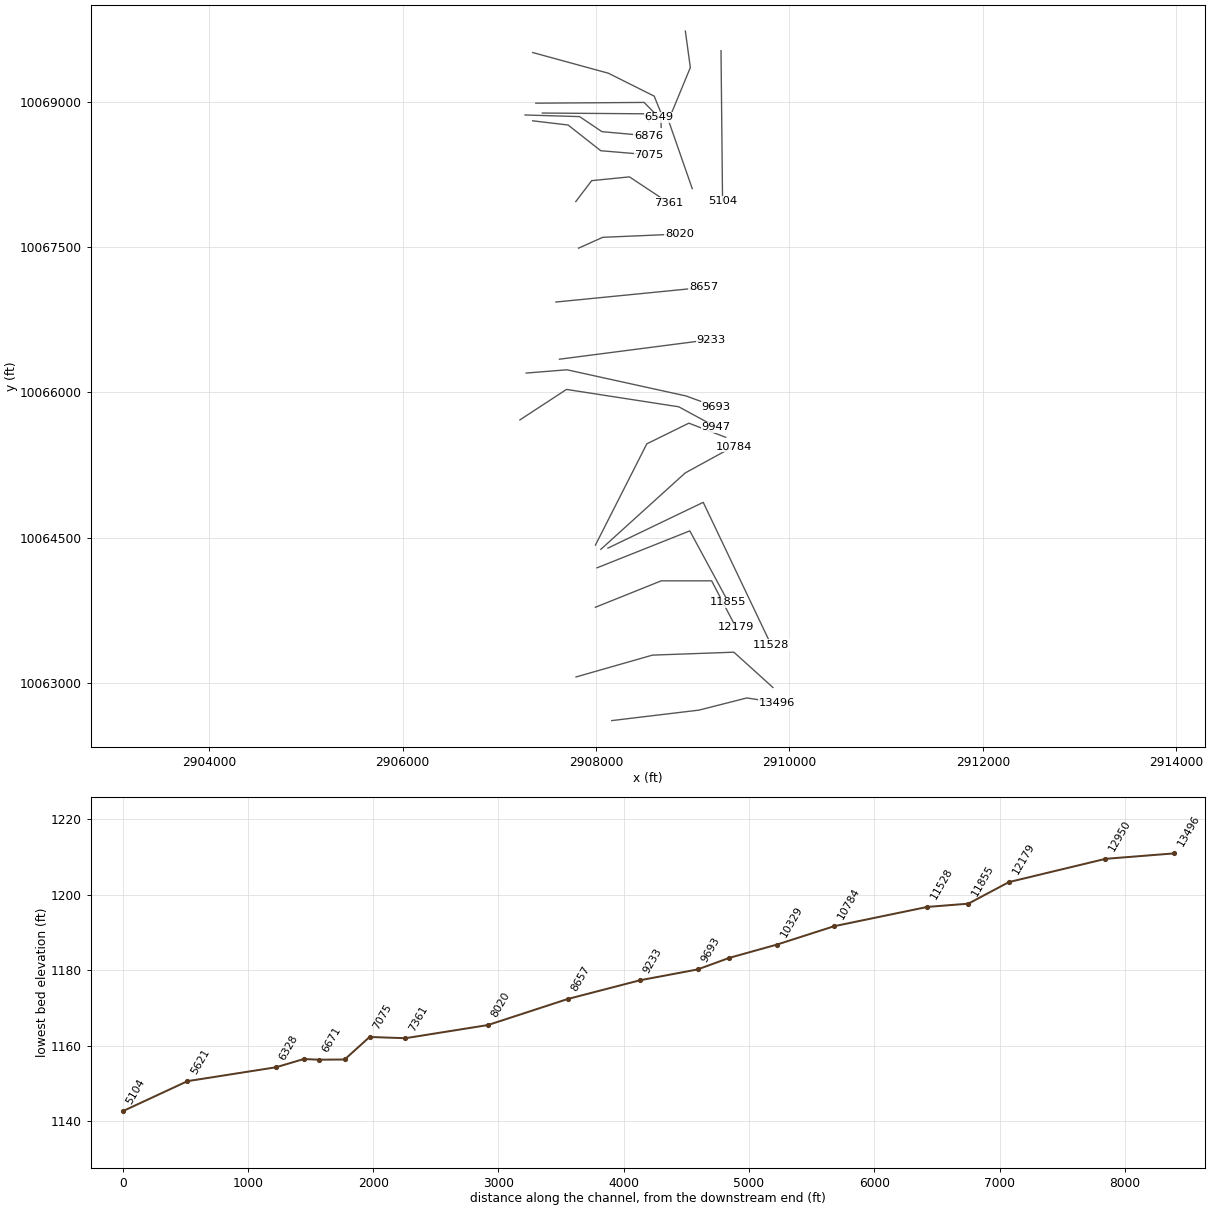
HEC-RAS study DEER CREEK.prj: DEER CREEK Base Level Engineering

--- DEER CREEK.g01 (geometry) --- (continued)

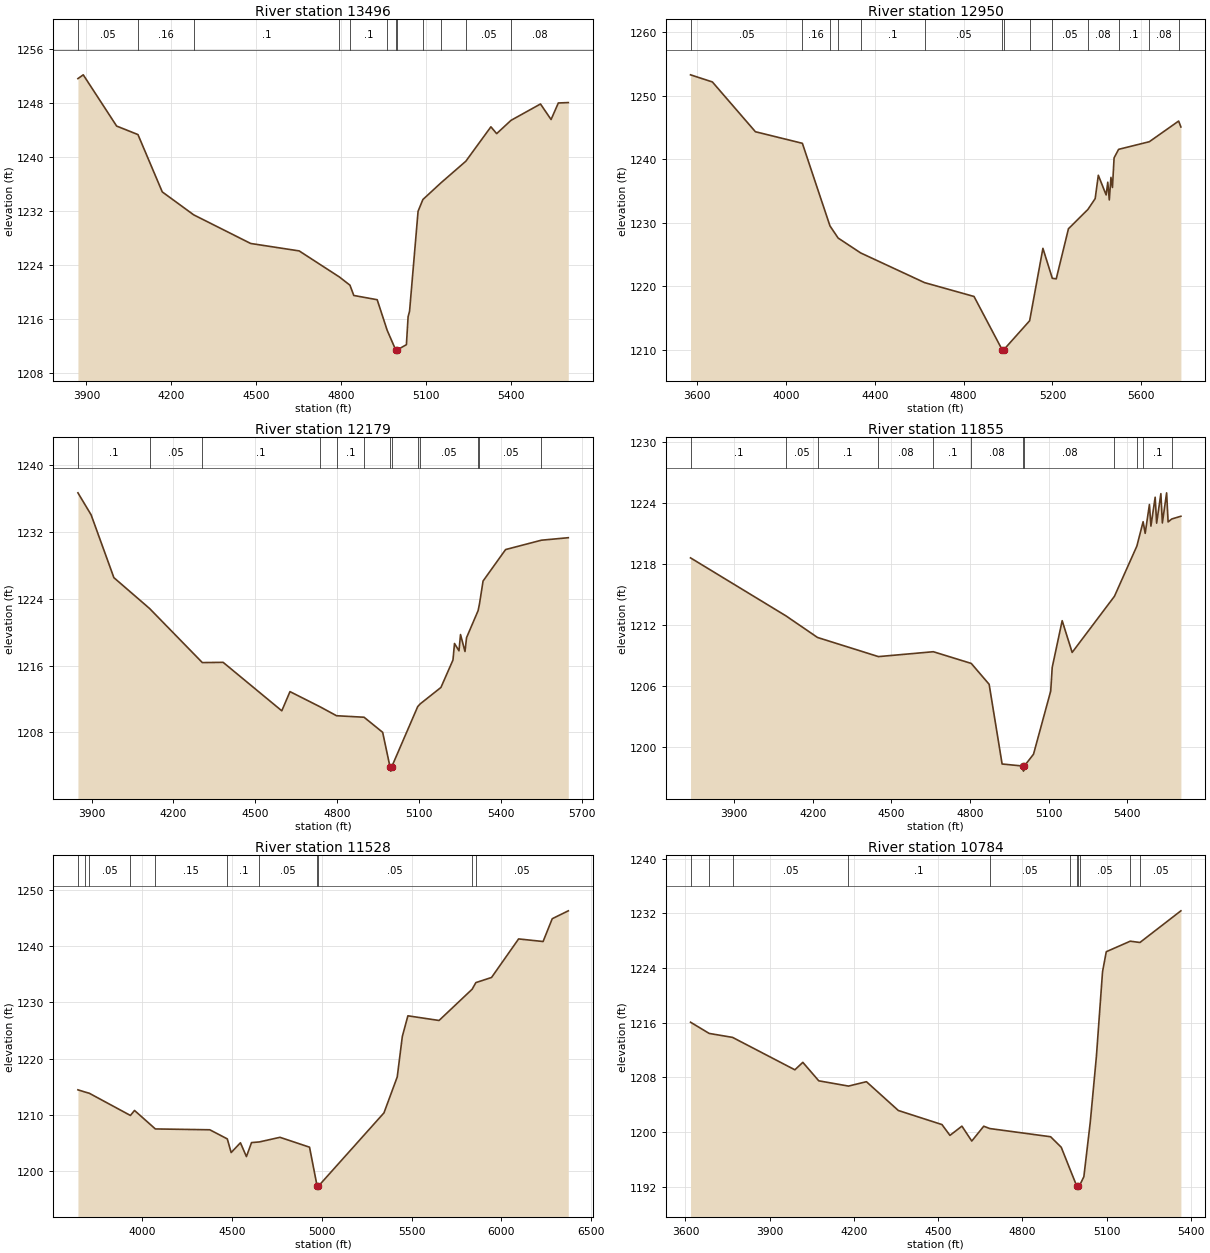
Type RM Length L Ch R = 1 ,13496   ,546,546,546
BEGIN DESCRIPTION:
DEER CREEK 30.0
END DESCRIPTION:
XS GIS Cut Line= 4
      2908162.75     10062606.74      2909065.56     10062715.25
      2909560.36     10062841.12      2909868.51     10062793.38
#Sta/Elev= 30
  3869.9 1251.61  3888.7 1252.17  4006.6 1244.58  4081.9 1243.32  4167.7 1234.83
  4278.8 1231.43    4480 1227.19  4651.2 1226.09  4793.2 1222.23  4830.6 1221.01
  4844.1 1219.49  4926.7 1218.86  4962.1 1214.32  4991.9 1211.45  4994.7 1210.95
  4997.9 1211.45  5029.9  1212.2  5035.9 1216.35    5041 1217.14  5071.1 1231.96
  5088.1  1233.7  5151.9 1236.17  5239.7 1239.37  5328.3 1244.47  5348.6 1243.46
  5399.4 1245.43  5503.4 1247.85  5540.8 1245.55  5566.4    1248  5601.6 1248.06
#Mann= 12 ,-1 , 0
  3869.9     .05       0  4081.9     .16       0  4278.8      .1       0
  4793.2     .05       0  4830.6      .1       0  4962.1     .16       0
  4991.9     .07       0  4997.9     .16       0  5088.1     .05       0
  5151.9     .16       0  5239.7     .05       0  5399.4     .08       0
Bank Sta=4991.9,4997.9
XS Rating Curve= 0 ,0
Exp/Cntr=0.3,0.1

Type RM Length L Ch R = 1 ,12950   ,771,771,771
BEGIN DESCRIPTION:
DEER CREEK 28.0
END DESCRIPTION:
XS GIS Cut Line= 4
      2907793.88     10063058.14      2908583.79     10063283.83
      2909425.81     10063314.21      2909829.45     10062949.63
#Sta/Elev= 30
  3570.2 1253.28  3668.6 1252.16  3862.3 1244.33  4073.8 1242.51    4198 1229.52
  4234.8 1227.61  4336.2 1225.27  4623.9  1220.6  4846.7 1218.42  4973.8 1210.01
  4976.5 1209.51  4979.8 1210.01  5097.1  1214.6  5156.9 1225.99  5199.2 1221.28
  5216.9 1221.19  5271.9 1229.07  5359.5 1232.11  5392.2 1233.81  5406.4 1237.48
  5441.6 1234.39    5449 1236.39  5455.8  1233.6  5463.2 1237.15    5470 1235.56
  5477.4 1240.22  5497.8 1241.56  5636.1 1242.76  5768.1 1246.01  5778.2 1245.08
#Mann= 14 ,-1 , 0
  3570.2     .05       0  4073.8     .16       0    4198      .1       0
  4234.8     .05       0  4336.2      .1       0  4623.9     .05       0
  4973.8    .035       0  4979.8     .05       0  5097.1     .16       0
  5199.2     .05       0  5359.5     .08       0  5497.8      .1       0
  5636.1     .08       0  5768.1     .05       0
Bank Sta=4973.8,4979.8
XS Rating Curve= 0 ,0
Exp/Cntr=0.3,0.1

Type RM Length L Ch R = 1 ,12179   ,324,324,324
BEGIN DESCRIPTION:
DEER CREEK 27.0
END DESCRIPTION:
XS GIS Cut Line= 4
      2907993.51     10063778.62      2908674.94     10064052.06
      2909195.77     10064052.06      2909447.53     10063570.25
#Sta/Elev= 30
  3849.6 1236.71    3898 1234.07  3981.5 1226.54  4112.5 1222.84  4305.9 1216.36
  4382.2 1216.39  4597.4 1210.58  4627.4 1212.88  4736.7 1211.08  4798.2 1209.99
  4899.2 1209.81  4967.4    1208  4994.4 1203.85  4997.1 1203.35  5000.4 1203.85
    5096 1211.09  5105.4 1211.42  5181.1 1213.38  5225.3 1216.67  5230.9 1218.65
  5247.3 1217.77    5253 1219.72  5269.4 1217.69  5275.1 1219.35  5317.5 1222.59
  5322.5 1223.39  5335.7 1226.14  5418.3 1229.91  5549.5 1231.03  5648.3 1231.33
#Mann= 13 ,-1 , 0
  3849.6      .1       0  4112.5     .05       0  4305.9      .1       0
  4736.7     .08       0  4798.2      .1       0  4899.2     .16       0
  4994.4     .07       0  5000.4     .16       0    5096     .08       0
  5105.4     .05       0  5317.5      .1       0  5322.5     .05       0
  5549.5     .08       0
Bank Sta=4994.4,5000.4
XS Rating Curve= 0 ,0
Exp/Cntr=0.3,0.1

Type RM Length L Ch R = 1 ,11855   ,327,327,327
BEGIN DESCRIPTION:
DEER CREEK 26.0
END DESCRIPTION:
XS GIS Cut Line= 3
      2908010.86      10064186.6      2908970.08     10064568.55
      2909369.37     10063830.74
#Sta/Elev= 30
  3733.1 1218.58  4097.4 1212.88  4217.8 1210.76  4450.3 1208.88  4659.7 1209.36
  4804.5 1208.21  4872.7 1206.16  4922.2 1198.33    5001 1198.13  5003.7 1197.63
    5007 1198.13    5042 1199.29  5107.7  1205.5  5113.4 1207.82  5151.4 1212.41
  5189.5 1209.29    5351 1214.81  5436.5 1219.74  5460.3 1222.13  5468.2 1220.99
  5484.4 1223.82  5490.1  1221.7  5506.3 1224.54  5511.9 1221.99  5528.1 1224.89
  5533.8 1222.01    5550 1224.97  5555.7 1222.11  5569.6  1222.4  5604.5 1222.67
#Mann= 12 ,-1 , 0
  3733.1      .1       0  4097.4     .05       0  4217.8      .1       0
  4450.3     .08       0  4659.7      .1       0  4804.5     .08       0
    5001     .07       0    5007     .08       0    5351     .05       0
  5436.5     .08       0  5460.3      .1       0  5569.6     .05       0
Bank Sta=5001,5007
XS Rating Curve= 0 ,0
Exp/Cntr=0.3,0.1

Type RM Length L Ch R = 1 ,11528   ,744,744,744
BEGIN DESCRIPTION:
DEER CREEK 25.0
END DESCRIPTION:
XS GIS Cut Line= 3
      2908123.72      10064390.6      2909108.97     10064863.69
      2909811.92     10063388.35
#Sta/Elev= 30
  3644.7 1214.44  3684.8 1214.04  3707.9 1213.83  3936.6 1209.88  3959.4 1210.77
  4075.3 1207.48  4378.1 1207.33  4475.4 1205.71  4496.9 1203.28  4548.5 1205.02
  4581.8 1202.56  4610.1 1205.05  4654.2 1205.17  4768.3 1205.99  4932.8 1204.23
  4975.2 1197.27  4977.9 1196.77  4981.2 1197.27  5346.8 1210.34  5420.6 1216.74
  5448.8 1223.93  5479.8 1227.61  5653.1 1226.78  5837.1 1232.34  5857.9 1233.52
    5945 1234.43  6095.5 1241.29  6231.7 1240.83  6282.7 1244.89  6371.9 1246.29
#Mann= 11 ,-1 , 0
  3644.7     .05       0  3684.8      .1       0  3707.9     .05       0
  3936.6      .1       0  4075.3     .15       0  4475.4      .1       0
  4654.2     .05       0  4975.2     .04       0  4981.2     .05       0
  5837.1     .08       0  5857.9     .05       0
Bank Sta=4975.2,4981.2
XS Rating Curve= 0 ,0
Exp/Cntr=0.3,0.1

Type RM Length L Ch R = 1 ,10784   ,455,455,455
BEGIN DESCRIPTION:
DEER CREEK 24.0
END DESCRIPTION:
XS GIS Cut Line= 3
      2908049.97     10064377.61      2908922.34     10065167.51
       2909421.5     10065440.96
#Sta/Elev= 30
  3618.2 1216.07  3684.6 1214.43  3767.9 1213.85  3989.7 1209.11  4018.1  1210.2
  4074.8  1207.5  4180.6 1206.73  4244.5 1207.37  4358.1 1203.16  4513.5  1201.1
  4541.9 1199.52  4584.5 1200.87  4619.6 1198.69  4662.2 1200.86  4683.7 1200.52
  4900.3 1199.32  4938.2 1197.78  4969.2 1194.58  4992.9 1192.16  4995.6 1191.66
  4998.9 1192.16    5004 1192.24  5018.7 1193.48  5041.5 1201.45  5063.4 1211.09
  5085.2 1223.46  5098.5 1226.38  5183.9 1227.92  5218.3 1227.73  5364.2 1232.36
#Mann= 11 ,-1 , 0
  3618.2     .05       0  3684.6      .1       0  3767.9     .05       0
  4180.6      .1       0  4683.7     .05       0  4969.2     .16       0
  4992.9     .07       0  4998.9     .16       0    5004     .05       0
  5183.9      .1       0  5218.3     .05       0
Bank Sta=4992.9,4998.9
XS Rating Curve= 0 ,0
Exp/Cntr=0.3,0.1

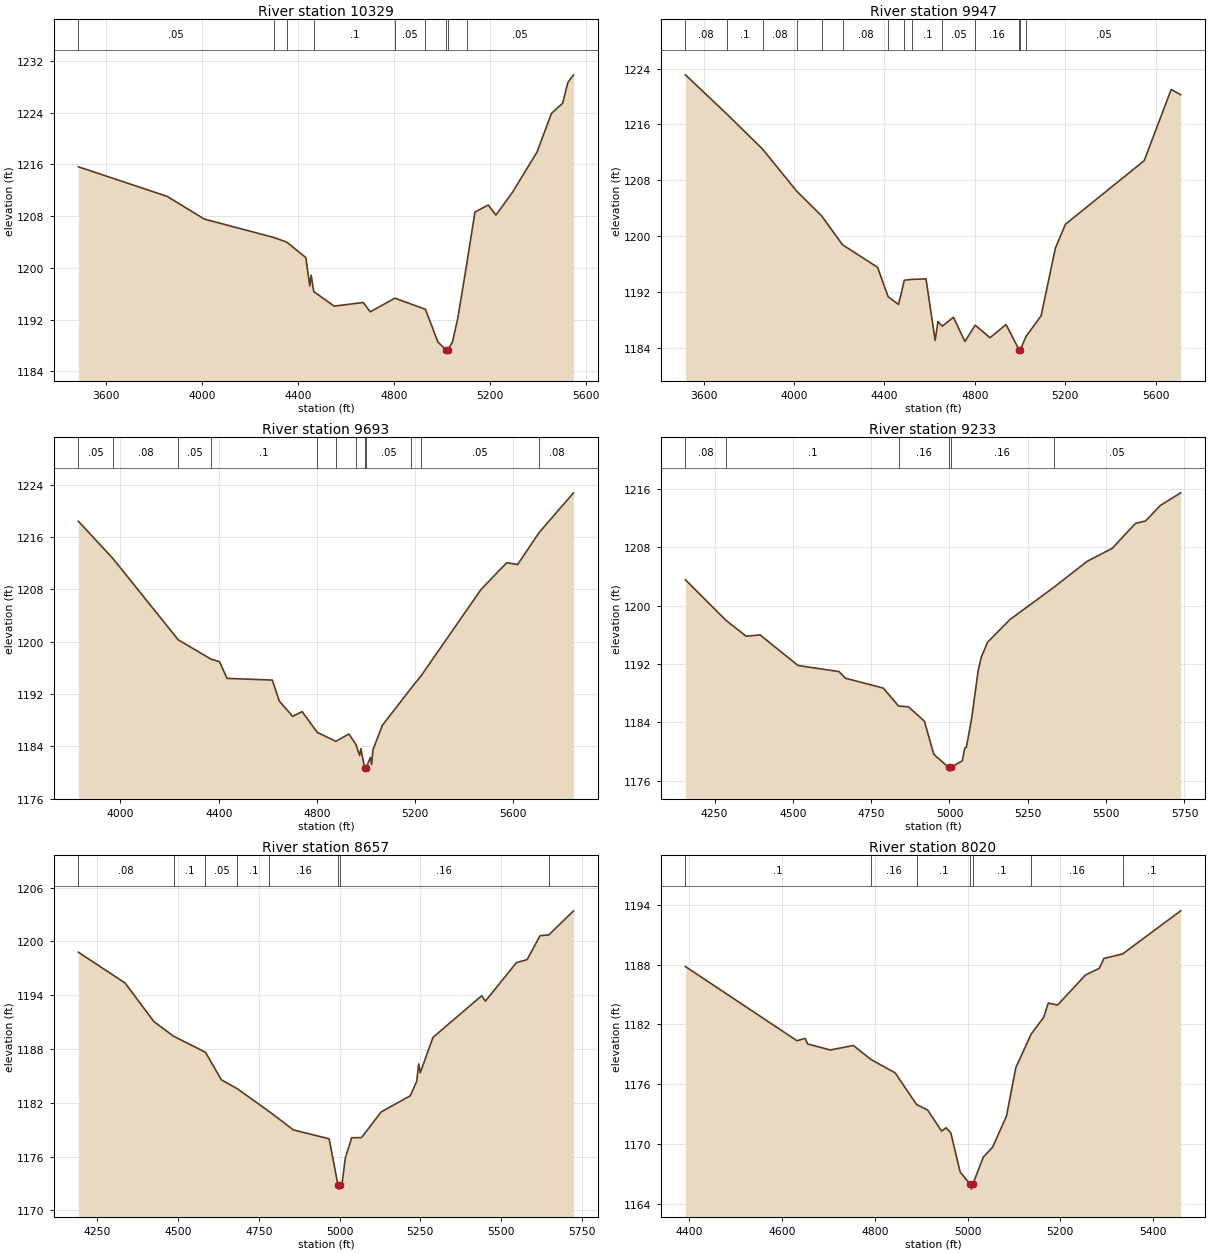
Type RM Length L Ch R = 1 ,10329   ,382,382,382
BEGIN DESCRIPTION:
DEER CREEK 23.0
END DESCRIPTION:
XS GIS Cut Line= 4
      2907994.39     10064421.87      2908525.63     10065468.73
      2908960.53     10065682.27      2909340.78     10065536.42
#Sta/Elev= 30
  3483.1 1215.63  3853.2 1211.06    4009 1207.54  4298.2  1204.7  4352.6 1203.98
    4432 1201.59  4448.7 1197.21  4454.3 1198.86  4465.3 1196.33  4550.5 1194.08
  4671.3 1194.64  4700.8  1193.2  4803.8 1195.31  4931.2 1193.58  4983.3 1188.51
  5018.2 1187.31  5020.9 1186.81  5024.2 1187.31  5043.7 1188.52  5066.1 1192.22
  5102.6 1200.44  5137.6 1208.63  5192.9 1209.72    5225 1208.16  5292.8 1211.61
  5396.4  1217.9  5456.9 1223.89  5503.5 1225.46  5524.9 1228.64  5548.8 1229.85
#Mann= 9 ,-1 , 0
  3483.1     .05       0  4298.2     .16       0  4352.6     .05       0
  4465.3      .1       0  4803.8     .05       0  4931.2     .16       0
  5018.2     .07       0  5024.2     .16       0  5102.6     .05       0
Bank Sta=5018.2,5024.2
XS Rating Curve= 0 ,0
Exp/Cntr=0.3,0.1

Type RM Length L Ch R = 1 ,9947    ,254,254,254
BEGIN DESCRIPTION:
DEER CREEK 22.0
END DESCRIPTION:
XS GIS Cut Line= 4
      2907213.15     10065716.13       2907694.9     10066031.23
      2908856.36     10065851.54      2909243.97     10065640.83
#Sta/Elev= 30
  3518.9 1223.11  3702.8 1217.48  3860.6 1212.47  4010.9 1206.48  4121.8 1202.92
  4214.4 1198.78  4369.4 1195.56  4416.1 1191.35  4462.4 1190.23  4487.8 1193.71
  4523.8 1193.83  4583.9  1193.9  4624.3  1185.1  4636.8  1187.8  4655.9 1187.13
  4705.3 1188.41  4755.9 1184.94  4801.6 1187.27  4867.2 1185.48    4938 1187.36
  4995.7 1183.77  4998.5 1183.27  5001.7 1183.77  5026.4 1185.65  5093.4 1188.62
  5156.5  1198.3  5201.1 1201.72  5549.5 1210.82  5669.2 1221.01    5711 1220.27
#Mann= 14 ,-1 , 0
  3518.9     .08       0  3702.8      .1       0  3860.6     .08       0
  4010.9     .05       0  4121.8      .1       0  4214.4     .08       0
  4416.1      .1       0  4487.8     .08       0  4523.8      .1       0
  4655.9     .05       0  4801.6     .16       0  4995.7     .07       0
  5001.7     .16       0  5026.4     .05       0
Bank Sta=4995.7,5001.7
XS Rating Curve= 0 ,0
Exp/Cntr=0.3,0.1

Type RM Length L Ch R = 1 ,9693    ,460,460,460
BEGIN DESCRIPTION:
DEER CREEK 21.0
END DESCRIPTION:
XS GIS Cut Line= 4
      2907278.19     10066200.49      2907700.11     10066234.35
      2908931.88     10065963.52       2909243.9     10065849.11
#Sta/Elev= 30
  3828.3 1218.44  3968.5 1212.77  4235.1  1200.3  4366.8 1197.37  4403.5 1196.93
  4434.2 1194.39  4618.5 1194.13  4647.2 1190.89  4701.2 1188.59  4739.8 1189.31
  4801.5 1186.13  4876.8 1184.76  4930.2 1185.88  4958.6 1184.31    4974 1182.59
  4979.1 1183.64  4994.3  1180.7  4997.1  1180.2  5000.3  1180.7  5017.8 1182.28
  5022.9 1181.22    5028 1183.44  5066.6 1187.21  5182.7 1192.84  5223.6 1194.75
  5468.3 1207.99    5573 1212.09  5617.4 1211.81  5705.3 1216.72  5845.1 1222.78
#Mann= 12 ,-1 , 0
  3828.3     .05       0  3968.5     .08       0  4235.1     .05       0
  4366.8      .1       0  4801.5     .05       0  4876.8     .16       0
  4958.6     .05       0  4994.3     .04       0  5000.3     .05       0
  5182.7     .16       0  5223.6     .05       0  5705.3     .08       0
Bank Sta=4994.3,5000.3
XS Rating Curve= 0 ,0
Exp/Cntr=0.3,0.1

Type RM Length L Ch R = 1 ,9233    ,576,576,576
BEGIN DESCRIPTION:
DEER CREEK 20.0
END DESCRIPTION:
XS GIS Cut Line= 2
      2907622.02     10066343.73      2909189.72     10066546.85
#Sta/Elev= 30
  4157.1 1203.56  4287.3 1197.97  4350.9 1195.82  4395.5    1196  4516.5 1191.81
  4647.6 1190.97  4667.9 1190.06  4788.8 1188.71  4837.3 1186.26  4869.4 1186.13
  4919.9 1184.18  4950.1 1179.62  4997.5 1177.83  5000.3 1177.33  5003.5 1177.83
  5040.9 1178.74    5049 1180.52    5054  1180.6  5071.1 1184.66  5091.3 1191.02
  5101.4 1192.93  5121.5 1194.99  5192.1 1198.07    5333 1202.52  5440.2  1206.1
  5519.4 1207.86  5593.6 1211.28  5625.7 1211.61  5672.9 1213.73  5737.9 1215.47
#Mann= 6 ,-1 , 0
  4157.1     .08       0  4287.3      .1       0  4837.3     .16       0
  4997.5     .07       0  5003.5     .16       0    5333     .05       0
Bank Sta=4997.5,5003.5
XS Rating Curve= 0 ,0
Exp/Cntr=0.3,0.1

Type RM Length L Ch R = 1 ,8657    ,637,637,637
BEGIN DESCRIPTION:
DEER CREEK 19.0
END DESCRIPTION:
XS GIS Cut Line= 2
      2907585.52     10066934.87      2909111.56     10067085.91
#Sta/Elev= 30
  4191.2 1198.79  4335.9 1195.36  4425.3 1191.05  4486.2 1189.42    4585 1187.63
  4633.9 1184.57  4683.7 1183.56  4782.4 1181.02  4857.4 1178.97  4967.9 1177.98
  4995.1 1172.87  4997.8 1172.37  5001.1 1172.87  5008.1 1173.04  5018.2 1175.88
  5037.9  1178.1  5068.4 1178.12  5128.7 1180.97  5219.1 1182.78  5239.2  1184.4
    5245 1186.33    5250 1185.34  5289.5 1189.29  5440.2 1193.93    5452 1193.34
    5548 1197.63  5580.9 1197.96  5621.1 1200.63  5648.1 1200.71  5724.7  1203.4
#Mann= 8 ,-1 , 0
  4191.2     .08       0  4486.2      .1       0    4585     .05       0
  4683.7      .1       0  4782.4     .16       0  4995.1     .07       0
  5001.1     .16       0  5648.1     .05       0
Bank Sta=4995.1,5001.1
XS Rating Curve= 0 ,0
Exp/Cntr=0.3,0.1

Type RM Length L Ch R = 1 ,8020    ,659,659,659
BEGIN DESCRIPTION:
DEER CREEK 18.0
END DESCRIPTION:
XS GIS Cut Line= 3
      2907819.94     10067492.18       2908069.9     10067604.14
      2908863.79     10067637.98
#Sta/Elev= 30
  4391.2 1187.82  4631.8 1180.37  4649.5  1180.6    4655 1180.04  4703.7 1179.44
  4753.7 1179.89  4791.4 1178.49  4843.8 1177.14  4889.8 1173.97  4913.9 1173.41
  4943.9  1171.3  4953.9 1171.63  4963.9  1171.1  4983.9  1167.2  5005.3 1165.97
  5008.1 1165.47  5011.3 1165.97    5034 1168.69    5054 1169.68    5084 1172.82
  5104.1 1177.67  5137.2 1181.04  5164.1 1182.71  5174.1 1184.15  5194.1 1183.95
  5254.2 1186.96  5284.2 1187.64  5294.2 1188.63  5334.4 1189.08  5459.7 1193.41
#Mann= 7 ,-1 , 0
  4391.2      .1       0  4791.4     .16       0  4889.8      .1       0
  5005.3     .07       0  5011.3      .1       0  5137.2     .16       0
  5334.4      .1       0
Bank Sta=5005.3,5011.3
XS Rating Curve= 0 ,0
Exp/Cntr=0.3,0.1

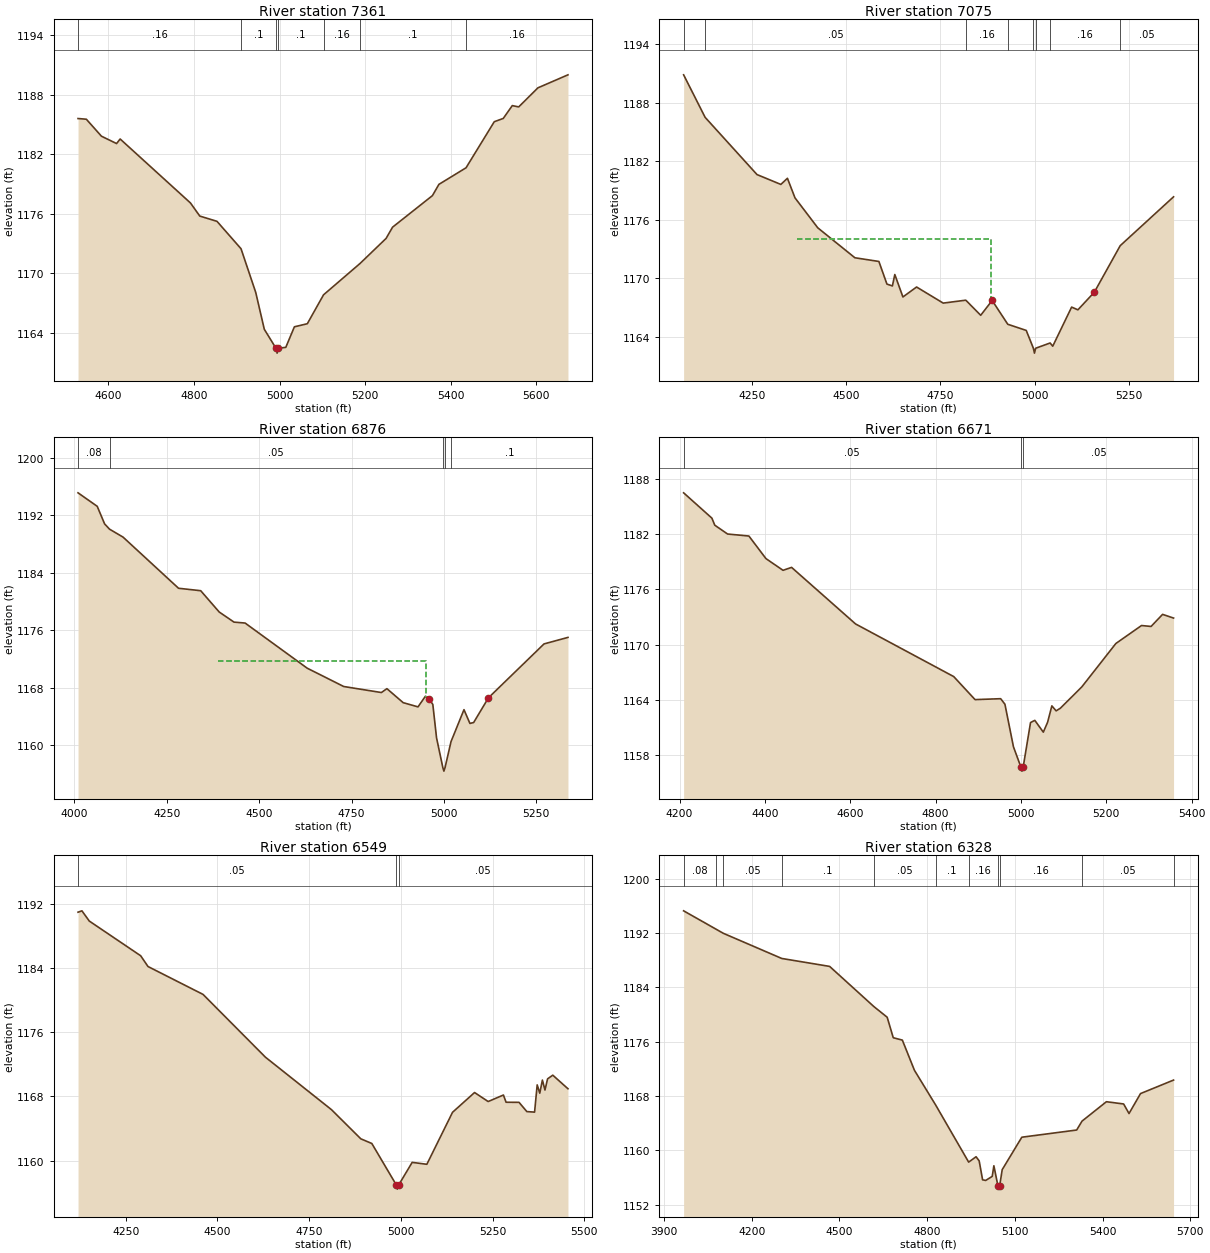
Type RM Length L Ch R = 1 ,7361    ,286,286,286
BEGIN DESCRIPTION:
DEER CREEK 17.0
END DESCRIPTION:
XS GIS Cut Line= 4
      2907791.27     10067973.95      2907955.32     10068190.08
      2908345.95     10068229.14      2908746.95     10067963.54
#Sta/Elev= 30
  4528.9  1185.6  4548.3 1185.53  4583.6 1183.82    4619 1183.08  4627.3 1183.54
  4791.6  1177.1  4813.4 1175.78  4853.6 1175.25  4909.8 1172.49  4944.1  1168.1
  4964.2 1164.38  4991.3 1162.48  4994.1 1161.98  4997.3 1162.48  5014.4 1162.56
  5034.5 1164.63  5064.7 1164.94  5102.6 1167.85    5188 1171.01  5248.8 1173.53
  5263.9 1174.66  5357.1 1177.84  5372.2 1178.97  5435.6 1180.64  5501.6 1185.28
  5522.6 1185.61  5543.7  1186.9  5558.7 1186.77  5603.6 1188.69  5673.8    1190
#Mann= 7 ,-1 , 0
  4528.9     .16       0  4909.8      .1       0  4991.3     .07       0
  4997.3      .1       0  5102.6     .16       0    5188      .1       0
  5435.6     .16       0
Bank Sta=4991.3,4997.3
XS Rating Curve= 0 ,0
Exp/Cntr=0.3,0.1

Type RM Length L Ch R = 1 ,7075    ,199,199,199
BEGIN DESCRIPTION:
DEER CREEK 16.0
END DESCRIPTION:
XS GIS Cut Line= 4
      2907345.21     10068808.86      2907711.48     10068765.38
      2908049.29     10068499.47      2908547.69     10068457.66
#Sta/Elev= 30
  4069.4 1190.85  4126.4 1186.49    4264 1180.62  4327.2 1179.61  4344.6 1180.24
  4364.7 1178.23  4425.1 1175.16  4523.5 1172.09  4587.1 1171.71  4608.4 1169.39
  4622.9  1169.2  4629.3 1170.37  4650.8 1168.07    4687 1169.09  4757.6 1167.44
  4817.5 1167.74    4857 1166.19  4887.4 1167.71  4928.8 1165.27  4977.7 1164.64
  4996.7 1162.81  4999.5 1162.31  5002.7 1162.81  5041.1 1163.35    5048 1163.02
  5098.1 1167.03  5114.7 1166.75  5158.3 1168.56  5226.9 1173.33  5368.3 1178.34
#Mann= 8 ,-1 , 0
  4069.4     .08       0  4126.4     .05       0  4817.5     .16       0
  4928.8      .1       0  4996.7     .07       0  5002.7      .1       0
  5041.1     .16       0  5226.9     .05       0
#XS Ineff= 1 ,-1
 4369.09 4885.34 1174.02
Permanent Ineff=
       T
Bank Sta=4887.4,5158.3
XS Rating Curve= 0 ,0
Exp/Cntr=0.3,0.1

Type RM Length L Ch R = 1 ,6876    ,205,205,205
BEGIN DESCRIPTION:
DEER CREEK 15.0
END DESCRIPTION:
XS GIS Cut Line= 4
      2907266.58     10068869.06      2907830.21     10068852.34
        2908061.     10068696.81      2908542.66     10068653.33
#Sta/Elev= 30
  4009.8 1195.15  4061.7 1193.27  4081.7 1190.82  4095.1 1190.08  4131.7 1188.97
  4281.8 1181.84  4341.8  1181.5  4391.8 1178.53  4431.9 1177.12  4461.9 1176.99
  4629.8  1170.7  4728.8 1168.14  4830.7  1167.3  4845.7 1167.84  4889.6 1165.89
  4929.8  1165.3  4949.8 1166.78  4959.9 1166.42  4969.9 1165.64    4980 1160.97
    4997 1156.84  4999.8 1156.34    5003 1156.84  5019.1 1160.45  5054.2 1164.91
  5070.3 1162.99  5080.4 1163.12  5120.5 1166.57  5270.8 1174.08  5335.6 1174.99
#Mann= 5 ,-1 , 0
  4009.8     .08       0  4095.1     .05       0    4997     .04       0
    5003     .05       0  5019.1      .1       0
#XS Ineff= 1 ,-1
 4389.77 4951.36 1171.71
Permanent Ineff=
       T
Bank Sta=4959.9,5120.5
XS Rating Curve= 0 ,0
Exp/Cntr=0.3,0.1

Type RM Length L Ch R = 1 ,6671    ,122,122,122
BEGIN DESCRIPTION:
DEER CREEK 14.0
END DESCRIPTION:
XS GIS Cut Line= 3
      2907445.45     10068889.21      2908497.51      10068881.4
      2908549.61     10068800.64
#Sta/Elev= 30
  4209.4 1186.49  4275.7 1183.74  4282.4 1182.98  4312.4 1182.02  4362.4  1181.8
  4402.4 1179.35  4442.4 1178.08  4462.4  1178.4  4612.4 1172.26  4842.4 1166.55
  4892.4 1164.05  4952.4 1164.15  4962.4 1163.55  4982.4 1158.93  4999.4 1156.79
  5002.2 1156.29  5005.4 1156.79  5022.4 1161.56  5032.4  1161.8  5052.4 1160.52
  5062.4 1161.59  5072.4 1163.37  5082.4 1162.83  5092.4 1163.12  5142.4 1165.42
  5222.4 1170.14  5282.5 1172.09  5304.9 1171.99  5331.9  1173.3  5357.6  1172.9
#Mann= 3 ,-1 , 0
  4209.4     .05       0  4999.4     .04       0  5005.4     .05       0
Bank Sta=4999.4,5005.4
XS Rating Curve= 0 ,0
Exp/Cntr=0.3,0.1

Type RM Length L Ch R = 1 ,6549    ,221,221,221
BEGIN DESCRIPTION:
DEER CREEK 13.0
END DESCRIPTION:
XS GIS Cut Line= 3
      2907377.82     10068991.13      2908497.64     10068998.94
      2908648.68      10068845.3
#Sta/Elev= 30
  4120.2 1190.92  4130.8 1191.09  4150.8 1189.82  4290.9  1185.5  4310.9 1184.16
  4460.9 1180.69  4630.9 1172.88  4810.9 1166.35  4890.9 1162.72  4920.9 1162.14
  4987.9 1156.96  4990.6 1156.46  4993.9 1156.96  5030.9 1159.79  5070.9 1159.55
  5140.9 1166.02  5200.9 1168.48    5238 1167.36  5279.6 1168.17  5286.8 1167.27
  5322.1 1167.26  5343.4 1166.11  5364.5 1166.04  5371.6 1169.43  5378.7  1168.4
  5385.8 1170.03  5392.8 1168.79  5399.9 1170.18  5414.1 1170.64  5455.5 1168.95
#Mann= 3 ,-1 , 0
  4120.2     .05       0  4987.9     .04       0  4993.9     .05       0
Bank Sta=4987.9,4993.9
XS Rating Curve= 0 ,0
Exp/Cntr=0.3,0.1

Type RM Length L Ch R = 1 ,6328    ,707,707,707
BEGIN DESCRIPTION:
Mapping XS 5830a78a
END DESCRIPTION:
XS GIS Cut Line= 5
      2907346.58     10069514.57      2908127.85     10069301.03
       2908601.8     10069064.05      2908669.51     10068897.38
      2908673.96     10068740.77
#Sta/Elev= 30
  3966.7 1195.29  4079.1 1192.55  4102.4 1191.98  4302.5 1188.27  4466.3  1187.1
    4618 1181.17  4663.2 1179.61    4684 1176.59  4715.1 1176.24  4756.5 1171.79
  4829.3 1166.66    4942 1158.26  4967.4 1159.05    4978 1158.44  4989.7 1155.65
  5000.3 1155.56  5022.7 1156.16  5028.3 1157.72  5042.1 1154.78  5044.8 1154.28
  5048.1 1154.78  5056.8 1157.15  5123.9 1161.93  5311.6 1162.99  5329.9  1164.3
  5413.3 1167.16  5472.3 1166.83  5490.7 1165.42  5530.1 1168.36  5643.1 1170.35
#Mann= 11 ,-1 , 0
  3966.7     .08       0  4079.1      .1       0  4102.4     .05       0
  4302.5      .1       0    4618     .05       0  4829.3      .1       0
    4942     .16       0  5042.1     .07       0  5048.1     .16       0
  5329.9     .05       0  5643.1     .05       0
#XS Ineff= 2 , 0
                         5413.64         1167.15
Permanent Ineff=
       T       T
Bank Sta=5042.1,5048.1
XS Rating Curve= 0 ,0
Exp/Cntr=0.3,0.1

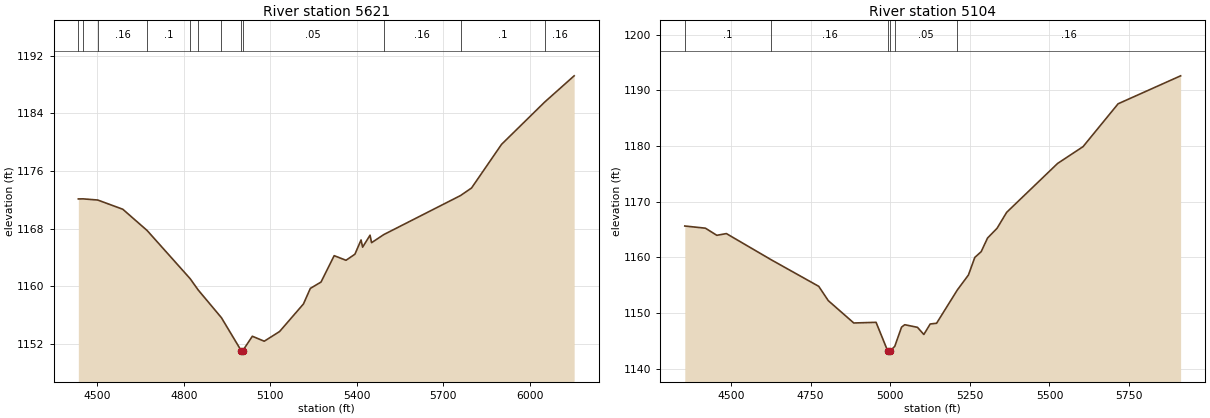
Type RM Length L Ch R = 1 ,5621    ,517,517,517
BEGIN DESCRIPTION:
DEER CREEK 12.0
END DESCRIPTION:
XS GIS Cut Line= 4
      2908924.12     10069736.44      2908975.66     10069359.81
      2908749.68     10068812.72      2908995.18     10068107.92
#Sta/Elev= 30
  4434.7 1172.13  4451.2 1172.14  4501.9 1171.98  4588.8  1170.7  4672.9 1167.76
  4822.4 1161.06  4850.1  1159.5  4930.7 1155.65  4998.9  1151.1  5001.7  1150.6
  5004.9  1151.1  5037.8 1153.08  5079.1 1152.39  5132.3 1153.74  5214.9 1157.56
  5238.8 1159.72  5275.8  1160.6  5321.4 1164.26  5362.4 1163.62  5393.2 1164.46
  5414.6 1166.44  5419.9 1165.44  5445.7  1167.1    5451 1166.06  5493.1 1167.18
  5759.3  1172.6  5797.5 1173.65  5901.4  1179.7  6051.2 1185.58  6153.1 1189.21
#Mann= 12 ,-1 , 0
  4434.7     .16       0  4451.2      .1       0  4501.9     .16       0
  4672.9      .1       0  4822.4     .05       0  4850.1     .16       0
  4930.7     .05       0  4998.9     .04       0  5004.9     .05       0
  5493.1     .16       0  5759.3      .1       0  6051.2     .16       0
Bank Sta=4998.9,5004.9
XS Rating Curve= 0 ,0
Exp/Cntr=0.3,0.1

Type RM Length L Ch R = 1 ,5104    ,491,491,491
BEGIN DESCRIPTION:
DEER CREEK 11.0
END DESCRIPTION:
XS GIS Cut Line= 2
      2909292.82     10069534.29      2909308.66     10067977.47
#Sta/Elev= 30
  4354.9 1165.63  4419.6 1165.24  4455.5 1163.96  4485.5 1164.27  4625.3  1159.6
  4775.5  1154.8  4805.5 1152.23  4885.5 1148.22  4955.5 1148.34  4992.5 1143.13
  4995.2 1142.63  4998.5 1143.13  5014.2 1144.03  5035.5 1147.47  5045.5 1147.91
  5085.5 1147.44  5105.5 1146.16  5125.5 1148.04  5145.5 1148.17  5210.8 1154.16
  5245.5 1156.83  5265.5 1159.99  5285.5 1161.02  5305.5 1163.47  5335.5 1165.23
  5365.5 1168.08  5525.5 1176.86  5605.5 1179.88  5715.5 1187.57  5911.8 1192.59
#Mann= 6 ,-1 , 0
  4354.9      .1       0  4625.3     .16       0  4992.5     .07       0
  4998.5     .16       0  5014.2     .05       0  5210.8     .16       0
Bank Sta=4992.5,4998.5
XS Rating Curve= 0 ,0
Exp/Cntr=0.3,0.1