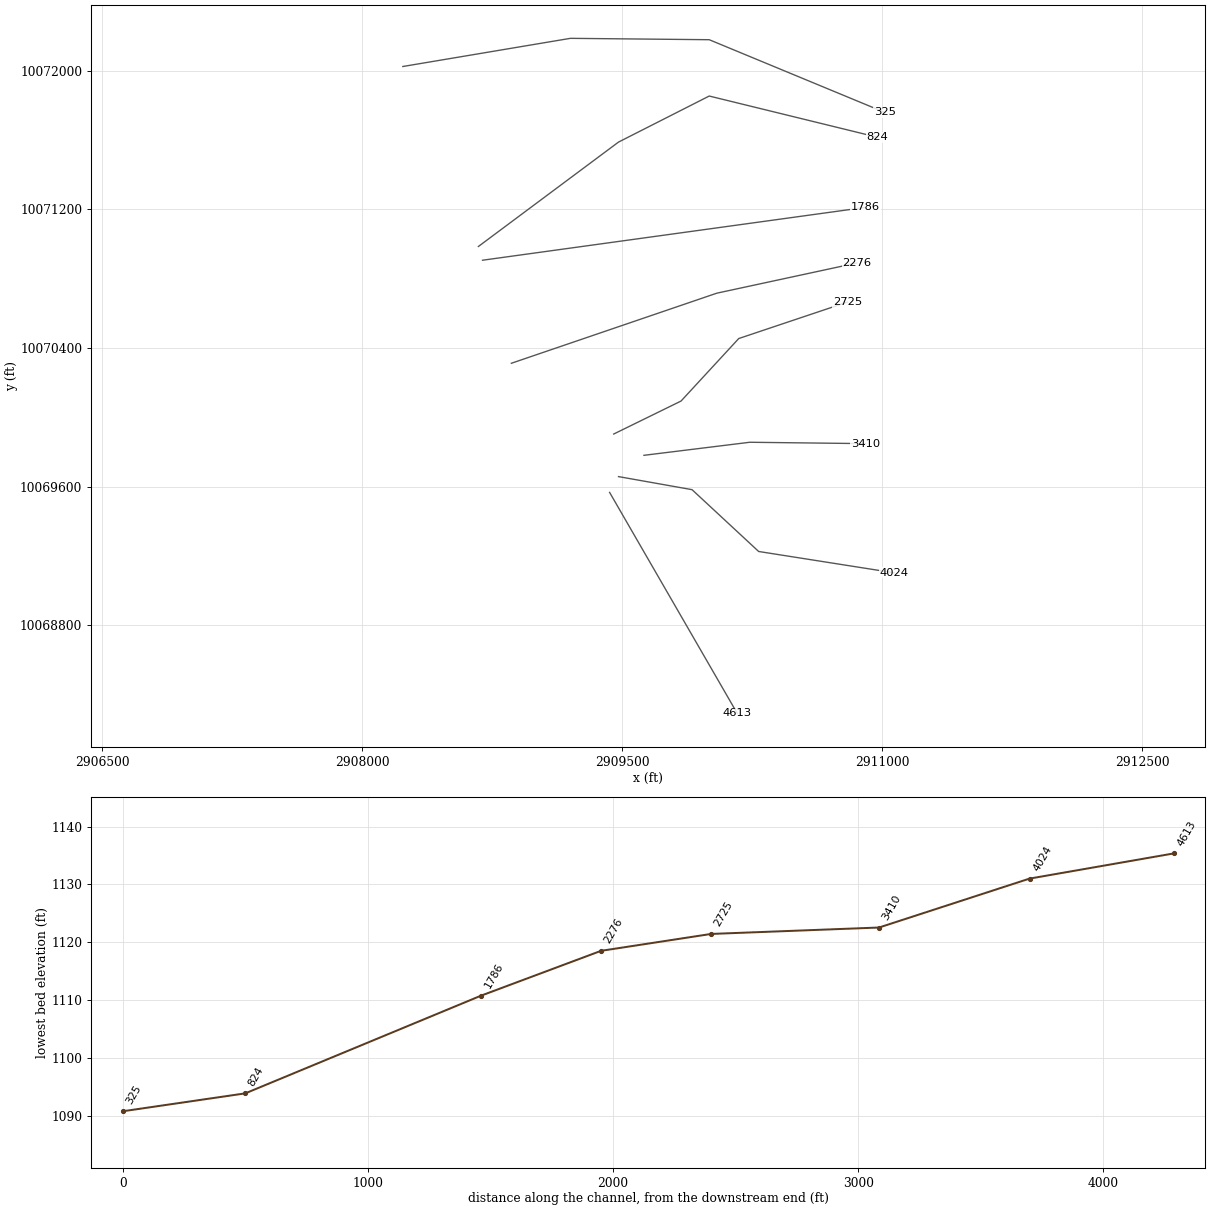
HEC-RAS study DEER CREEK.prj: DEER CREEK Base Level Engineering

--- DEER CREEK.g01 (geometry) --- (continued)

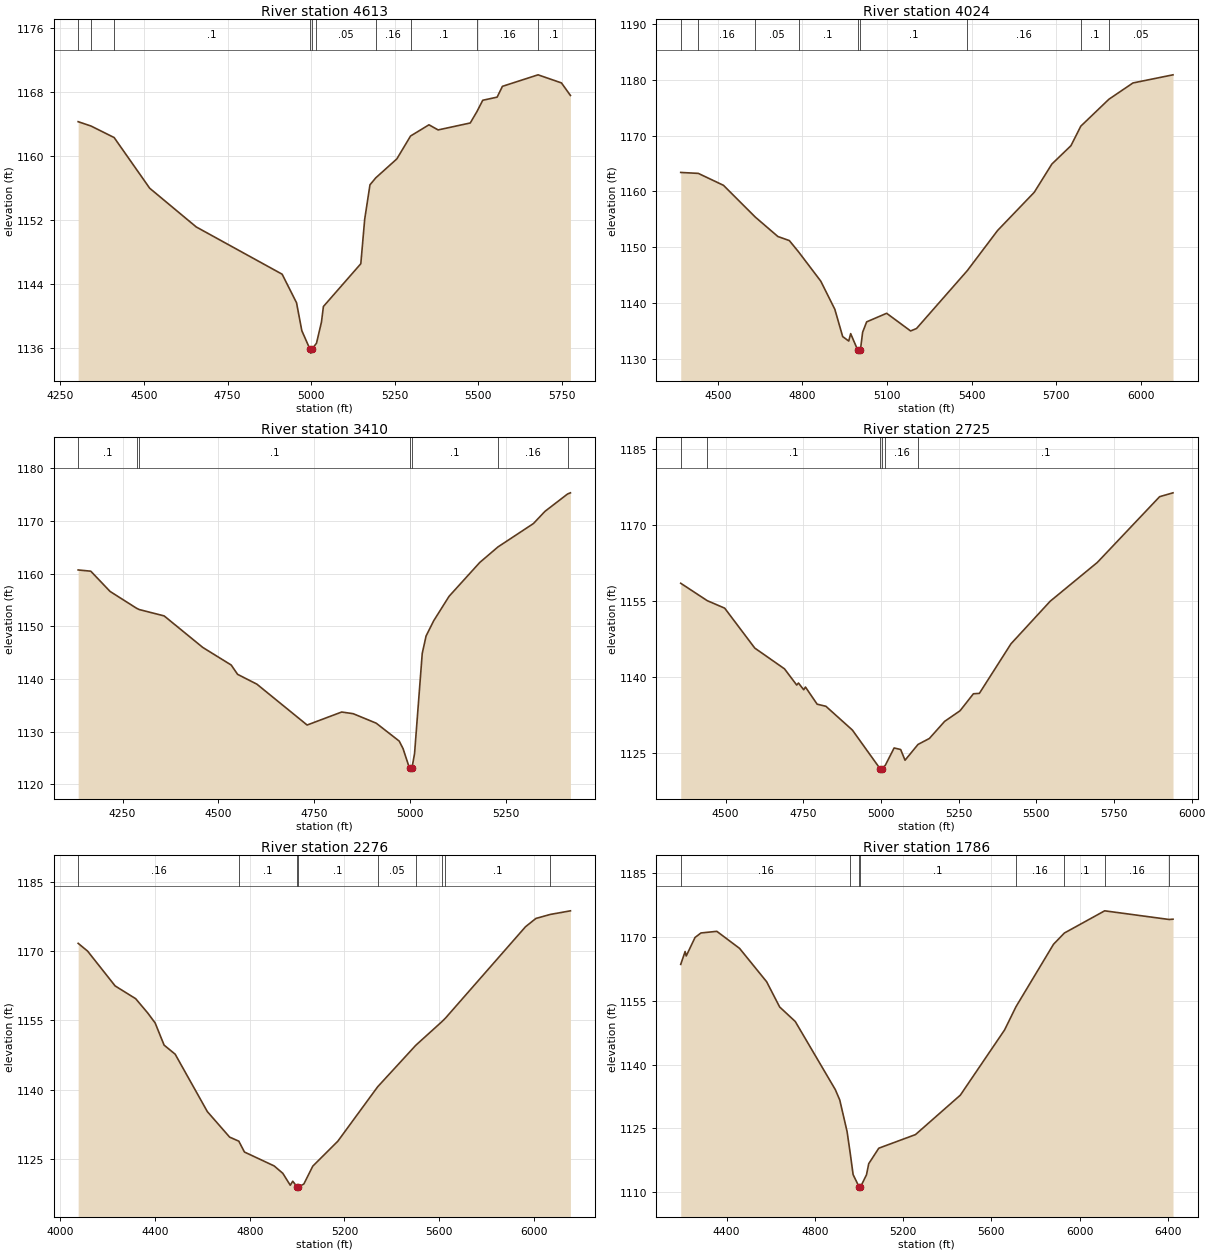
Type RM Length L Ch R = 1 ,4613    ,589,589,589
BEGIN DESCRIPTION:
DEER CREEK 10.0
END DESCRIPTION:
XS GIS Cut Line= 2
       2909427.6     10069565.99      2910164.22     10068290.75
#Sta/Elev= 30
  4303.1 1164.29  4341.4 1163.75  4410.7 1162.31  4517.1 1155.97  4656.3 1151.13
  4913.3 1145.22  4956.4 1141.65  4972.2 1138.16  4996.5 1135.85  4999.2 1135.35
  5002.5 1135.85  5016.1 1136.59    5031 1139.24  5036.8 1141.18  5148.7 1146.53
  5160.3 1152.09  5176.1  1156.4  5193.5 1157.27  5256.5 1159.64  5297.5  1162.5
  5352.6  1163.9    5380 1163.26  5476.1 1164.13  5495.9 1165.54  5513.5 1166.97
  5556.5 1167.36  5572.3 1168.71  5678.9 1170.15  5748.9 1169.14  5775.8 1167.57
#Mann= 10 ,-1 , 0
  4303.1      .1       0  4341.4     .05       0  4410.7      .1       0
  4996.5     .07       0  5002.5      .1       0  5016.1     .05       0
  5193.5     .16       0  5297.5      .1       0  5495.9     .16       0
  5678.9      .1       0
Bank Sta=4996.5,5002.5
XS Rating Curve= 0 ,0
Exp/Cntr=0.3,0.1

Type RM Length L Ch R = 1 ,4024    ,614,614,614
BEGIN DESCRIPTION:
DEER CREEK 9.0
END DESCRIPTION:
XS GIS Cut Line= 4
      2909479.15     10069657.15      2909903.34     10069581.82
       2910287.9     10069225.02      2911068.88     10069102.13
#Sta/Elev= 30
  4368.6 1163.42    4431 1163.25  4520.2 1161.11    4633 1155.41  4713.2 1151.92
  4753.8 1151.19  4786.5 1149.17  4865.3 1143.91  4915.2 1138.85    4943 1133.96
  4964.5 1133.16  4971.3 1134.49  4996.7 1131.49  4999.4 1130.99  5002.7 1131.49
    5007    1132  5013.8 1134.74    5028  1136.6  5098.9 1138.14  5183.9 1134.97
  5204.9 1135.41  5385.2 1145.81  5492.4    1153  5622.5 1159.86    5685 1164.93
  5752.6 1168.22  5787.5 1171.72  5887.3 1176.56  5972.5 1179.48  6114.6 1180.94
#Mann= 9 ,-1 , 0
  4368.6      .1       0    4431     .16       0    4633     .05       0
  4786.5      .1       0  4996.7     .07       0  5002.7      .1       0
  5385.2     .16       0  5787.5      .1       0  5887.3     .05       0
Bank Sta=4996.7,5002.7
XS Rating Curve= 0 ,0
Exp/Cntr=0.3,0.1

Type RM Length L Ch R = 1 ,3410    ,685,685,685
BEGIN DESCRIPTION:
DEER CREEK 7.0
END DESCRIPTION:
XS GIS Cut Line= 3
      2909625.82     10069780.05      2910236.36     10069855.37
      2910904.95     10069847.46
#Sta/Elev= 30
  4134.2 1160.71  4167.1 1160.48  4217.5 1156.63  4286.6 1153.44  4293.8 1153.19
  4358.5 1151.99  4459.3    1146  4533.3 1142.67    4550  1140.9  4600.4 1139.03
  4731.3 1131.28  4821.5 1133.75  4851.5 1133.43  4911.5 1131.63  4971.5 1128.23
  4981.5  1126.8  4998.5 1123.03  5001.2 1122.53  5004.5 1123.03  5011.5 1125.86
  5031.5 1144.87  5041.5 1148.17  5061.5 1151.08  5101.5 1155.71  5181.5 1162.13
    5229 1165.08  5321.5 1169.52  5351.5 1171.83  5410.5 1175.13    5418 1175.35
#Mann= 7 ,-1 , 0
  4134.2      .1       0  4286.6     .16       0  4293.8      .1       0
  4998.5     .07       0  5004.5      .1       0    5229     .16       0
  5410.5      .1       0
Bank Sta=4998.5,5004.5
XS Rating Curve= 0 ,0
Exp/Cntr=0.3,0.1

Type RM Length L Ch R = 1 ,2725    ,449,449,449
BEGIN DESCRIPTION:
DEER CREEK 6.0
END DESCRIPTION:
XS GIS Cut Line= 4
      2909451.38     10069902.94      2909839.91     10070093.24
      2910172.93     10070454.01      2910799.33     10070664.13
#Sta/Elev= 30
  4355.7 1158.46    4441 1155.03  4497.2 1153.55    4594 1145.68  4689.6 1141.59
    4729 1138.39  4734.6 1138.79  4751.5 1137.46  4757.1    1138  4794.7 1134.62
    4823  1134.2  4908.1 1129.52    4997 1121.92  4999.7 1121.42    5003 1121.92
  5013.9 1122.55  5042.5 1125.99  5063.5 1125.68  5077.6 1123.57  5119.3 1126.68
  5155.9 1127.86  5205.2 1131.24  5254.6 1133.32  5297.6 1136.67  5316.8 1136.75
  5418.5 1146.52  5544.6 1154.91  5696.5 1162.57  5896.9 1175.53    5940 1176.29
#Mann= 6 ,-1 , 0
  4355.7     .16       0    4441      .1       0    4997     .07       0
    5003      .1       0  5013.9     .16       0  5119.3      .1       0
Bank Sta=4997,5003
XS Rating Curve= 0 ,0
Exp/Cntr=0.3,0.1

Type RM Length L Ch R = 1 ,2276    ,490,490,490
BEGIN DESCRIPTION:
DEER CREEK 5.0
END DESCRIPTION:
XS GIS Cut Line= 3
      2908860.67     10070311.28      2910046.07     10070715.66
      2910854.11     10070889.94
#Sta/Elev= 30
  4075.2 1171.65  4115.1 1169.97  4231.4 1162.44  4318.1 1159.68  4368.7 1156.61
  4400.4 1154.43  4438.2 1149.64  4484.9 1147.68  4620.9 1135.26  4714.9 1129.75
  4753.7 1128.87  4777.6 1126.52  4902.9 1123.52  4939.6 1121.92    4971 1119.34
  4981.5 1120.21  4999.7    1119  5002.4  1118.5  5005.7    1119  5028.3  1119.6
  5066.1 1123.47  5171.7 1128.85    5340 1140.62  5501.3 1149.61  5612.8 1154.78
  5626.5 1155.48  5964.4 1175.23  6008.3 1177.03  6069.2  1177.9  6154.3 1178.68
#Mann= 9 ,-1 , 0
  4075.2     .16       0  4753.7      .1       0  4999.7     .07       0
  5005.7      .1       0    5340     .05       0  5501.3      .1       0
  5612.8     .05       0  5626.5      .1       0  6069.2     .16       0
Bank Sta=4999.7,5005.7
XS Rating Curve= 0 ,0
Exp/Cntr=0.3,0.1

Type RM Length L Ch R = 1 ,1786    ,962,962,962
BEGIN DESCRIPTION:
DEER CREEK 4.0
END DESCRIPTION:
XS GIS Cut Line= 2
      2908694.19     10070905.96      2910904.94     10071211.02
#Sta/Elev= 30
  4191.8 1163.56  4211.7 1166.58  4216.7 1165.54  4256.7 1169.89  4283.6 1170.95
  4355.5 1171.33  4458.6 1167.32  4581.3 1159.48  4640.3 1153.55    4711 1150.14
  4892.7 1134.12  4912.8 1131.68  4945.9 1124.28  4960.2 1119.17  4973.4 1114.14
  5000.7 1111.24  5003.5 1110.74  5006.7 1111.24    5034 1114.12  5044.1 1116.72
  5089.7 1120.36  5256.1 1123.56  5459.4 1132.83  5659.9 1148.15  5711.4 1153.59
  5881.9  1168.3    5931 1170.93  6113.7 1176.15  6405.4 1174.12  6423.5 1174.18
#Mann= 8 ,-1 , 0
  4191.8     .16       0  4960.2      .1       0  5000.7     .07       0
  5006.7      .1       0  5711.4     .16       0    5931      .1       0
  6113.7     .16       0  6405.4      .1       0
Bank Sta=5000.7,5006.7
XS Rating Curve= 0 ,0
Exp/Cntr=0.3,0.1

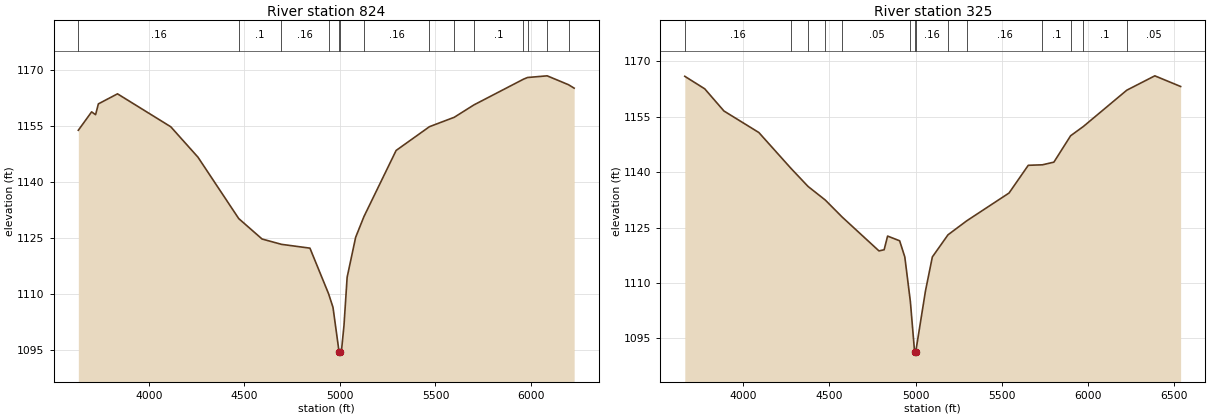
Type RM Length L Ch R = 1 ,824     ,499,499,499
BEGIN DESCRIPTION:
DEER CREEK 2.0
END DESCRIPTION:
XS GIS Cut Line= 4
      2908670.41     10070985.26      2909479.15     10071587.84
      2910002.46     10071853.46      2910973.65     10071615.62
#Sta/Elev= 30
  3630.8 1153.77  3700.3 1158.69  3721.1 1157.94  3735.7 1160.83  3835.8 1163.52
  4114.7  1154.7    4257 1146.56  4470.3 1130.13  4592.7 1124.65  4694.2 1123.23
  4843.1 1122.21  4940.6 1110.01  4963.8 1106.36  4995.9 1094.34  4998.7 1093.84
  5001.9 1094.34  5008.7 1095.04  5021.2 1101.44  5037.8 1114.41  5082.4 1125.12
  5125.7 1130.65  5294.2 1148.36  5468.8 1154.73  5598.4 1157.24  5701.6 1160.56
  5960.8 1167.44  5982.2 1167.89  6084.8 1168.34  6196.5 1165.96  6226.1 1165.04
#Mann= 14 ,-1 , 0
  3630.8     .16       0  4470.3      .1       0  4694.2     .16       0
  4940.6      .1       0  4995.9     .07       0  5001.9      .1       0
  5125.7     .16       0  5468.8      .1       0  5598.4     .05       0
  5701.6      .1       0  5960.8     .16       0  5982.2      .1       0
  6084.8     .05       0  6196.5      .1       0
Bank Sta=4995.9,5001.9
XS Rating Curve= 0 ,0
Exp/Cntr=0.3,0.1

Type RM Length L Ch R = 1 ,325     ,0,0,0
BEGIN DESCRIPTION:
DEER CREEK 1.0
END DESCRIPTION:
XS GIS Cut Line= 4
      2908234.28     10072023.93      2909201.63     10072186.48
      2910002.46     10072178.55      2911016.86     10071758.52
#Sta/Elev= 30
  3659.9 1165.96  3775.7 1162.57  3887.2 1156.57    4090 1150.74  4276.7 1141.03
  4376.1 1136.13  4475.4 1132.48  4574.8 1127.82  4787.7 1118.69  4817.7 1119.01
  4837.7 1122.71  4907.7 1121.43  4937.7 1117.05  4970.1 1104.94  4994.7 1091.25
  4997.4 1090.75  5000.7 1091.25  5057.7 1107.86  5097.7 1117.06  5188.5 1123.05
  5297.7 1126.85    5543 1134.36  5654.8 1141.87  5736.6    1142  5803.5 1142.72
  5900.8 1149.87  5974.6 1152.37  6226.9  1162.2  6389.8 1166.09  6539.6  1163.2
#Mann= 14 ,-1 , 0
  3659.9     .16       0  4276.7      .1       0  4376.1     .16       0
  4475.4      .1       0  4574.8     .05       0  4970.1     .16       0
  4994.7     .07       0  5000.7     .16       0  5188.5      .1       0
  5297.7     .16       0  5736.6      .1       0  5900.8     .05       0
  5974.6      .1       0  6226.9     .05       0
Bank Sta=4994.7,5000.7
XS Rating Curve= 0 ,0
Exp/Cntr=0.3,0.1

Chan Stop Cuts=-1
Use User Specified Reach Order=0
Composite Channel Slope=5