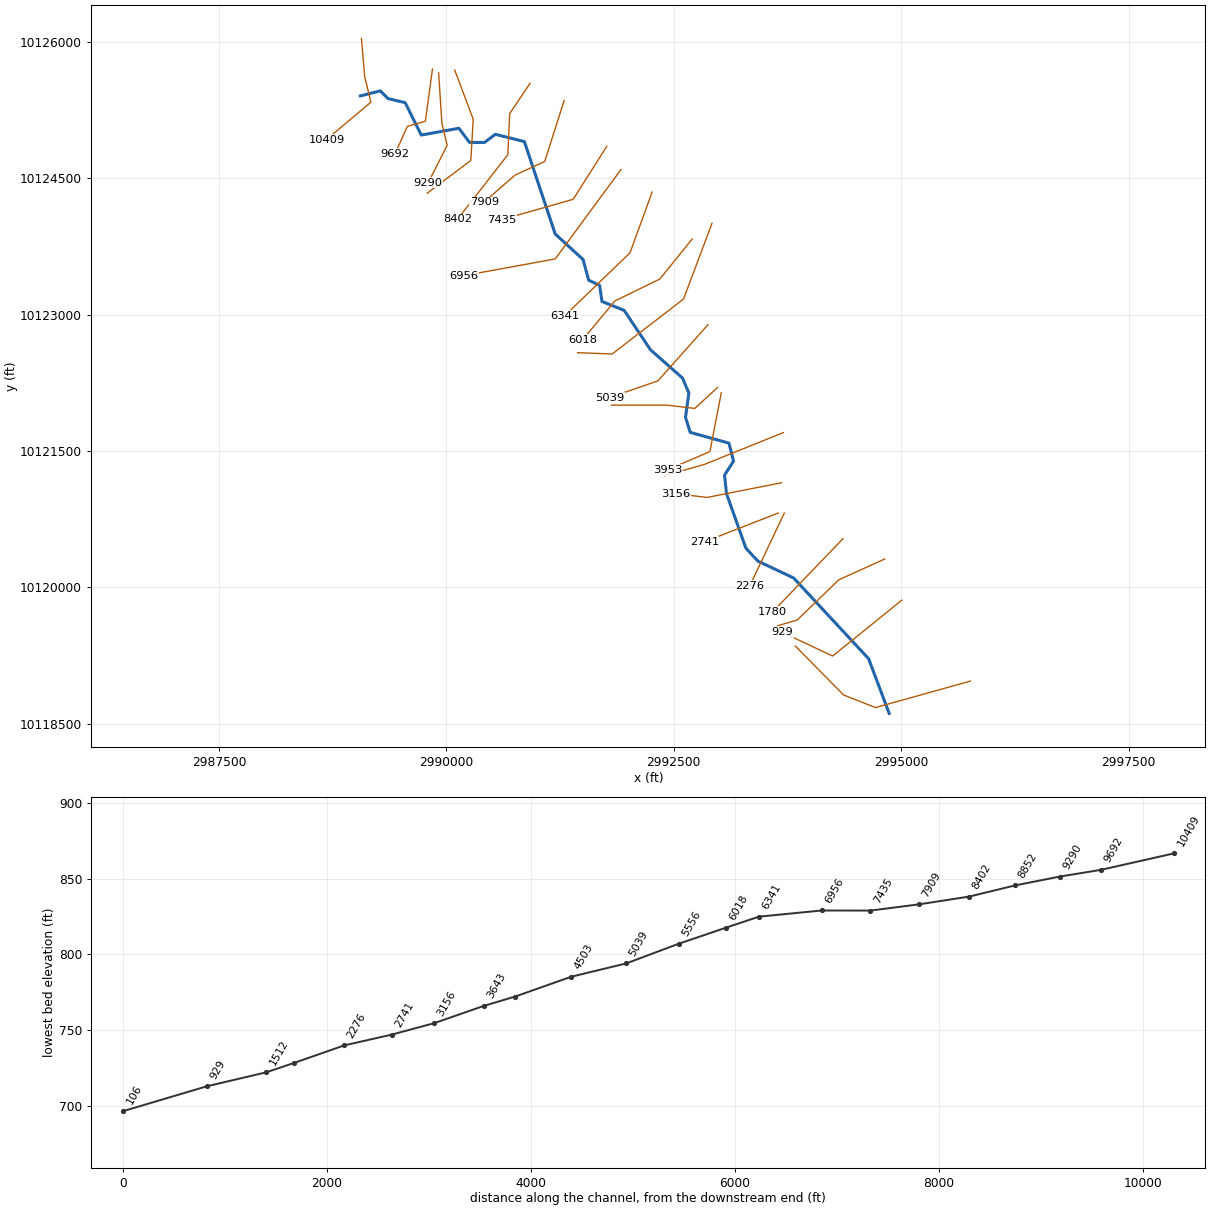
--- FALL CREEK TRIB 1.prj (project) ---

Proj Title=FALL CREEK TRIB 1 Base Level Engineering
Current Plan=p01
Default Exp/Contr=0.3,0.1
English Units
Geom File=g01
Flow File=f01
Plan File=p01
BEGIN DESCRIPTION:
FALL CREEK TRIB 1
END DESCRIPTION:

--- FALL CREEK TRIB 1.p01 (plan) ---

Plan Title=Multiple Run
Short Identifier=Multiple
Geom File=g01
Flow File=f01
Subcritical Flow
K Sum by GR= 0
Std Step Tol= 0.01
Critical Tol= 0.01
Num of Std Step Trials= 20
Max Error Tol= 0.3
Flow Tol Ratio= 0.001
Split Flow NTrial= 30
Split Flow Tol= 0.02
Split Flow Ratio= 0.02
Log Output Level= 0
Friction Slope Method= 1
Unsteady Friction Slope Method= 2
Unsteady Bridges Friction Slope Method= 1
Parabolic Critical Depth
Global Vel Dist=  1 , 1 , 1
Global Log Level= 0
CheckData=True
Encroach Param= -1, 0, 0, 0
BEGIN DESCRIPTION:
Multiple Run
END DESCRIPTION:

--- FALL CREEK TRIB 1.f01 (steady flow) ---

Flow Title=Multiple
Number of Profiles=7
Profile Names=10-year,25-year,50-year,1pct_min,100-year,1pct_plu,500-year
River Rch & RM= FALL CREEK TRIB ,Reach-1,10409
     963    1414    1812    1701    2300    3110    3720
River Rch & RM= FALL CREEK TRIB ,Reach-1,9290
    1462    2192    2846    2703    3656    4944    6059
River Rch & RM= FALL CREEK TRIB ,Reach-1,5039
    1740    2628    3430    3271    4424    5982    7392
Boundary for River Rch & Prof#=FALL CREEK TRIB ,Reach-1,1
Up Type=0
Dn Type=3
Dn Slope=0.005
Boundary for River Rch & Prof#=FALL CREEK TRIB ,Reach-1,2
Up Type=0
Dn Type=3
Dn Slope=0.005
Boundary for River Rch & Prof#=FALL CREEK TRIB ,Reach-1,3
Up Type=0
Dn Type=3
Dn Slope=0.005
Boundary for River Rch & Prof#=FALL CREEK TRIB ,Reach-1,4
Up Type=0
Dn Type=3
Dn Slope=0.005
Boundary for River Rch & Prof#=FALL CREEK TRIB ,Reach-1,5
Up Type=0
Dn Type=3
Dn Slope=0.005
Boundary for River Rch & Prof#=FALL CREEK TRIB ,Reach-1,6
Up Type=0
Dn Type=3
Dn Slope=0.005
Boundary for River Rch & Prof#=FALL CREEK TRIB ,Reach-1,7
Up Type=0
Dn Type=3
Dn Slope=0.005

--- FALL CREEK TRIB 1.g01 (geometry) ---

Geom Title=Existing Conditions

River Reach=FALL CREEK TRIB ,Reach-1
Reach XY= 30
      2989054.34     10125406.21      2989273.32     10125461.45
      2989359.53     10125376.72      2989547.78     10125331.55
      2989724.19     10124975.58      2990138.18     10125049.95
      2990253.82     10124895.38      2990418.66     10124893.40
      2990539.36     10124983.77      2990858.06     10124903.91
      2991196.80     10123887.32      2991503.41     10123606.37
      2991564.85     10123378.36      2991685.01     10123322.50
      2991710.73     10123145.22      2991955.24     10123047.02
      2992244.96     10122612.94      2992596.05     10122302.82
      2992666.69     10122137.93      2992629.42     10121871.58
      2992680.90     10121705.19      2993106.57     10121586.68
      2993157.37     10121388.54      2993058.16     10121234.19
      2993080.51     10121029.28      2993293.29     10120431.01
      2993425.70     10120288.53      2993818.09     10120103.04
      2994642.46     10119214.91      2994868.47     10118613.73

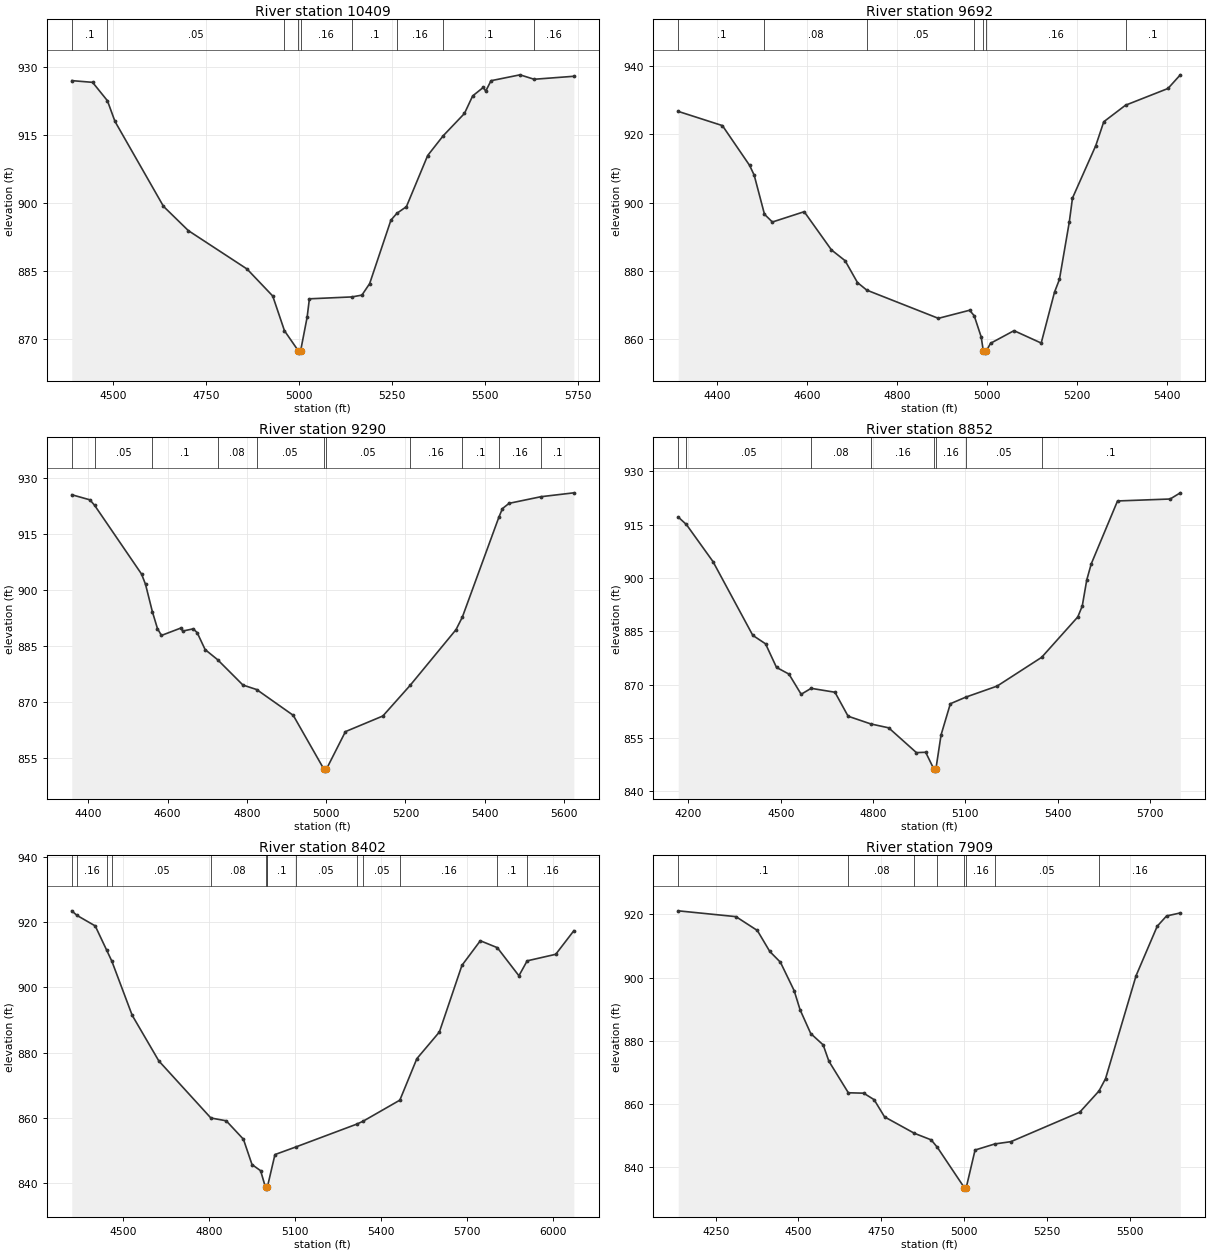
Type RM Length L Ch R = 1,10409,717,717,717
BEGIN DESCRIPTION:
FALL CREEK TRIB 1 23.0
END DESCRIPTION:
XS GIS Cut Line= 4
      2989066.32     10126039.51      2989102.78     10125617.61
      2989170.49     10125336.36      2988682.19     10124925.99
#Sta/Elev= 30
  4388.7  927.00  4444.7  926.62  4484.6  922.56  4504.9  917.99  4635.4  899.22
  4702.3  893.86  4860.1  885.38  4929.3  879.41  4960.9  871.73  4998.3  867.29
  5001.1  866.79  5004.3  867.29  5021.9  874.76  5027.9  878.79  5142.5  879.21
  5169.2  879.61  5190.0  882.15  5247.2  896.17  5263.2  897.68  5288.9  899.15
  5346.1  910.45  5387.7  914.80  5445.0  919.74  5467.1  923.62  5495.7  925.50
  5502.2  924.68  5516.5  926.98  5594.5  928.28  5632.4  927.30  5739.3  927.96
#Mann=9,-1,0
  4388.7     0.1       0  4484.6    0.05       0  4960.9    0.16       0
  4998.3    0.07       0  5004.3    0.16       0  5142.5     0.1       0
  5263.2    0.16       0  5387.7     0.1       0  5632.4    0.16       0
Bank Sta=4998.3,5004.3
Exp/Cntr=0.3,0.1

Type RM Length L Ch R = 1,9692,402,402,402
BEGIN DESCRIPTION:
FALL CREEK TRIB 1 22.0
END DESCRIPTION:
XS GIS Cut Line= 4
      2989847.57     10125700.93      2989769.45     10125128.03
      2989571.53     10125070.74      2989436.15     10124768.74
#Sta/Elev= 30
  4314.2  926.70  4412.3  922.54  4472.8  910.87  4482.9  908.02  4505.8  896.56
  4523.3  894.30  4594.0  897.32  4654.5  886.13  4684.8  882.98  4712.3  876.57
  4733.0  874.35  4892.0  866.09  4961.4  868.46  4971.6  866.85  4987.1  860.65
  4992.0  856.40  4994.8  855.90  4998.0  856.40  5007.9  858.78  5060.0  862.48
  5120.4  858.85  5150.0  873.77  5160.9  877.48  5182.8  894.29  5189.9  901.32
  5241.7  916.70  5259.4  923.67  5307.7  928.51  5402.0  933.41  5429.4  937.41
#Mann=7,-1,0
  4314.2     0.1       0  4505.8    0.08       0  4733.0    0.05       0
  4971.6    0.16       0  4992.0    0.07       0  4998.0    0.16       0
  5307.7     0.1       0
Bank Sta=4992,4998
Exp/Cntr=0.3,0.1

Type RM Length L Ch R = 1,9290,438,438,438
BEGIN DESCRIPTION:
FALL CREEK TRIB 1 21.0
END DESCRIPTION:
XS GIS Cut Line= 4
      2989915.28     10125659.33      2989951.74     10125101.99
      2990009.03     10124862.40      2989800.68     10124450.92
#Sta/Elev= 30
  4358.5  925.57  4404.2  924.20  4416.1  922.73  4534.5  904.30  4544.5  901.55
  4561.7  894.24  4574.6  889.69  4584.6  887.85  4633.4  889.83  4638.4  889.03
  4664.8  889.62  4674.8  888.59  4694.8  884.06  4726.4  881.34  4790.2  874.55
  4824.7  873.35  4917.0  866.44  4994.5  851.98  4997.2  851.48  5000.5  851.98
  5048.6  862.07  5143.0  866.26  5211.6  874.45  5327.5  889.41  5343.4  892.76
  5435.3  919.48  5444.5  921.85  5461.2  923.26  5541.6  925.04  5624.6  926.08
#Mann=11,-1,0
  4358.5     0.1       0  4416.1    0.05       0  4561.7     0.1       0
  4726.4    0.08       0  4824.7    0.05       0  4994.5   0.035       0
  5000.5    0.05       0  5211.6    0.16       0  5343.4     0.1       0
  5435.3    0.16       0  5541.6     0.1       0
Bank Sta=4994.5,5000.5
Exp/Cntr=0.3,0.1

Type RM Length L Ch R = 1,8852,450,450,450
BEGIN DESCRIPTION:
FALL CREEK TRIB 1 20.0
END DESCRIPTION:
XS GIS Cut Line= 4
      2990092.38     10125690.49      2990295.49     10125148.86
      2990269.45     10124695.74      2989790.27     10124336.36
#Sta/Elev= 30
  4167.0  917.16  4193.4  915.07  4279.8  904.64  4409.2  883.86  4450.7  881.47
  4486.3  874.83  4526.7  872.95  4566.4  867.27  4598.8  868.94  4676.2  867.84
  4718.9  861.09  4792.9  858.91  4850.8  857.82  4940.9  850.84  4971.0  850.94
  4998.0  846.13  5000.8  845.63  5004.0  846.13  5021.0  855.84  5051.1  864.60
  5101.8  866.48  5203.1  869.57  5347.8  877.67  5465.2  889.04  5479.7  892.11
  5494.3  899.44  5508.9  903.98  5594.3  921.69  5765.2  922.24  5798.3  923.98
#Mann=8,-1,0
  4167.0     0.1       0  4193.4    0.05       0  4598.8    0.08       0
  4792.9    0.16       0  4998.0    0.07       0  5004.0    0.16       0
  5101.8    0.05       0  5347.8     0.1       0
Bank Sta=4998,5004
Exp/Cntr=0.3,0.1

Type RM Length L Ch R = 1,8402,493,493,493
BEGIN DESCRIPTION:
FALL CREEK TRIB 1 19.0
END DESCRIPTION:
XS GIS Cut Line= 4
      2990920.48     10125544.68      2990696.53     10125211.36
      2990675.70     10124758.24      2990123.64     10124049.94
#Sta/Elev= 30
  4320.5  923.46  4338.5  922.07  4402.4  918.84  4442.4  911.41  4460.4  908.05
  4531.4  891.49  4624.4  877.52  4806.2  860.04  4859.8  859.18  4919.9  853.54
  4949.9  845.78  4980.0  843.89  4997.0  838.76  4999.7  838.26  5003.0  838.76
  5003.4  838.85  5030.0  848.84  5102.0  851.14  5315.0  858.14  5337.2  859.02
  5466.1  865.50  5525.5  878.20  5604.2  886.37  5682.9  906.76  5747.1  914.30
  5806.5  912.18  5881.9  903.58  5910.7  908.15  6010.4  910.15  6073.7  917.37
#Mann=14,-1,0
  4320.5    0.05       0  4338.5    0.16       0  4442.4     0.1       0
  4460.4    0.05       0  4806.2    0.08       0  4997.0    0.07       0
  5003.0    0.08       0  5003.4     0.1       0  5102.0    0.05       0
  5315.0     0.1       0  5337.2    0.05       0  5466.1    0.16       0
  5806.5     0.1       0  5910.7    0.16       0
Bank Sta=4997,5003
Exp/Cntr=0.3,0.1

Type RM Length L Ch R = 1,7909,474,474,474
BEGIN DESCRIPTION:
FALL CREEK TRIB 1 18.0
END DESCRIPTION:
XS GIS Cut Line= 4
      2991295.47     10125357.15      2991081.95     10124685.32
      2990753.82     10124534.28      2990416.06     10124238.09
#Sta/Elev= 30
  4137.1  921.11  4311.3  919.27  4375.8  914.90  4413.5  908.25  4445.5  904.86
  4487.0  895.87  4504.8  889.84  4537.0  882.31  4574.5  878.72  4591.9  873.54
  4650.5  863.58  4696.8  863.45  4728.3  861.40  4759.8  855.96  4850.0  850.76
  4900.5  848.69  4919.3  846.31  5000.4  833.61  5003.1  833.11  5006.4  833.61
  5033.0  845.47  5092.8  847.40  5141.2  848.12  5349.1  857.45  5407.1  864.15
  5426.9  868.06  5519.0  900.60  5582.8  916.24  5611.0  919.49  5652.5  920.44
#Mann=8,-1,0
  4137.1     0.1       0  4650.5    0.08       0  4850.0    0.05       0
  4919.3    0.16       0  5000.4    0.07       0  5006.4    0.16       0
  5092.8    0.05       0  5407.1    0.16       0
Bank Sta=5000.4,5006.4
Exp/Cntr=0.3,0.1

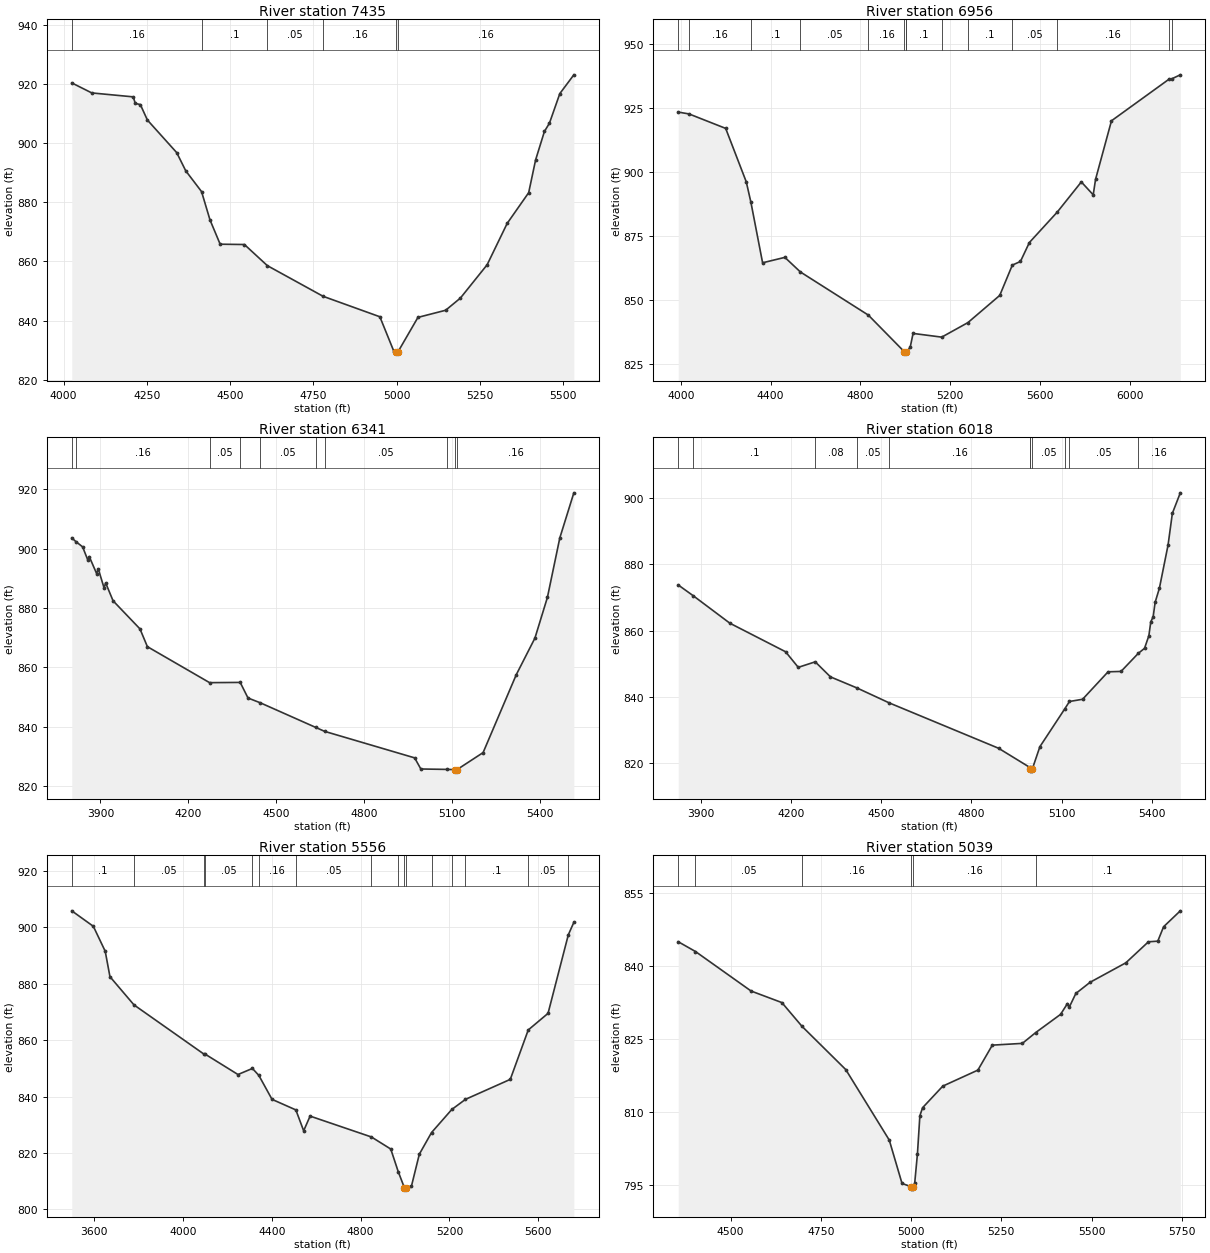
Type RM Length L Ch R = 1,7435,479,479,479
BEGIN DESCRIPTION:
FALL CREEK TRIB 1 17.0
END DESCRIPTION:
XS GIS Cut Line= 3
      2991764.22     10124851.96      2991394.45     10124268.65
      2990607.96     10124044.69
#Sta/Elev= 30
  4024.3  920.36  4084.5  916.97  4209.1  915.64  4215.0  913.42  4230.3  913.04
  4251.5  907.81  4339.6  896.79  4366.7  890.65  4414.2  883.62  4439.6  874.04
  4470.1  865.84  4543.0  865.73  4611.9  858.59  4779.5  848.22  4949.9  841.31
  4991.5  829.76  4998.7  829.52  5001.5  829.02  5004.7  829.52  5064.3  841.10
  5147.5  843.51  5191.8  847.62  5272.2  858.89  5332.4  872.87  5397.0  883.25
  5417.8  894.32  5444.3  903.95  5459.4  906.75  5490.6  916.75  5532.7  923.09
#Mann=6,-1,0
  4024.3    0.16       0  4414.2     0.1       0  4611.9    0.05       0
  4779.5    0.16       0  4998.7    0.07       0  5004.7    0.16       0
Bank Sta=4998.7,5004.7
Exp/Cntr=0.3,0.1

Type RM Length L Ch R = 1,6956,615,615,615
BEGIN DESCRIPTION:
FALL CREEK TRIB 1 16.0
END DESCRIPTION:
XS GIS Cut Line= 3
      2991920.47     10124596.75      2991196.53     10123612.40
      2990196.50     10123430.11
#Sta/Elev= 30
  3988.1  923.39  4036.1  922.67  4199.6  917.01  4291.4  896.09  4311.9  888.19
  4364.2  864.42  4463.5  866.54  4532.7  860.83  4835.6  843.95  4996.6  829.57
  4999.4  829.07  5002.6  829.57  5005.2  829.57  5005.4  829.57  5022.1  831.31
  5035.1  836.78  5162.8  835.33  5279.7  841.02  5421.5  851.66  5477.6  863.52
  5513.7  864.93  5553.6  872.35  5677.9  884.26  5785.2  896.06  5838.2  891.01
  5848.7  897.10  5919.6  919.98  6175.7  936.23  6190.7  936.50  6226.5  937.97
#Mann=15,-1,0
  3988.1     0.1       0  4036.1    0.16       0  4311.9     0.1       0
  4532.7    0.05       0  4835.6    0.16       0  4996.6    0.07       0
  5002.6    0.16       0  5005.2    0.05       0  5005.4     0.1       0
  5162.8    0.05       0  5279.7     0.1       0  5477.6    0.05       0
  5677.9    0.16       0  6175.7     0.1       0  6190.7    0.16       0
Bank Sta=4996.6,5002.6
Exp/Cntr=0.3,0.1

Type RM Length L Ch R = 1,6341,323,323,323
BEGIN DESCRIPTION:
FALL CREEK TRIB 1 14.0
END DESCRIPTION:
XS GIS Cut Line= 3
      2992262.50     10124348.50      2992019.45     10123680.11
      2991298.95     10122985.66
#Sta/Elev= 30
  3802.3  903.64  3816.4  902.40  3839.3  900.62  3856.6  896.28  3861.9  897.35
  3887.2  891.58  3892.5  893.25  3912.5  886.76  3917.8  888.48  3943.1  882.44
  4034.9  872.95  4060.1  866.97  4272.2  854.83  4376.6  854.91  4403.2  849.65
  4445.7  848.01  4633.9  839.74  4664.5  838.40  4971.4  829.46  4992.5  825.71
  5081.4  825.57  5109.7  825.49  5112.4  824.99  5115.7  825.49  5204.8  831.24
  5318.0  857.54  5381.5  869.85  5424.0  883.56  5466.4  903.66  5514.2  918.85
#Mann=10,-1,0
  3802.3     0.1       0  3816.4    0.16       0  4272.2    0.05       0
  4376.6     0.1       0  4445.7    0.05       0  4633.9    0.16       0
  4664.5    0.05       0  5081.4    0.16       0  5109.7   0.035       0
  5115.7    0.16       0
Bank Sta=5109.7,5115.7
Exp/Cntr=0.3,0.1

Type RM Length L Ch R = 1,6018,462,462,462
BEGIN DESCRIPTION:
Mapping XS a343164c
END DESCRIPTION:
XS GIS Cut Line= 4
      2992702.22     10123831.25      2992347.40     10123391.96
      2991851.79     10123149.79      2991499.80     10122724.58
#Sta/Elev= 30
  3825.7  873.70  3875.7  870.45  3997.4  862.19  4182.4  853.61  4224.5  848.92
  4280.9  850.58  4331.6  846.05  4419.1  842.74  4526.7  838.23  4890.1  824.58
  4993.4  818.85  4995.7  818.20  4998.5  817.70  5001.7  818.20  5027.4  825.05
  5110.0  836.42  5125.7  838.65  5169.3  839.32  5254.0  847.58  5297.0  847.69
  5354.5  853.14  5375.1  854.64  5389.5  858.43  5395.9  862.61  5403.8  864.13
  5410.3  868.47  5424.6  872.75  5453.3  885.72  5467.6  895.26  5494.0  901.42
#Mann=11,-1,0
  3825.7    0.16       0  3875.7     0.1       0  4280.9    0.08       0
  4419.1    0.05       0  4526.7    0.16       0  4993.4    0.05       0
  4995.7   0.035       0  5001.7    0.05       0  5110.0    0.16       0
  5125.7    0.05       0  5354.5    0.16       0
Bank Sta=4995.7,5001.7
Exp/Cntr=0.3,0.1

Type RM Length L Ch R = 1,5556,517,517,517
BEGIN DESCRIPTION:
FALL CREEK TRIB 1 13.0
END DESCRIPTION:
XS GIS Cut Line= 4
      2992920.48     10124004.74      2992607.99     10123171.43
      2991823.27     10122567.27      2991442.35     10122581.12
#Sta/Elev= 30
  3498.9  905.91  3596.1  900.41  3649.5  891.57  3670.9  882.53  3779.1  872.52
  4092.7  855.13  4099.2  855.06  4247.6  847.80  4312.6  849.96  4341.5  847.49
  4400.9  838.99  4508.2  835.24  4543.4  827.83  4572.4  833.04  4848.7  825.63
  4935.7  821.35  4969.4  813.32  4997.1  807.62  4999.8  807.12  5003.1  807.62
  5029.1  808.24  5064.4  819.52  5119.4  827.20  5210.6  835.39  5272.3  838.99
  5474.1  846.08  5555.0  863.62  5644.2  869.52  5735.5  897.40  5760.4  901.82
#Mann=16,-1,0
  3498.9     0.1       0  3779.1    0.05       0  4092.7     0.1       0
  4099.2    0.05       0  4312.6    0.08       0  4341.5    0.16       0
  4508.2    0.05       0  4848.7     0.1       0  4969.4    0.16       0
  4997.1    0.07       0  5003.1    0.16       0  5119.4     0.1       0
  5210.6    0.16       0  5272.3     0.1       0  5555.0    0.05       0
  5735.5     0.1       0
Bank Sta=4997.1,5003.1
Exp/Cntr=0.3,0.1

Type RM Length L Ch R = 1,5039,536,536,536
BEGIN DESCRIPTION:
FALL CREEK TRIB 1 12.0
END DESCRIPTION:
XS GIS Cut Line= 3
      2992877.09     10122890.19      2992325.00     10122270.39
      2991794.69     10122088.42
#Sta/Elev= 30
  4355.2  844.89  4403.0  842.88  4557.1  834.76  4642.3  832.39  4697.8  827.53
  4819.2  818.63  4939.7  804.15  4975.1  795.23  5000.6  794.57  5003.3  794.07
  5006.6  794.57  5010.2  795.30  5017.8  801.34  5024.5  809.14  5032.0  810.79
  5088.0  815.23  5185.2  818.52  5225.2  823.65  5308.4  824.01  5345.5  826.24
  5414.2  829.97  5433.4  832.20  5438.7  831.51  5456.5  834.26  5496.0  836.56
  5595.0  840.56  5657.6  844.88  5683.5  845.01  5699.6  847.97  5745.9  851.24
#Mann=6,-1,0
  4355.2    0.08       0  4403.0    0.05       0  4697.8    0.16       0
  5000.6    0.07       0  5006.6    0.16       0  5345.5     0.1       0
Bank Sta=5000.6,5006.6
Exp/Cntr=0.3,0.1

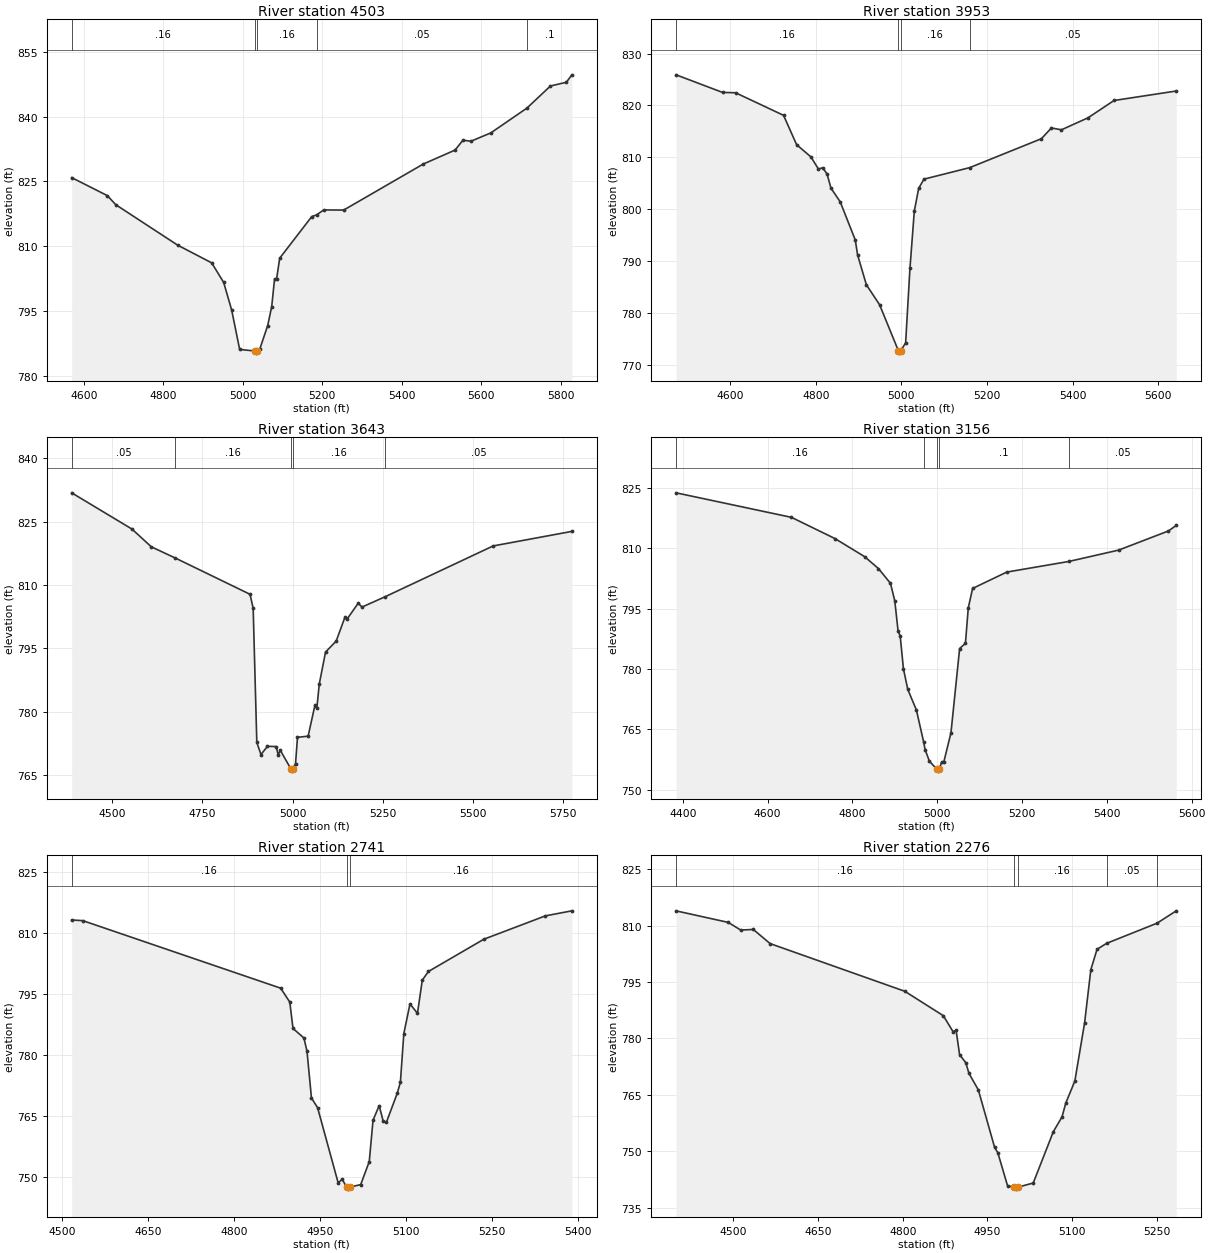
Type RM Length L Ch R = 1,4503,550,550,550
BEGIN DESCRIPTION:
FALL CREEK TRIB 1 10.0
END DESCRIPTION:
XS GIS Cut Line= 4
      2992981.28     10122197.50      2992731.25     10121968.31
      2992423.96     10122004.77      2991814.59     10122004.77
#Sta/Elev= 30
  4569.6  825.88  4659.1  821.73  4680.7  819.61  4836.1  810.28  4921.7  806.19
  4951.9  801.66  4972.0  795.27  4992.1  786.18  5029.4  785.83  5032.2  785.33
  5035.4  785.83  5042.5  786.23  5062.6  791.70  5072.7  796.10  5079.9  802.50
  5085.0  802.48  5092.8  807.27  5173.4  816.88  5185.5  817.27  5203.6  818.42
  5253.7  818.38  5453.7  829.01  5533.7  832.24  5553.7  834.52  5573.7  834.29
  5623.7  836.21  5714.5  841.94  5773.7  847.05  5813.7  847.91  5827.6  849.63
#Mann=5,-1,0
  4569.6    0.16       0  5029.4    0.07       0  5035.4    0.16       0
  5185.5    0.05       0  5714.5     0.1       0
Bank Sta=5029.4,5035.4
Exp/Cntr=0.3,0.1

Type RM Length L Ch R = 1,3953,310,310,310
BEGIN DESCRIPTION:
FALL CREEK TRIB 1 9.0
END DESCRIPTION:
XS GIS Cut Line= 3
      2993022.93     10122140.21      2992897.92     10121494.35
      2992429.19     10121291.23
#Sta/Elev= 30
  4473.7  825.91  4582.2  822.52  4612.7  822.45  4724.8  818.10  4755.3  812.44
  4788.8  810.08  4806.2  807.75  4816.4  807.99  4826.6  806.75  4835.5  804.07
  4857.2  801.41  4892.3  794.07  4897.9  791.14  4918.3  785.42  4949.2  781.57
  4992.9  772.74  4995.6  772.24  4998.9  772.74  5010.0  774.21  5020.1  788.57
  5030.3  799.64  5040.5  804.02  5052.8  805.79  5159.6  808.01  5327.2  813.59
  5350.6  815.66  5374.1  815.31  5436.1  817.62  5496.9  820.96  5642.4  822.79
#Mann=4,-1,0
  4473.7    0.16       0  4992.9    0.07       0  4998.9    0.16       0
  5159.6    0.05       0
Bank Sta=4992.9,4998.9
Exp/Cntr=0.3,0.1

Type RM Length L Ch R = 1,3643,487,487,487
BEGIN DESCRIPTION:
FALL CREEK TRIB 1 8.0
END DESCRIPTION:
XS GIS Cut Line= 3
      2993705.18     10121702.67      2992840.63     10121353.72
      2992403.34     10121228.78
#Sta/Elev= 30
  4387.4  831.80  4554.6  823.23  4608.3  819.03  4675.3  816.36  4882.1  807.80
  4890.7  804.48  4900.8  772.78  4912.3  769.91  4930.4  771.86  4954.5  771.80
  4959.9  769.90  4966.2  770.88  4995.5  766.49  4998.3  765.99  5001.5  766.49
  5008.2  767.78  5013.6  773.99  5043.1  774.26  5061.9  781.55  5067.2  780.82
  5074.0  786.58  5091.4  794.15  5120.9  796.74  5145.1  802.37  5150.5  801.87
  5181.9  805.69  5192.6  804.79  5255.9  807.20  5556.1  819.24  5774.5  822.68
#Mann=5,-1,0
  4387.4    0.05       0  4675.3    0.16       0  4995.5    0.07       0
  5001.5    0.16       0  5255.9    0.05       0
Bank Sta=4995.5,5001.5
Exp/Cntr=0.3,0.1

Type RM Length L Ch R = 1,3156,415,415,415
BEGIN DESCRIPTION:
FALL CREEK TRIB 1 7.0
END DESCRIPTION:
XS GIS Cut Line= 3
      2993684.41     10121150.61      2992866.67     10120989.14
      2992523.21     10121030.77
#Sta/Elev= 30
  4384.3  823.83  4656.3  817.73  4758.9  812.45  4828.7  807.96  4861.5  804.98
  4889.8  801.32  4900.0  796.94  4907.7  789.53  4912.8  788.16  4920.4  780.04
  4930.6  774.93  4951.0  769.77  4968.2  761.77  4971.4  759.96  4981.6  757.06
  4998.9  755.08  5001.7  754.58  5004.9  755.08  5010.2  756.78  5015.3  756.73
  5032.5  764.14  5052.9  785.09  5066.6  786.38  5073.3  795.21  5083.5  800.04
  5164.1  804.11  5310.3  806.75  5427.6  809.57  5545.1  814.33  5563.8  815.73
#Mann=5,-1,0
  4384.3    0.16       0  4968.2     0.1       0  4998.9    0.07       0
  5004.9     0.1       0  5310.3    0.05       0
Bank Sta=4998.9,5004.9
Exp/Cntr=0.3,0.1

Type RM Length L Ch R = 1,2741,465,465,465
BEGIN DESCRIPTION:
FALL CREEK TRIB 1 6.0
END DESCRIPTION:
XS GIS Cut Line= 2
      2993647.95     10120817.28      2992835.46     10120499.57
#Sta/Elev= 30
  4517.4  813.26  4536.9  813.09  4881.9  796.48  4897.8  793.06  4903.4  786.57
  4922.4  784.23  4927.8  780.99  4935.6  769.47  4946.3  767.07  4982.1  748.62
  4989.3  749.43  4997.0  747.54  4999.8  747.04  5003.0  747.54  5021.5  748.16
  5036.4  753.81  5043.0  764.00  5053.7  767.58  5060.8  763.72  5066.2  763.45
  5085.3  770.65  5090.7  773.33  5096.7  785.31  5107.4  792.60  5120.5  790.30
  5128.9  798.45  5139.6  800.59  5236.2  808.52  5343.6  814.27  5389.8  815.51
#Mann=3,-1,0
  4517.4    0.16       0  4997.0    0.07       0  5003.0    0.16       0
Bank Sta=4997,5003
Exp/Cntr=0.3,0.1

Type RM Length L Ch R = 1,2276,496,496,496
BEGIN DESCRIPTION:
FALL CREEK TRIB 1 5.0
END DESCRIPTION:
XS GIS Cut Line= 2
      2993715.62     10120817.24      2993336.28     10120017.00
#Sta/Elev= 30
  4398.8  813.92  4491.2  810.85  4513.3  808.81  4535.5  808.98  4565.2  805.22
  4803.7  792.54  4871.9  786.05  4889.1  781.81  4894.6  782.12  4900.7  775.71
  4911.7  773.53  4917.4  770.69  4933.9  766.32  4962.8  751.00  4968.4  749.62
  4985.6  740.85  4997.3  740.43  5000.0  739.93  5003.3  740.43  5031.1  741.55
  5066.7  755.20  5082.1  759.15  5088.8  762.83  5104.8  768.67  5122.0  784.08
  5133.1  798.29  5144.1  803.70  5161.0  805.28  5250.3  810.64  5284.4  813.93
#Mann=5,-1,0
  4398.8    0.16       0  4997.3    0.07       0  5003.3    0.16       0
  5161.0    0.05       0  5250.3     0.1       0
Bank Sta=4997.3,5003.3
Exp/Cntr=0.3,0.1

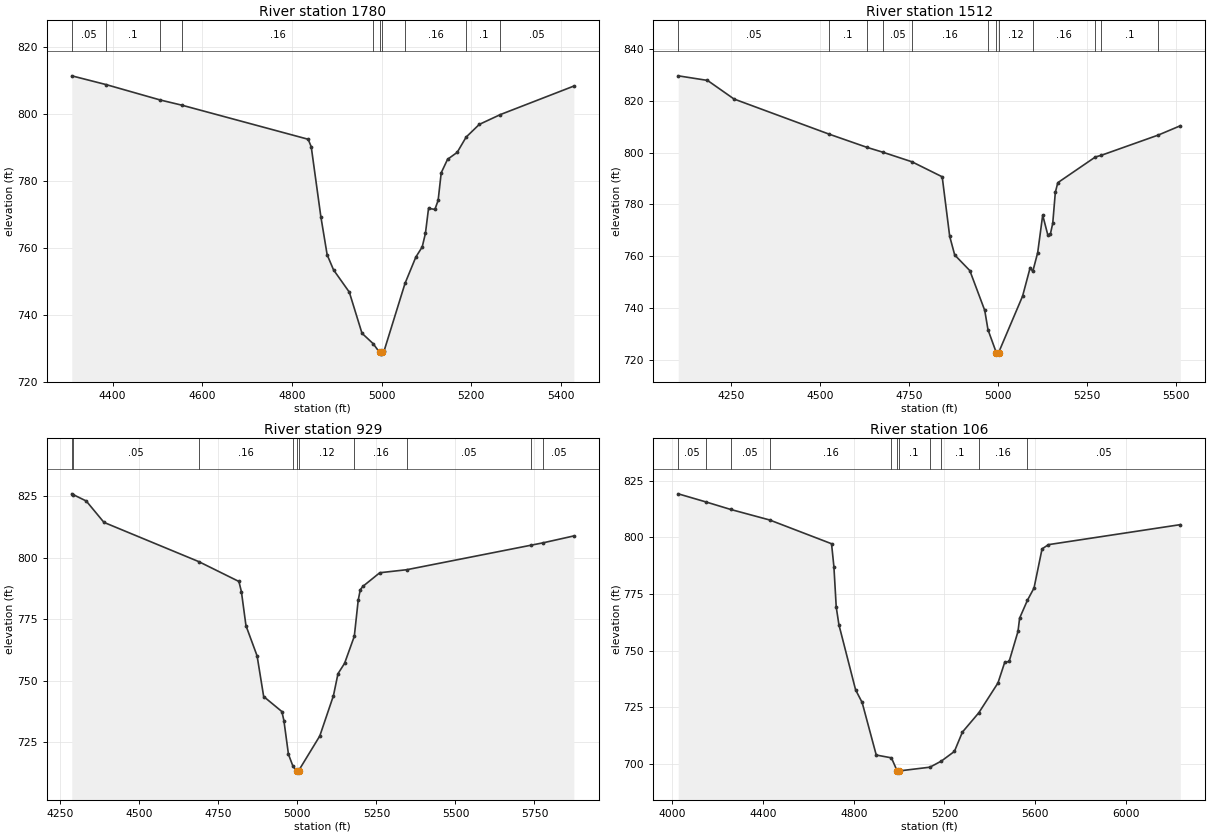
Type RM Length L Ch R = 1,1780,268,268,268
BEGIN DESCRIPTION:
FALL CREEK TRIB 1 4.0
END DESCRIPTION:
XS GIS Cut Line= 2
      2994361.45     10120536.01      2993585.41     10119728.72
#Sta/Elev= 30
  4308.8  811.38  4385.4  808.76  4506.4  804.15  4554.4  802.61  4836.0  792.43
  4842.9  790.18  4864.3  769.34  4878.4  757.92  4892.6  753.42  4927.8  746.76
  4956.1  734.47  4980.8  731.39  4995.5  728.74  4998.3  728.24  5001.5  728.74
  5005.5  729.24  5052.0  749.35  5076.2  757.24  5090.4  760.26  5097.6  764.33
  5104.5  771.77  5118.7  771.48  5125.9  774.16  5132.8  782.42  5147.0  786.45
  5168.4  788.51  5188.4  793.08  5217.7  796.87  5265.0  799.82  5428.6  808.32
#Mann=10,-1,0
  4308.8    0.05       0  4385.4     0.1       0  4506.4    0.05       0
  4554.4    0.16       0  4980.8    0.12       0  4995.5    0.07       0
  5001.5    0.12       0  5052.0    0.16       0  5188.4     0.1       0
  5265.0    0.05       0
Bank Sta=4995.5,5001.5
Exp/Cntr=0.3,0.1

Type RM Length L Ch R = 1,1512,583,583,583
BEGIN DESCRIPTION:
FALL CREEK TRIB 1 3.0
END DESCRIPTION:
XS GIS Cut Line= 4
      2994819.82     10120312.07      2994314.59     10120082.89
      2993856.25     10119640.18      2993644.84     10119578.30
#Sta/Elev= 30
  4100.7  829.62  4183.0  827.85  4257.7  820.66  4525.7  807.07  4632.0  801.98
  4676.1  800.13  4758.2  796.42  4843.2  790.63  4864.3  767.64  4878.4  760.44
  4920.9  754.41  4962.9  739.02  4972.0  731.58  4995.6  722.65  4998.3  722.15
  5001.6  722.65  5069.3  744.54  5090.7  755.57  5098.0  754.09  5111.8  761.33
  5125.9  775.81  5140.1  768.29  5147.3  768.39  5154.2  772.71  5161.4  784.59
  5168.4  788.36  5274.3  798.30  5290.8  798.93  5450.9  806.74  5513.0  810.33
#Mann=12,-1,0
  4100.7    0.05       0  4525.7     0.1       0  4632.0    0.16       0
  4676.1    0.05       0  4758.2    0.16       0  4972.0    0.12       0
  4995.6    0.07       0  5001.6    0.12       0  5098.0    0.16       0
  5274.3    0.05       0  5290.8     0.1       0  5450.9    0.05       0
Bank Sta=4995.6,5001.6
Exp/Cntr=0.3,0.1

Type RM Length L Ch R = 1,929,823,823,823
BEGIN DESCRIPTION:
FALL CREEK TRIB 1 2.0
END DESCRIPTION:
XS GIS Cut Line= 3
      2995007.29     10119858.93      2994246.88     10119244.35
      2993694.83     10119504.75
#Sta/Elev= 30
  4286.4  825.88  4290.6  825.58  4332.2  822.97  4388.2  814.29  4688.1  798.36
  4815.1  790.30  4823.0  786.15  4837.4  772.36  4872.6  760.09  4893.4  743.59
  4951.0  737.49  4957.4  733.82  4971.8  720.14  4986.1  715.28  4997.6  713.40
  5000.3  712.90  5003.6  713.40  5070.9  727.58  5114.1  743.95  5128.5  752.87
  5149.3  757.06  5180.1  768.05  5192.4  782.65  5198.9  786.91  5206.8  788.27
  5260.6  793.84  5345.8  795.07  5740.2  805.05  5776.8  805.98  5874.5  808.79
#Mann=10,-1,0
  4286.4    0.16       0  4290.6    0.05       0  4688.1    0.16       0
  4986.1    0.12       0  4997.6    0.07       0  5003.6    0.12       0
  5180.1    0.16       0  5345.8    0.05       0  5740.2     0.1       0
  5776.8    0.05       0
Bank Sta=4997.6,5003.6
Exp/Cntr=0.3,0.1

Type RM Length L Ch R = 1,106,0,0,0
BEGIN DESCRIPTION:
FALL CREEK TRIB 1 1.0
END DESCRIPTION:
XS GIS Cut Line= 4
      2995759.73     10118968.33      2994718.09     10118677.54
      2994366.53     10118816.42      2993837.00     10119354.63
#Sta/Elev= 30
  4026.1  819.16  4149.7  815.54  4257.1  812.28  4429.5  807.62  4702.3  797.15
  4712.7  787.04  4723.0  769.21  4734.9  761.39  4808.4  732.71  4837.2  727.16
  4899.5  703.97  4966.4  702.73  4991.9  696.93  4994.6  696.43  4997.9  696.93
  5136.2  698.61  5186.8  701.31  5244.2  705.56  5279.4  714.07  5352.0  722.63
  5436.3  735.75  5466.0  744.82  5485.6  745.24  5524.7  758.49  5531.8  764.33
  5566.5  772.27  5595.4  777.64  5630.8  794.88  5659.1  796.75  6240.6  805.57
#Mann=11,-1,0
  4026.1    0.05       0  4149.7     0.1       0  4257.1    0.05       0
  4429.5    0.16       0  4966.4     0.1       0  4991.9    0.07       0
  4997.9     0.1       0  5136.2    0.16       0  5186.8     0.1       0
  5352.0    0.16       0  5566.5    0.05       0
Bank Sta=4991.9,4997.9
Exp/Cntr=0.3,0.1

Chan Stop Cuts=-1