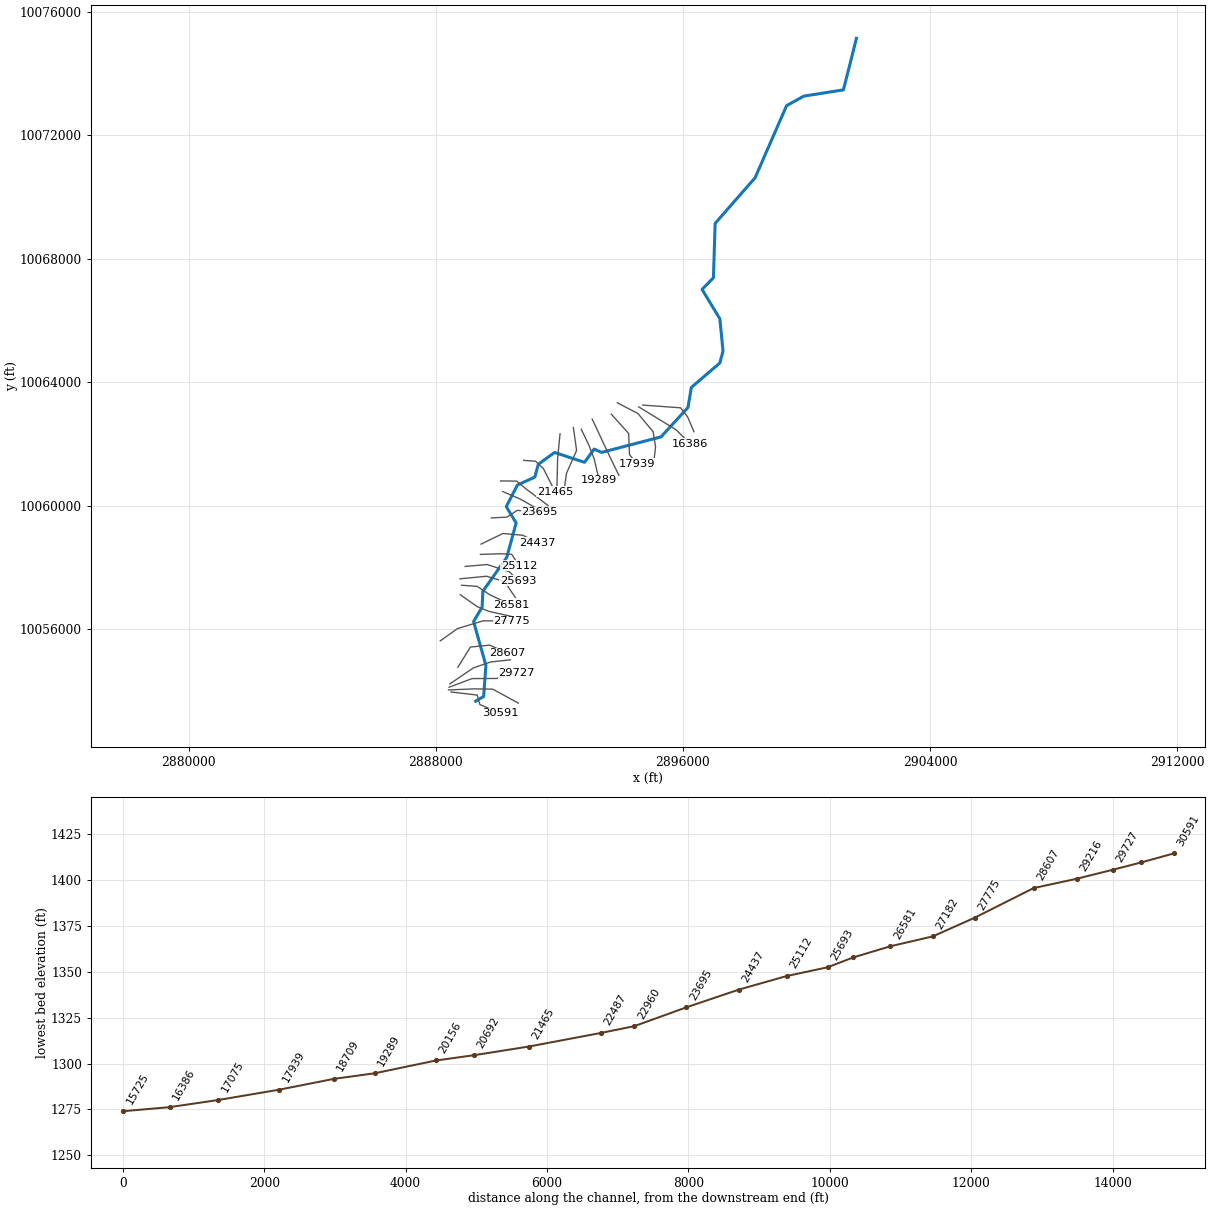
--- FLAT CREEK 2.prj (project) ---

Proj Title=FLAT CREEK 2 Base Level Engineering
Current Plan=p01
Default Exp/Contr=0.3,0.1
English Units
Geom File=g01
Flow File=f01
Plan File=p01
Y Axis Title=Elevation
X Axis Title(PF)=Main Channel Distance
X Axis Title(XS)=Station
BEGIN DESCRIPTION:
FLAT CREEK 2
END DESCRIPTION:
DSS File=dss
DSS Export Rating Curves= 0
DSS Export Rating Curve Sorted= 0
DSS Export Volume Flow Curves= 0
DXF OffsetX= 0
DXF OffsetY= 0
DXF ScaleX= 1
DXF ScaleY= 10

--- FLAT CREEK 2.p01 (plan) ---

Plan Title=Multiple Run
Short Identifier=Multiple
Geom File=g01
Flow File=f01
Subcritical Flow
K Sum by GR= 0
Std Step Tol= 0.01
Critical Tol= 0.01
Num of Std Step Trials= 20
Max Error Tol= 0.3
Flow Tol Ratio= 0.001
Split Flow NTrial= 30
Split Flow Tol= 0.02
Split Flow Ratio= 0.02
Log Output Level= 0
Friction Slope Method= 1
Unsteady Friction Slope Method= 2
Unsteady Bridges Friction Slope Method= 1
Parabolic Critical Depth
Global Vel Dist=  1 , 1 , 1
Global Log Level= 0
CheckData=True
Encroach Param= -1, 0, 0, 0
BEGIN DESCRIPTION:
Multiple Run
END DESCRIPTION:

--- FLAT CREEK 2.f01 (steady flow) ---

Flow Title=Multiple
Program Version=4.10
Number of Profiles= 7
Profile Names=10-year,25-year,50-year,1pct_min,100-year,1pct_plu,500-year
River Rch & RM=FLAT CREEK 2,Reach-1         ,30591
    1178    1754    2268    2150    2908    3933    4794
River Rch & RM=FLAT CREEK 2,Reach-1         ,30131
    1648    2479    3228    3075    4159    5624    6927
River Rch & RM=FLAT CREEK 2,Reach-1         ,23695
    2062    3133    4106    3933    5319    7193    8959
River Rch & RM=FLAT CREEK 2,Reach-1         ,20692
    2447    3742    4925    4733    6401    8657   10859
River Rch & RM=FLAT CREEK 2,Reach-1         ,17939
    2644    4047    5329    5121    6926    9367   11752
River Rch & RM=FLAT CREEK 2,Reach-1         ,14203
    3922    6098    8114    7870   10643   14393   18395
River Rch & RM=FLAT CREEK 2,Reach-1         ,13352
    3922    6098    8114    7870   10643   14393   18395
River Rch & RM=FLAT CREEK 2,Reach-1         ,10187
    4096    6369    8477    8222   11119   15037   19217
River Rch & RM=FLAT CREEK 2,Reach-1         ,6037
    4263    6627    8818    8548   11560   15634   19958
Boundary for River Rch & Prof#=FLAT CREEK 2,Reach-1         , 1
Up Type= 0
Dn Type= 3
Dn Slope=0.016
Boundary for River Rch & Prof#=FLAT CREEK 2,Reach-1         , 2
Up Type= 0
Dn Type= 3
Dn Slope=0.016
Boundary for River Rch & Prof#=FLAT CREEK 2,Reach-1         , 3
Up Type= 0
Dn Type= 3
Dn Slope=0.016
Boundary for River Rch & Prof#=FLAT CREEK 2,Reach-1         , 4
Up Type= 0
Dn Type= 3
Dn Slope=0.016
Boundary for River Rch & Prof#=FLAT CREEK 2,Reach-1         , 5
Up Type= 0
Dn Type= 3
Dn Slope=0.016
Boundary for River Rch & Prof#=FLAT CREEK 2,Reach-1         , 6
Up Type= 0
Dn Type= 3
Dn Slope=0.016
Boundary for River Rch & Prof#=FLAT CREEK 2,Reach-1         , 7
Up Type= 0
Dn Type= 3
Dn Slope=0.016
DSS Import GetInterval= 0
DSS Import GetPeak= 0
DSS Import FillOption= 0

--- FLAT CREEK 2.g01 (geometry) ---

Geom Title=Existing Conditions
Program Version=4.10

River Reach=FLAT CREEK 2    ,Reach-1
Reach XY= 30
      2889288.47     10053663.73      2889545.69     10053814.94
      2889618.81      10054820.4      2889219.83     10056244.77
      2889496.07     10056709.27      2889520.03     10057223.09
      2890295.05      10058325.1      2890597.58     10059438.72
      2890278.25     10059968.71      2890639.36     10060666.97
      2891202.15       10060924.      2891316.04     10061340.08
      2891843.79     10061722.99      2892812.14     10061403.66
      2893124.57     10061831.97      2893362.65     10061725.48
       2895288.2     10062226.73      2896162.86     10063181.43
      2896271.84     10063832.34      2897194.15     10064620.18
      2897297.64     10065009.07      2897195.78     10066052.62
      2896619.17     10067008.47      2896987.32     10067383.73
      2897042.77     10069146.67       2898336.1     10070624.53
      2899356.12     10072961.53      2899914.18     10073271.44
      2901197.63     10073473.65      2901618.47     10075143.73

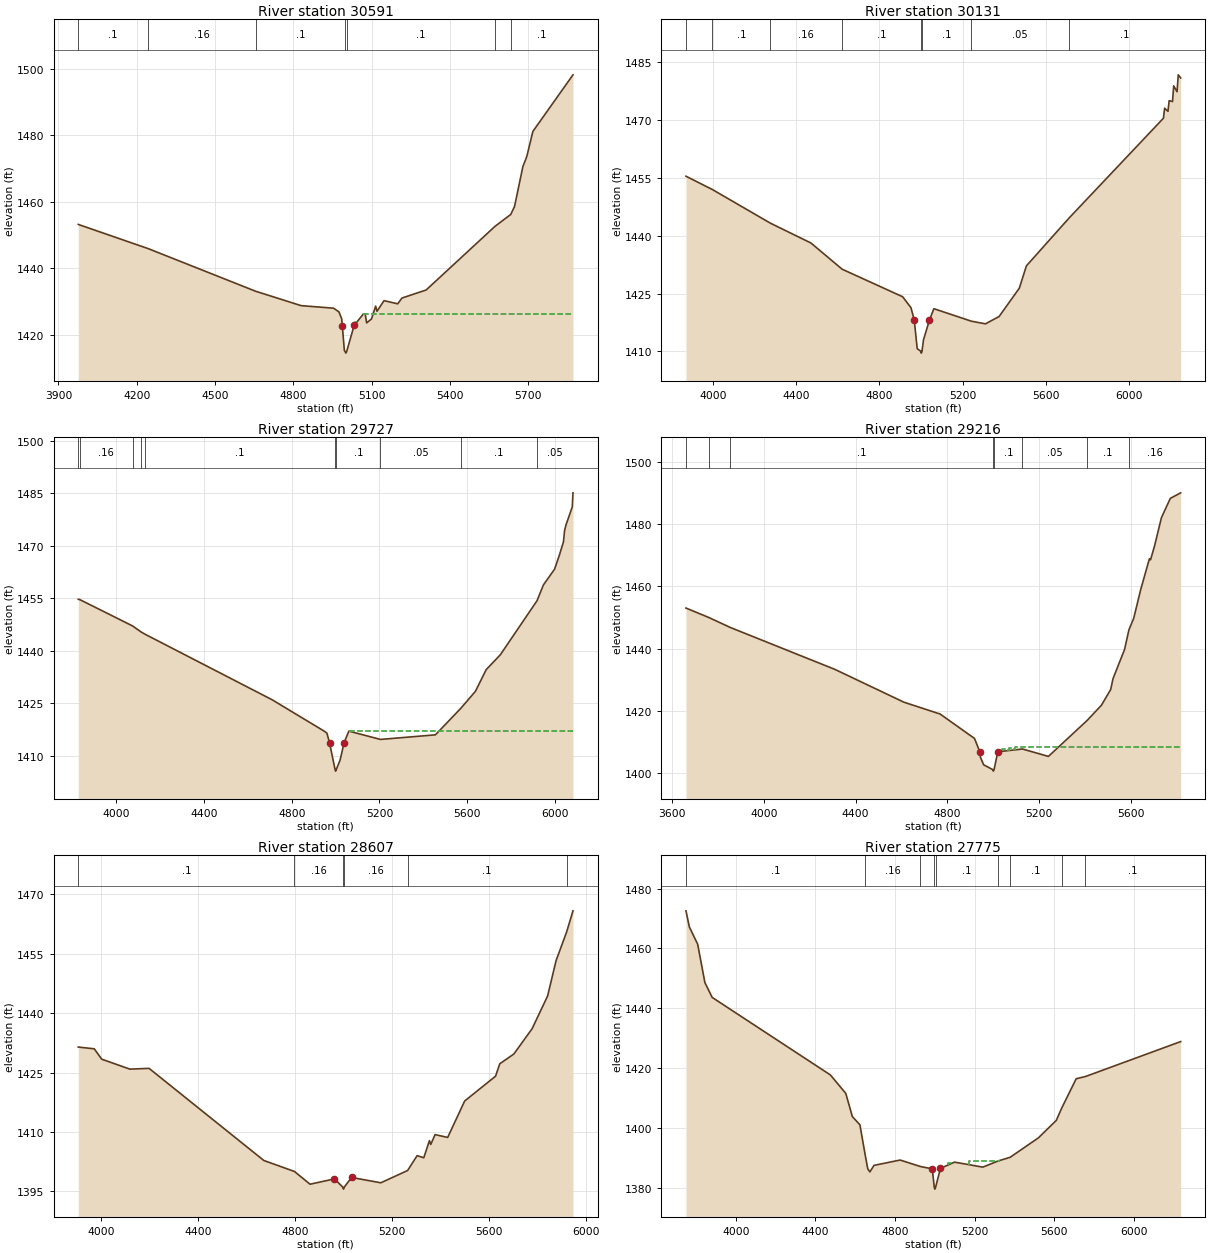
Type RM Length L Ch R = 1 ,30591   ,460,460,460
BEGIN DESCRIPTION:
FLAT CREEK 2 64.0
END DESCRIPTION:
XS GIS Cut Line= 4
      2888488.26     10053961.57      2889338.91     10053860.88
      2889422.24     10053555.33      2890084.42     10053267.57
#Sta/Elev= 30
    3976 1453.17  4243.8 1445.89  4655.2 1433.08  4829.8 1428.74    4954 1427.98
  4974.7 1426.86  4985.1  1424.8 4987.46  1422.7  4995.5 1415.23  4998.3 1414.96
    5001 1414.46  5004.3 1414.96 5032.83 1422.78    5068 1426.22  5075.6 1426.12
  5080.8 1423.55  5099.1 1424.72  5115.3 1428.59  5120.5 1427.05  5147.5 1430.25
  5199.7 1429.29    5216 1431.02  5308.7 1433.45  5572.8 1452.61  5632.7 1456.16
  5647.4 1458.56  5679.5 1470.62  5694.3 1473.58  5717.7 1481.15  5871.3 1498.16
#Mann= 7 ,-1 , 0
    3976      .1       0  4243.8     .16       0  4655.2      .1       0
  4998.3     .07       0  5004.3      .1       0  5572.8     .05       0
  5632.7      .1       0
#XS Ineff= 2 ,-1
  5035.7 5051.05 1423.82 5068.08  5871.3 1426.29
Permanent Ineff=
       T       T
Bank Sta=4987.46,5032.83
XS Rating Curve= 0 ,0
Exp/Cntr=0.3,0.1

Type RM Length L Ch R = 1 ,30131   ,404,404,404
BEGIN DESCRIPTION:
FLAT CREEK 2 63.0
END DESCRIPTION:
XS GIS Cut Line= 4
      2888408.33     10054027.55      2889262.52     10054062.27
      2889842.38     10054051.85      2890668.79     10053600.46
#Sta/Elev= 30
  3871.2 1455.47  3998.6    1452  4276.5 1443.29  4471.8 1438.13  4621.7 1431.33
  4912.1 1424.19  4952.1 1421.34 4967.61 1418.25  4982.1 1410.71  4999.1 1410.06
  5001.8 1409.56  5005.1 1410.06  5012.1 1412.99 5040.91 1418.14  5062.1 1421.09
  5242.6 1417.84  5309.9 1417.16  5375.4 1419.06  5472.5  1426.4  5506.7 1432.21
  5711.1 1444.59  6164.9 1470.52  6170.6 1473.12  6186.7 1472.32  6192.4 1475.07
  6208.5 1474.85  6214.2 1478.92  6230.3 1477.39    6236 1481.78  6247.7 1480.97
#Mann= 8 ,-1 , 0
  3871.2     .16       0  3998.6      .1       0  4276.5     .16       0
  4621.7      .1       0  4999.1     .07       0  5005.1      .1       0
  5242.6     .05       0  5711.1      .1       0
#XS Ineff= 2 , 0
                          5062.1         1421.09
Permanent Ineff=
       T       T
Bank Sta=4967.61,5040.91
XS Rating Curve= 0 ,0
Exp/Cntr=0.3,0.1

Type RM Length L Ch R = 1 ,29727   ,511,511,511
BEGIN DESCRIPTION:
FLAT CREEK 2 62.0
END DESCRIPTION:
XS GIS Cut Line= 4
      2888425.72     10054114.36      2889172.24      10054395.6
      2889963.91     10054399.08      2890608.78     10054568.96
#Sta/Elev= 30
  3826.4 1454.67  3833.5 1454.58  4074.5 1447.04  4113.3 1445.31  4132.1 1444.65
  4710.4 1425.96  4950.4  1416.9  4960.4 1416.41 4972.49 1413.65  4997.4 1406.06
  5000.1 1405.56  5003.4 1406.06  5020.4  1408.7 5038.86 1413.68  5060.4    1417
  5204.6 1414.62  5455.2 1415.93  5570.9  1423.5  5637.7 1428.37  5686.7 1434.55
  5751.5 1438.83  5918.7 1454.27  5947.9 1458.78  5998.9 1463.31  6020.3 1467.22
  6039.2 1471.07  6044.4 1474.33  6051.3 1476.02  6079.5 1481.09  6082.7  1485.1
#Mann= 10 ,-1 , 0
  3826.4      .1       0  3833.5     .16       0  4074.5      .1       0
  4113.3     .16       0  4132.1      .1       0  4997.4     .07       0
  5003.4      .1       0  5204.6     .05       0  5570.9      .1       0
  5918.7     .05       0
#XS Ineff= 2 , 0
                         5060.38         1417.02
Permanent Ineff=
       T       T
Bank Sta=4972.49,5038.86
XS Rating Curve= 0 ,0
Exp/Cntr=0.3,0.1

Type RM Length L Ch R = 1 ,29216   ,609,609,609
BEGIN DESCRIPTION:
FLAT CREEK 2 61.0
END DESCRIPTION:
XS GIS Cut Line= 4
      2888450.01     10054221.99      2889217.38     10054742.83
      2889776.41      10054933.8      2890411.84     10055003.25
#Sta/Elev= 30
    3660 1453.04  3759.1 1450.02  3852.6 1446.82  4308.9 1433.35  4610.4 1422.79
  4768.2 1418.99  4918.2 1411.15  4941.3 1406.88  4944.3 1405.06  4958.4 1402.66
  4997.7 1401.14  5000.5 1400.64  5003.7 1401.14 5020.02 1406.85  5127.5 1407.75
  5240.6 1405.37    5409 1416.89    5472 1421.83  5512.2 1426.87  5522.3 1430.34
  5572.6 1439.71  5591.6 1446.01  5612.8  1449.8    5643 1458.95    5681 1468.87
    5686 1468.54  5703.4 1472.98  5733.5 1482.08  5772.3 1488.28  5817.4 1490.06
#Mann= 8 ,-1 , 0
    3660      .1       0  3759.1     .16       0  3852.6      .1       0
  4997.7     .07       0  5003.7      .1       0  5127.5     .05       0
    5409      .1       0  5591.6     .16       0
#XS Ineff= 3 ,-1
 5037.99 5065.57 1407.86 5069.67 5091.62 1408.16 5095.95  5817.4 1408.39
Permanent Ineff=
       T       T       T
Bank Sta=4941.3,5020.02
XS Rating Curve= 0 ,0
Exp/Cntr=0.3,0.1

Type RM Length L Ch R = 1 ,28607   ,832,832,832
BEGIN DESCRIPTION:
FLAT CREEK 2 59.0
END DESCRIPTION:
XS GIS Cut Line= 4
      2888710.42     10054760.16      2889116.69     10055416.44
      2889738.21     10055478.94      2890324.01     10055218.97
#Sta/Elev= 30
  3907.4 1431.46  3973.2 1431.02    4004  1428.4  4119.8 1425.89    4199 1426.08
  4671.7 1402.81  4797.7 1400.04  4861.9 1396.82  4962.4 1398.17  4996.8 1396.08
  4999.6 1395.58  5002.8 1396.08  5032.8 1398.53  5153.4 1397.18  5263.6 1400.28
  5302.9 1404.04  5330.3  1403.5  5353.6 1407.83    5359 1406.86  5376.8 1409.35
  5428.8 1408.64  5498.6 1417.83  5625.9  1424.1  5643.3 1427.24  5701.2  1429.7
  5776.5  1436.1  5840.3 1444.37    5875 1453.26  5918.3 1460.48  5944.8 1465.87
#Mann= 6 ,-1 , 0
  3907.4      .1       0  4797.7     .16       0  4996.8     .07       0
  5002.8     .16       0  5263.6      .1       0  5918.3     .16       0
Bank Sta=4962.4,5032.8
XS Rating Curve= 0 ,0
Exp/Cntr=0.3,0.1

Type RM Length L Ch R = 1 ,27775   ,593,593,593
BEGIN DESCRIPTION:
FLAT CREEK 2 58.0
END DESCRIPTION:
XS GIS Cut Line= 4
      2888140.97     10055617.81      2888696.55     10056013.66
      2889529.88     10056267.13      2890463.72     10056256.72
#Sta/Elev= 30
  3748.8 1472.55  3765.9 1467.16  3807.7 1461.37    3844 1448.55  3880.8 1443.58
  4474.8 1417.66  4552.3 1411.48  4585.2 1403.74  4623.3 1400.98    4651 1390.47
  4662.9 1386.24  4673.4 1385.22  4694.3 1387.41  4825.7 1389.19  4927.2 1387.03
    4987 1386.24  4997.4 1379.96  5000.2 1379.46  5003.4 1379.96  5028.1 1386.39
    5099 1388.49  5240.9 1386.82  5319.8 1388.91  5378.3  1390.1  5520.6 1396.61
  5610.6 1402.45  5637.7 1406.55  5710.6 1416.38  5757.3 1417.13  6235.9 1428.81
#Mann= 9 ,-1 , 0
  3748.8      .1       0    4651     .16       0  4927.2      .1       0
  4997.4     .07       0  5003.4      .1       0  5319.8     .05       0
  5378.3      .1       0  5637.7     .05       0  5757.3      .1       0
#XS Ineff= 3 ,-1
  3748.8  4825.8 1389.18 5065.56 5090.19 1388.07 5170.62 5327.44 1388.94
Permanent Ineff=
       T       T       T
Bank Sta=4987,5028.1
XS Rating Curve= 0 ,0
Exp/Cntr=0.3,0.1

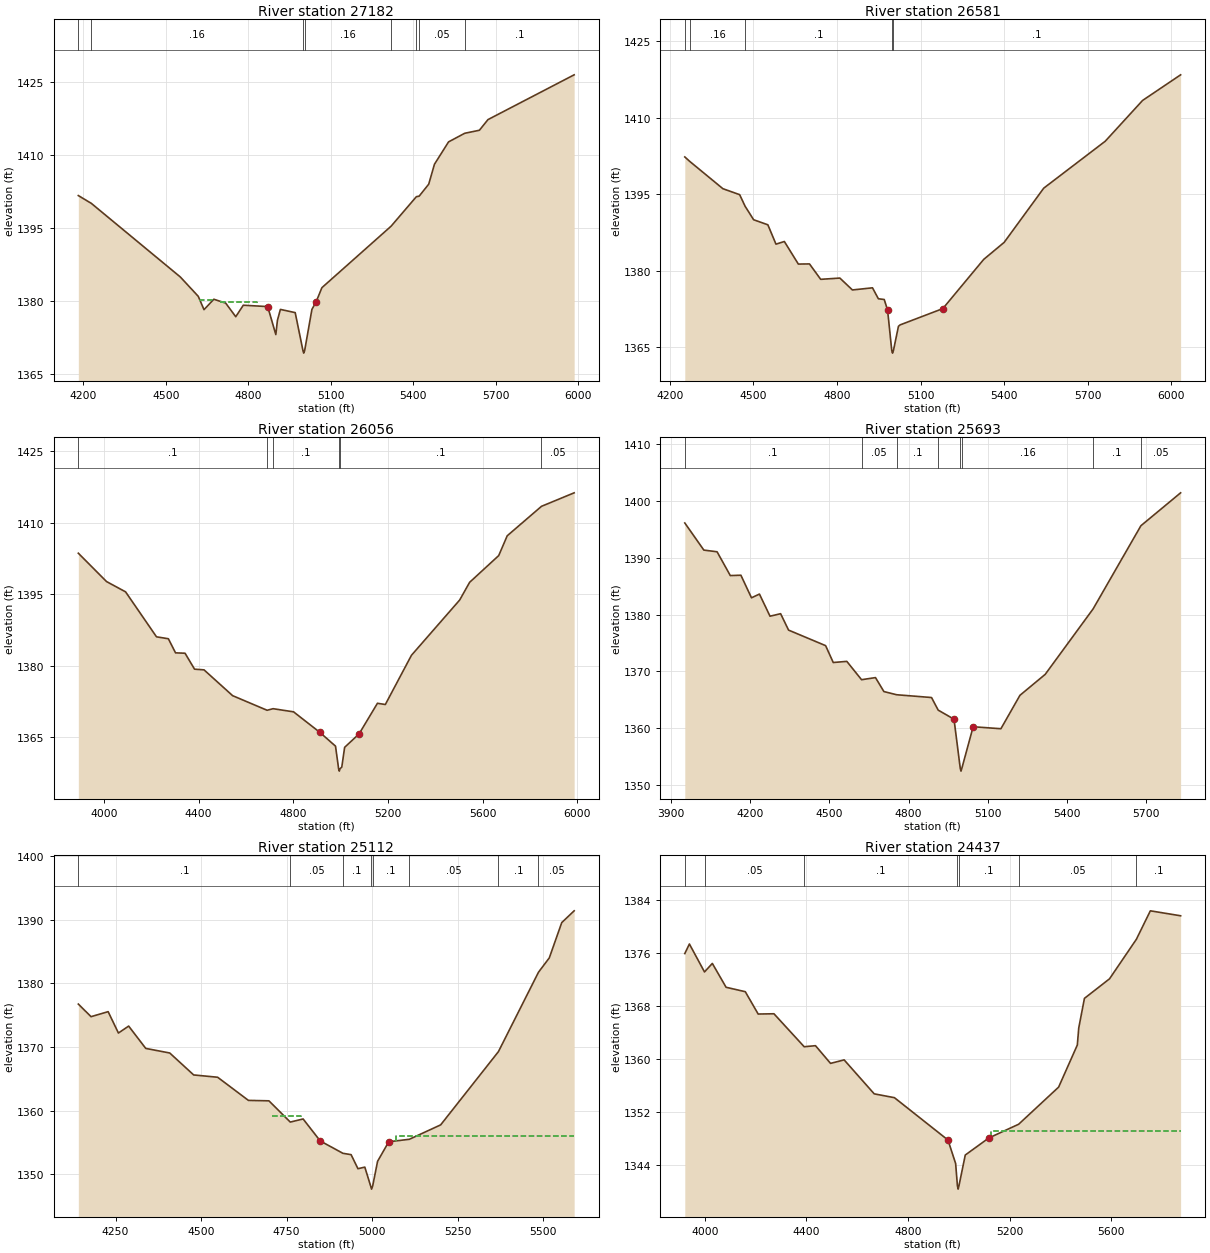
Type RM Length L Ch R = 1 ,27182   ,601,601,601
BEGIN DESCRIPTION:
FLAT CREEK 2 56.0
END DESCRIPTION:
XS GIS Cut Line= 4
      2888790.29     10057112.62      2889337.17      10056727.2
      2889722.59     10056570.95      2890424.63     10056414.94
#Sta/Elev= 30
  4181.6 1401.68  4228.8 1400.08  4552.5 1384.95    4618 1380.96  4638.9 1378.22
  4674.6 1380.36  4717.7 1379.57  4754.4 1376.77  4781.8 1379.13  4870.7 1378.85
  4900.2 1373.09    4906 1376.02  4916.8 1378.27  4970.7 1377.61    4999 1369.78
  5001.7 1369.28    5005 1369.78  5031.5 1378.27  5046.3 1379.76  5067.9 1382.74
  5319.6 1395.38  5411.6 1401.45  5421.7 1401.56  5456.5 1404.02  5477.4 1408.12
  5528.7 1412.72  5587.5 1414.49  5640.9 1415.11  5672.1  1417.3  5985.7 1426.51
#Mann= 8 ,-1 , 0
  4181.6      .1       0  4228.8     .16       0    4999     .07       0
    5005     .16       0  5319.6      .1       0  5411.6     .16       0
  5421.7     .05       0  5587.5      .1       0
#XS Ineff= 2 ,-1
    4625 4668.18 1380.24 4698.86 4832.95  1379.8
Permanent Ineff=
       T       T
Bank Sta=4870.7,5046.3
XS Rating Curve= 0 ,0
Exp/Cntr=0.3,0.1

Type RM Length L Ch R = 1 ,26581   ,525,525,525
BEGIN DESCRIPTION:
FLAT CREEK 2 55.0
END DESCRIPTION:
XS GIS Cut Line= 4
      2888831.98     10057419.91      2889337.17     10057383.45
      2889743.42     10057112.62      2890451.72     10056774.09
#Sta/Elev= 30
  4253.6 1402.31  4271.3 1401.44  4390.4 1396.09  4450.6 1394.92  4469.8 1392.68
  4500.7 1390.01  4551.8 1389.02  4580.9 1385.23    4611 1385.75  4661.1 1381.33
  4701.2 1381.36  4741.4 1378.34  4810.2 1378.59  4855.3 1376.26  4927.4 1376.68
  4948.4 1374.54  4969.5 1374.39 4981.53 1372.32  4996.5 1364.39  4999.2 1363.89
  5002.5 1364.39  5020.5 1369.14  5026.5 1369.42  5179.8 1372.61  5326.5 1382.24
    5400 1385.58  5542.1  1396.2  5762.9 1405.39  5896.8 1413.37  6033.4 1418.39
#Mann= 5 ,-1 , 0
  4253.6      .1       0  4271.3     .16       0  4469.8      .1       0
  4996.5     .07       0  5002.5      .1       0
Bank Sta=4981.53,5179.8
XS Rating Curve= 0 ,0
Exp/Cntr=0.3,0.1

Type RM Length L Ch R = 1 ,26056   ,363,363,363
BEGIN DESCRIPTION:
FLAT CREEK 2 54.0
END DESCRIPTION:
XS GIS Cut Line= 4
      2888779.92     10057628.25      2889639.26     10057711.58
      2890222.59      10057539.7      2890571.55     10057024.08
#Sta/Elev= 30
  3891.8 1403.61  4010.9 1397.65  4091.3 1395.49  4221.9 1386.04  4272.1 1385.63
  4302.3 1382.67  4342.5 1382.59  4382.6 1379.24  4422.8 1379.09  4543.4 1373.67
  4689.1  1370.6  4714.4 1370.93  4800.9 1370.27  4911.3 1365.98    4978 1363.06
  4991.1 1358.31  4993.9 1357.81  4997.1 1358.31  5004.5 1358.66  5016.5 1362.81
  5077.5 1365.63  5155.1 1372.07  5188.4 1371.81  5298.8 1382.16  5502.4 1393.77
  5544.4 1397.49  5667.3 1403.11  5703.2 1407.27  5847.8 1413.46  5985.9  1416.3
#Mann= 6 ,-1 , 0
  3891.8      .1       0  4689.1     .16       0  4714.4      .1       0
  4991.1     .07       0  4997.1      .1       0  5847.8     .05       0
Bank Sta=4911.3,5077.5
XS Rating Curve= 0 ,0
Exp/Cntr=0.3,0.1

Type RM Length L Ch R = 1 ,25693   ,581,581,581
BEGIN DESCRIPTION:
FLAT CREEK 2 53.0
END DESCRIPTION:
XS GIS Cut Line= 4
      2888946.58     10058029.29      2889660.09     10058091.79
      2890378.84     10057857.41      2890664.35     10057566.71
#Sta/Elev= 30
  3951.9 1396.17  4024.1 1391.39  4074.3 1391.09  4124.4  1386.9  4164.6 1386.96
  4204.7 1382.98  4234.9 1383.64    4275 1379.74  4315.2 1380.18  4345.3 1377.29
  4485.8 1374.55  4514.7 1371.58  4566.1 1371.78    4622 1368.55  4674.8 1368.92
  4706.7 1366.46  4754.9  1365.9  4887.3 1365.41  4912.5 1363.19  4972.5 1361.59
  4996.2 1352.94  4998.9 1352.44  5002.2 1352.94  5045.1 1360.26  5150.3 1359.91
  5222.5  1365.8  5318.2 1369.49  5499.9 1381.03    5681 1395.68  5831.6 1401.48
#Mann= 8 ,-1 , 0
  3951.9      .1       0    4622     .05       0  4754.9      .1       0
  4912.5     .16       0  4996.2     .07       0  5002.2     .16       0
  5499.9      .1       0    5681     .05       0
#XS Ineff= 2 , 0
                         5053.98         1359.99
Permanent Ineff=
       T       T
Bank Sta=4972.5,5045.1
XS Rating Curve= 0 ,0
Exp/Cntr=0.3,0.1

Type RM Length L Ch R = 1 ,25112   ,675,675,675
BEGIN DESCRIPTION:
FLAT CREEK 2 52.0
END DESCRIPTION:
XS GIS Cut Line= 4
      2889441.32     10058419.91      2890128.84     10058440.74
      2890456.96     10058419.91      2890691.32     10058055.36
#Sta/Elev= 30
  4141.1 1376.74  4178.3 1374.76  4228.3 1375.55  4258.3 1372.19  4288.3 1373.28
  4338.3 1369.77  4408.4 1369.05  4478.4  1365.6  4548.4 1365.24  4638.5  1361.6
  4698.5 1361.53  4760.9 1358.19  4798.5 1358.68  4848.6 1355.22  4914.9 1353.28
  4938.8 1353.07  4958.8 1350.86  4978.9 1351.11  4995.9 1348.15  4998.6 1347.65
  5001.9 1348.15  5016.2 1352.02    5049  1355.1  5108.9 1355.48  5200.7 1357.75
  5369.6 1369.26  5486.8 1381.75  5518.4    1384  5554.8 1389.55  5591.1  1391.4
#Mann= 8 ,-1 , 0
  4141.1      .1       0  4760.9     .05       0  4914.9      .1       0
  4995.9     .07       0  5001.9      .1       0  5108.9     .05       0
  5369.6      .1       0  5486.8     .05       0
#XS Ineff= 2 ,-1
 4708.18 4792.73 1359.15 5069.01  5591.1    1356
Permanent Ineff=
       T       T
Bank Sta=4848.6,5049
XS Rating Curve= 0 ,0
Exp/Cntr=0.3,0.1

Type RM Length L Ch R = 1 ,24437   ,742,742,742
BEGIN DESCRIPTION:
FLAT CREEK 2 50.0
END DESCRIPTION:
XS GIS Cut Line= 4
       2889462.2     10058753.26      2890170.51     10059096.99
      2890816.34      10059039.7       2891274.1     10058800.42
#Sta/Elev= 30
  3921.2 1375.93  3939.3 1377.38  3998.8 1373.15  4029.6 1374.44  4083.8 1370.83
  4159.4 1370.16  4210.1 1366.78  4272.2 1366.82  4391.3 1361.83  4435.8 1361.99
    4495 1359.31  4548.6 1359.84    4667  1354.7  4746.6 1354.12  4957.4 1347.71
  4987.6 1344.15  4994.6 1340.78  4997.3 1340.28  5000.6 1340.78  5025.5 1345.44
  5118.1 1348.02  5235.7  1350.1  5393.1 1355.72  5466.7 1362.09  5472.3 1364.67
  5494.7 1369.15  5593.5 1372.11  5699.3  1378.1  5754.2  1382.4  5873.4 1381.65
#Mann= 7 ,-1 , 0
  3921.2      .1       0  3998.8     .05       0  4391.3      .1       0
  4994.6     .07       0  5000.6      .1       0  5235.7     .05       0
  5699.3      .1       0
#XS Ineff= 2 , 0
                         5127.84         1349.01
Permanent Ineff=
       T       T
Bank Sta=4957.4,5118.1
XS Rating Curve= 0 ,0
Exp/Cntr=0.3,0.1

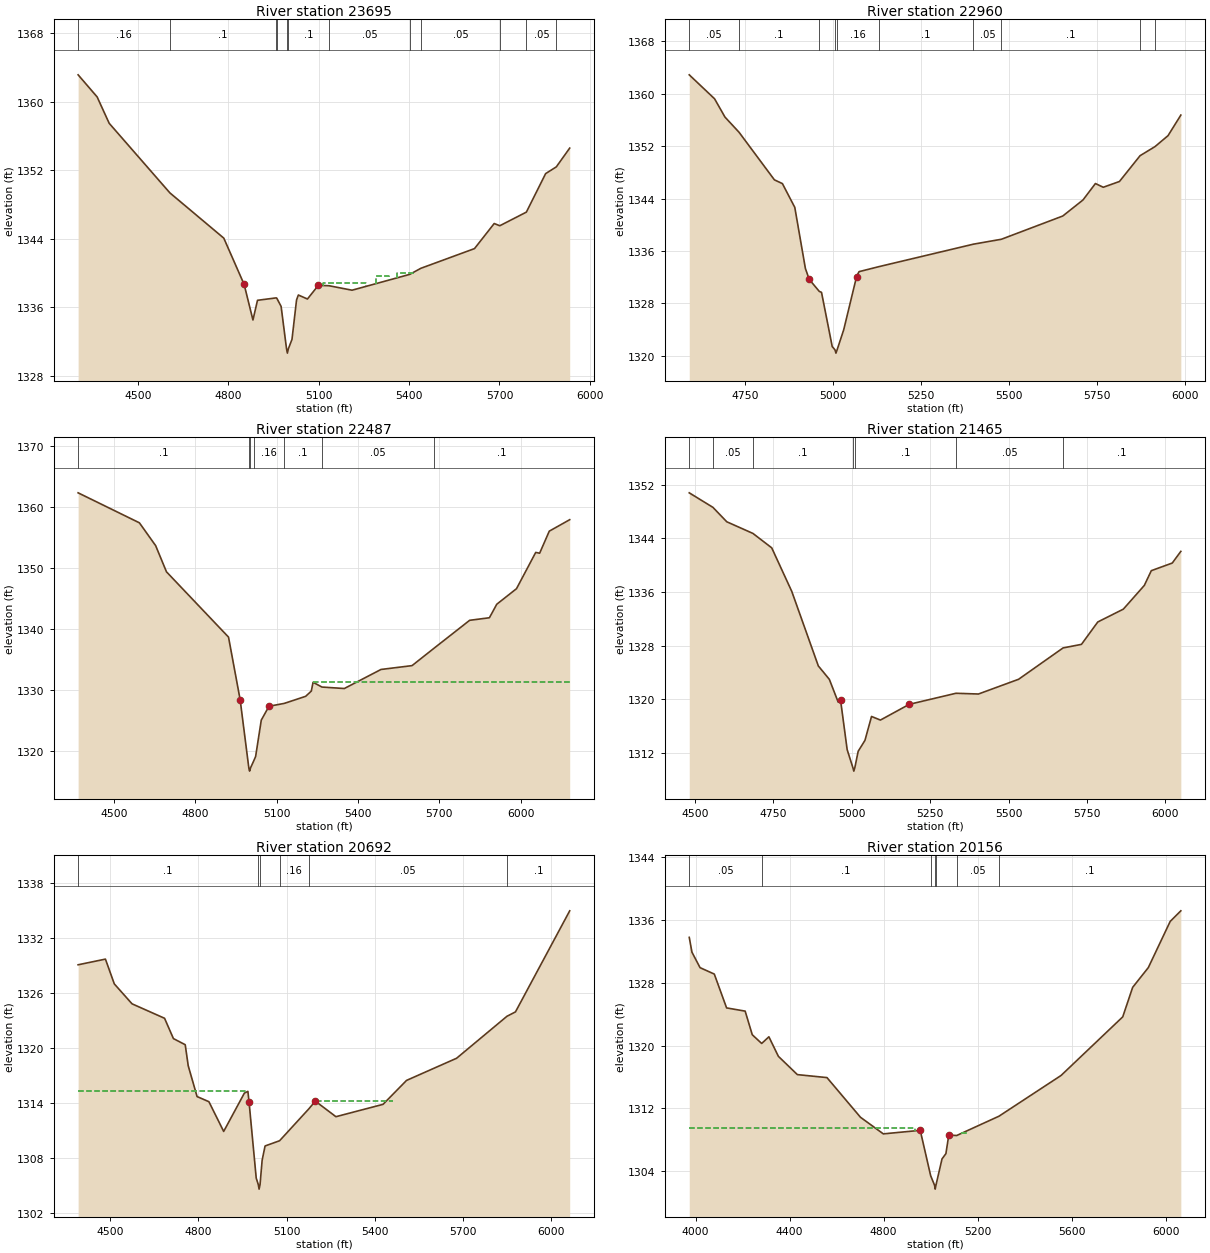
Type RM Length L Ch R = 1 ,23695   ,735,735,735
BEGIN DESCRIPTION:
FLAT CREEK 2 49.0
END DESCRIPTION:
XS GIS Cut Line= 4
      2889795.47      10059602.2      2890300.71     10059628.24
      2890634.05     10059846.99      2891357.97     10059779.29
#Sta/Elev= 30
  4301.4 1363.13  4364.5 1360.55  4404.5 1357.47    4606 1349.34    4785 1344.05
  4852.5 1338.64  4881.7 1334.49  4896.8 1336.79  4957.9 1337.07  4960.5 1337.06
  4975.2 1336.08  4993.2 1331.12    4996 1330.62  4999.2 1331.12  5011.3 1332.23
  5026.4 1336.83  5032.4 1337.41  5062.6 1336.94  5098.8 1338.54  5134.7 1338.49
  5210.7 1337.97  5402.1 1339.82  5439.1 1340.53  5617.1 1342.83  5682.5 1345.76
    5701  1345.5  5789.2 1347.09  5853.2 1351.59  5888.7 1352.38  5933.1 1354.57
#Mann= 12 ,-1 , 0
  4301.4     .16       0    4606      .1       0  4957.9     .16       0
  4960.5      .1       0  4993.2     .07       0  4999.2      .1       0
  5134.7     .05       0  5402.1      .1       0  5439.1     .05       0
    5701      .1       0  5789.2     .05       0  5888.7      .1       0
#XS Ineff= 4 ,-1
 5114.32 5256.48 1338.76 5290.23  5334.2 1339.59 5361.46 5420.88 1339.96
 5521.87 5551.08 1341.53
Permanent Ineff=
       T       T       T       T
Bank Sta=4852.5,5098.8
XS Rating Curve= 0 ,0
Exp/Cntr=0.3,0.1

Type RM Length L Ch R = 1 ,22960   ,473,473,473
BEGIN DESCRIPTION:
FLAT CREEK 2 47.0
END DESCRIPTION:
XS GIS Cut Line= 3
      2890165.28     10060456.38      2890733.01     10060211.58
      2891410.13     10059826.14
#Sta/Elev= 30
  4590.7 1362.89  4662.7 1359.23  4692.2 1356.44  4732.4 1354.11  4832.8 1346.85
  4855.5 1346.28  4890.7 1342.65  4920.9 1333.31  4931.8 1331.65  4960.3 1329.82
  4966.7 1329.67  4997.1  1321.4    5005 1320.89  5007.7 1320.39    5011 1320.89
  5029.8 1323.96  5066.2 1332.04  5073.3 1332.83  5130.1  1333.6  5398.6 1337.03
  5478.1 1337.78  5652.5 1341.33    5710 1343.78  5745.3 1346.29  5767.6 1345.72
  5813.6  1346.6  5872.2 1350.54  5914.7 1351.93  5951.7  1353.6  5988.1 1356.74
#Mann= 10 ,-1 , 0
  4590.7     .05       0  4732.4      .1       0  4960.3     .16       0
    5005     .07       0    5011     .16       0  5130.1      .1       0
  5398.6     .05       0  5478.1      .1       0  5872.2     .05       0
  5914.7      .1       0
Bank Sta=4931.8,5066.2
XS Rating Curve= 0 ,0
Exp/Cntr=0.3,0.1

Type RM Length L Ch R = 1 ,22487   ,1022,1022,1022
BEGIN DESCRIPTION:
FLAT CREEK 2 46.0
END DESCRIPTION:
XS GIS Cut Line= 4
      2890092.34     10060800.12      2890618.42     10060794.91
      2890925.71     10060534.49      2891633.79     10060003.44
#Sta/Elev= 30
  4367.4 1362.26  4593.5 1357.35  4653.5 1353.61  4693.5 1349.32  4922.4 1338.63
  4965.3 1328.38  4997.4 1317.18  5000.2 1316.68  5003.4 1317.18  5016.2 1318.44
  5022.4 1319.07  5043.3 1325.04  5071.9 1327.31    5128 1327.77    5207 1328.93
  5227.9 1329.79  5234.4 1331.23  5267.1 1330.45  5349.7 1330.21  5485.1 1333.33
  5599.7 1333.96    5680 1336.78  5812.2 1341.38  5885.1  1341.8  5912.2 1344.01
  5985.1 1346.56    6056  1352.5  6070.5 1352.37    6106 1355.98  6181.4 1357.86
#Mann= 7 ,-1 , 0
  4367.4      .1       0  4997.4     .07       0  5003.4      .1       0
  5016.2     .16       0    5128      .1       0  5267.1     .05       0
    5680      .1       0
#XS Ineff= 2 , 0
                          5235.8         1331.25
Permanent Ineff=
       T       T
Bank Sta=4965.3,5071.9
XS Rating Curve= 0 ,0
Exp/Cntr=0.3,0.1

Type RM Length L Ch R = 1 ,21465   ,773,773,773
BEGIN DESCRIPTION:
FLAT CREEK 2 44.0
END DESCRIPTION:
XS GIS Cut Line= 4
      2890842.43     10061466.78      2891222.59     10061440.74
       2891477.8     10061206.37      2891857.41     10060457.55
#Sta/Elev= 30
  4482.2 1350.81  4557.7 1348.64  4601.8 1346.49  4685.2 1344.75  4745.1  1342.6
    4809  1336.1  4893.7 1324.97  4928.8 1322.97  4957.2 1319.55  4964.6 1319.86
  4985.6 1312.48    5004 1309.77  5006.8 1309.27    5010 1309.77  5020.7 1312.23
  5042.3 1313.86  5063.3 1317.43  5091.6 1316.89  5183.5 1319.24  5332.4 1320.89
  5404.1 1320.78  5532.1 1322.98  5673.9 1327.66  5732.5 1328.19  5784.5 1331.53
  5866.1 1333.45  5932.9 1336.99  5955.2 1339.19    6022 1340.33  6049.3 1342.07
#Mann= 7 ,-1 , 0
  4482.2      .1       0  4557.7     .05       0  4685.2      .1       0
    5004     .07       0    5010      .1       0  5332.4     .05       0
  5673.9      .1       0
Bank Sta=4964.6,5183.5
XS Rating Curve= 0 ,0
Exp/Cntr=0.3,0.1

Type RM Length L Ch R = 1 ,20692   ,536,536,536
BEGIN DESCRIPTION:
FLAT CREEK 2 42.0
END DESCRIPTION:
XS GIS Cut Line= 3
      2892019.46     10062326.11      2891941.34     10061529.29
      2891920.51     10060659.48
#Sta/Elev= 30
  4391.7 1329.09  4484.5 1329.71  4514.7    1327    4575 1324.82  4685.5 1323.24
  4715.6 1321.02  4755.7 1320.35  4765.9 1318.05    4796 1314.68  4836.2 1314.12
  4886.4 1310.87  4956.8 1315.06  4968.7 1315.25 4972.73 1314.06    4997 1305.77
    5004 1305.06  5006.8 1304.56    5010 1305.06  5017.1 1307.72  5027.1 1309.28
  5076.4 1309.85  5175.6 1313.33  5197.9 1314.18  5267.9 1312.48    5428 1313.83
    5508 1316.45    5678 1318.87  5849.2 1323.46  5878.1 1323.94  6062.4 1334.99
#Mann= 6 ,-1 , 0
  4391.7      .1       0    5004     .07       0    5010      .1       0
  5076.4     .16       0  5175.6     .05       0  5849.2      .1       0
#XS Ineff= 2 ,-1
  4391.7 4968.63 1315.26 5208.15 5463.53 1314.24
Permanent Ineff=
       T       T
Bank Sta=4972.73,5197.9
XS Rating Curve= 0 ,0
Exp/Cntr=0.3,0.1

Type RM Length L Ch R = 1 ,20156   ,867,867,867
BEGIN DESCRIPTION:
FLAT CREEK 2 40.0
END DESCRIPTION:
XS GIS Cut Line= 4
      2892451.75     10062529.32      2892555.92      10061789.7
       2892227.8     10061044.91      2892154.87     10060518.82
#Sta/Elev= 30
  3972.7 1333.78  3984.2 1331.89  4018.7 1329.92  4079.3  1329.1  4131.6 1324.79
  4210.6 1324.38  4240.9 1321.37  4280.9 1320.26  4311.6 1321.11    4352 1318.62
  4432.8 1316.29  4558.8 1315.91  4701.2 1310.86  4798.6 1308.74  4955.6 1309.19
    5000 1303.41  5016.5  1302.2  5019.3  1301.7  5022.5  1302.2  5048.3 1305.55
  5064.9 1306.22  5077.1 1308.59  5110.7 1308.53  5290.6 1310.99  5554.9 1316.18
  5817.4 1323.65  5859.6 1327.41  5926.3 1329.93  6019.3 1335.81  6064.6 1337.16
#Mann= 7 ,-1 , 0
  3972.7     .05       0  4280.9      .1       0    5000     .16       0
  5016.5     .07       0  5022.5     .16       0  5110.7     .05       0
  5290.6      .1       0
#XS Ineff= 3 ,-1
  3972.7 4931.82 1309.51 5077.61 5118.36 1308.57  5130.5 5161.79  1308.9
Permanent Ineff=
       T       T       T
Bank Sta=4955.6,5077.1
XS Rating Curve= 0 ,0
Exp/Cntr=0.3,0.1

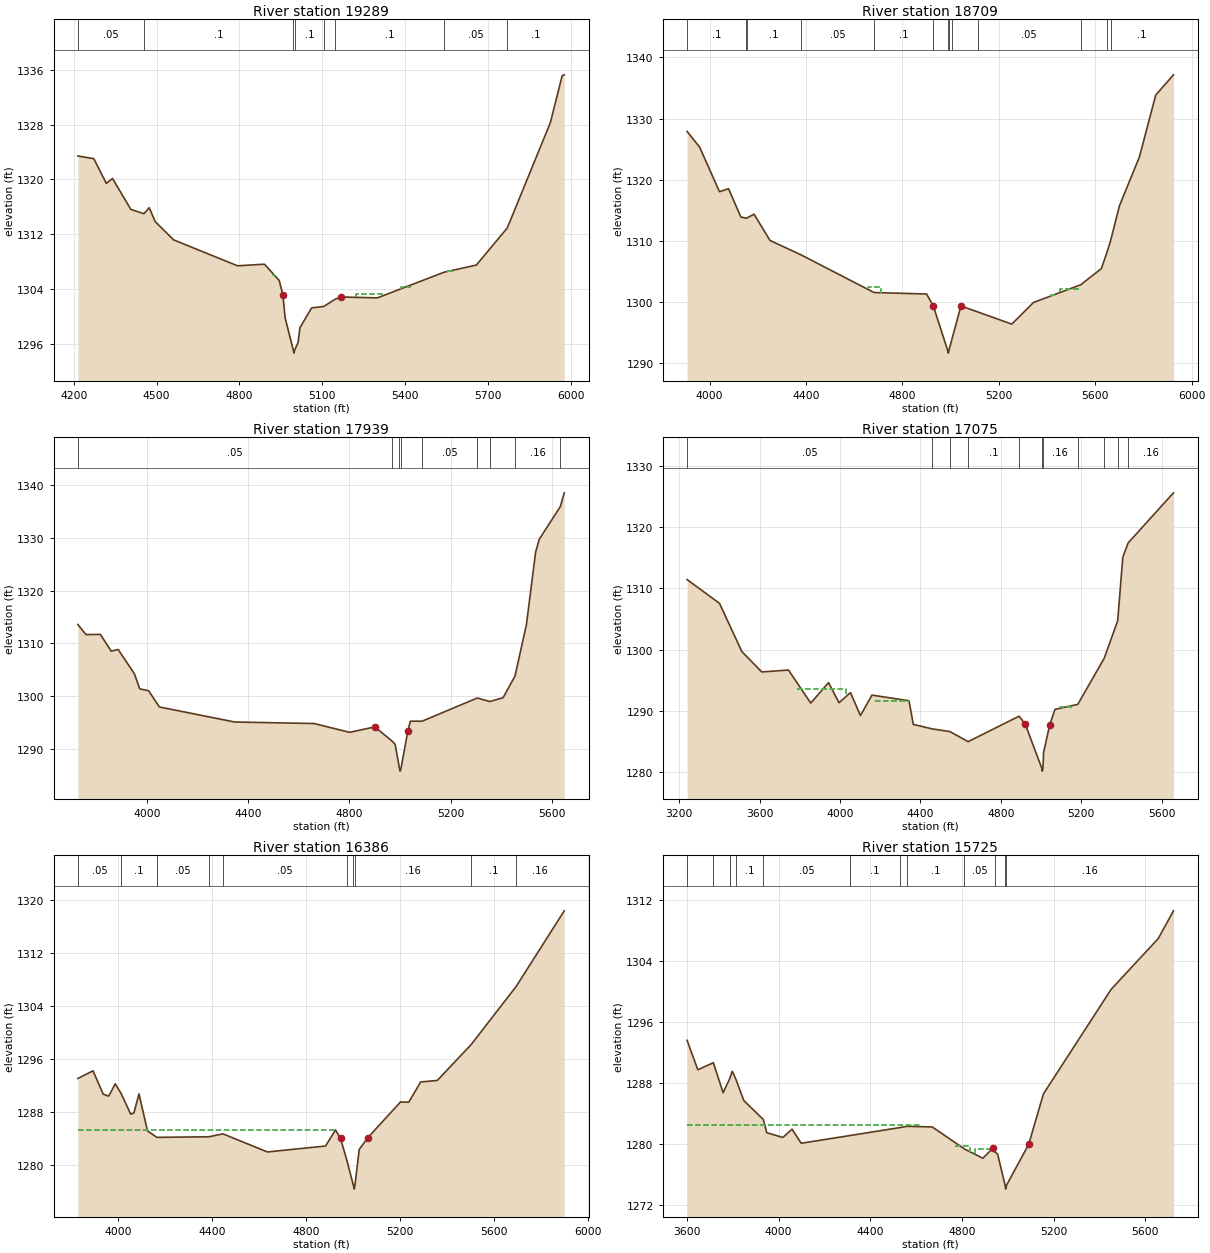
Type RM Length L Ch R = 1 ,19289   ,580,580,580
BEGIN DESCRIPTION:
FLAT CREEK 2 39.0
END DESCRIPTION:
XS GIS Cut Line= 4
      2892706.98     10062477.17      2892956.96     10061951.16
      2893128.84     10061503.24      2893285.09     10060820.96
#Sta/Elev= 30
    4215 1323.42  4272.7 1323.03  4318.1 1319.43  4340.6 1320.14    4407 1315.64
  4454.3 1315.02  4473.5 1315.89  4495.6 1313.85    4562 1311.21  4793.3 1307.44
    4891 1307.67  4944.6  1305.3  4957.9 1303.17    4966 1299.85  4995.1 1295.23
  4997.9 1294.73  5001.1 1295.23  5012.6 1296.24  5019.6 1298.43  5061.9 1301.31
  5105.7 1301.52  5146.8 1302.57  5169.5  1302.9  5300.1 1302.77  5541.3  1306.5
  5658.8 1307.55  5770.8 1312.95  5926.6 1328.25  5969.5  1335.1  5977.1 1335.23
#Mann= 8 ,-1 , 0
    4215     .05       0  4454.3      .1       0  4995.1     .07       0
  5001.1      .1       0  5105.7     .05       0  5146.8      .1       0
  5541.3     .05       0  5770.8      .1       0
#XS Ineff= 4 ,-1
 4918.18 4927.93  1306.1 5222.72 5315.64 1303.27 5386.24 5421.28  1304.3
 5553.91 5580.64 1306.72
Permanent Ineff=
       T       T       T       T
Bank Sta=4957.9,5169.5
XS Rating Curve= 0 ,0
Exp/Cntr=0.3,0.1

Type RM Length L Ch R = 1 ,18709   ,770,770,770
BEGIN DESCRIPTION:
FLAT CREEK 2 38.0
END DESCRIPTION:
XS GIS Cut Line= 3
      2893061.11     10062805.37      2893623.63      10061602.2
      2893925.73     10060982.37
#Sta/Elev= 30
  3906.9 1327.89    3959 1325.32  4041.2 1318.05  4078.8 1318.53    4130 1313.91
  4152.8  1313.7  4155.8 1313.77  4184.7 1314.37  4250.9 1310.08  4378.4 1307.75
  4682.5 1301.57  4900.4 1301.33  4927.4 1299.43  4928.8 1299.31  4987.5 1292.17
  4990.3 1291.67  4993.5 1292.17  5005.5 1293.96    5043 1299.37    5112 1298.41
  5253.8 1296.41  5343.9 1299.95  5539.8 1302.84  5625.5 1305.48  5649.3 1308.21
  5663.4 1309.98  5700.6 1315.76  5783.3 1323.72  5850.9 1333.83  5924.6 1337.14
#Mann= 13 ,-1 , 0
  3906.9      .1       0  4152.8     .05       0  4155.8      .1       0
  4378.4     .05       0  4682.5      .1       0  4927.4     .16       0
  4987.5     .07       0  4993.5     .16       0  5005.5      .1       0
    5112     .05       0  5539.8      .1       0  5649.3     .05       0
  5663.4      .1       0
#XS Ineff= 4 ,-1
 4655.81 4712.13 1302.53 4744.92  4900.2 1301.24 5417.04 5434.06 1301.09
 5455.56 5538.88 1302.17
Permanent Ineff=
       T       T       T       T
Bank Sta=4928.8,5043
XS Rating Curve= 0 ,0
Exp/Cntr=0.3,0.1

Type RM Length L Ch R = 1 ,17939   ,864,864,864
BEGIN DESCRIPTION:
FLAT CREEK 2 36.0
END DESCRIPTION:
XS GIS Cut Line= 4
      2893680.93     10062961.57      2894243.42     10062336.58
      2894269.46     10061649.08      2894523.32     10061348.59
#Sta/Elev= 30
  3727.3 1313.59  3759.5 1311.67  3816.3 1311.72  3858.9 1308.54  3886.6 1308.85
  3950.8 1304.24  3971.8 1301.39  4006.9 1301.03  4049.5 1297.96    4347 1295.11
  4661.1 1294.82  4801.2 1293.15  4901.2 1294.18  4970.1 1291.45  4981.3 1290.87
  4998.3  1286.3    5001  1285.8  5004.3  1286.3  5031.3 1293.36  5041.3 1295.26
  5087.6 1295.26    5306 1299.66  5355.4 1298.99  5407.7 1299.71  5454.9 1303.82
    5500 1313.56  5536.4 1327.31  5550.7 1329.74  5633.9 1335.92  5649.5 1338.54
#Mann= 9 ,-1 , 0
  3727.3     .05       0  4970.1      .1       0  4998.3     .07       0
  5004.3      .1       0  5087.6     .05       0    5306      .1       0
  5355.4     .05       0  5454.9     .16       0  5633.9      .1       0
#XS Ineff= 1 ,-1
 5041.42 5096.53 1295.19
Permanent Ineff=
       T
Bank Sta=4901.2,5031.3
XS Rating Curve= 0 ,0
Exp/Cntr=0.3,0.1

Type RM Length L Ch R = 1 ,17075   ,689,689,689
BEGIN DESCRIPTION:
FLAT CREEK 2 34.0
END DESCRIPTION:
XS GIS Cut Line= 5
      2893876.17     10063330.74       2894540.3     10062987.62
      2895035.09     10062393.87      2895113.21     10061899.08
      2895066.34     10061503.28
#Sta/Elev= 30
    3239 1311.42  3400.3 1307.54  3511.7 1299.66  3610.6 1296.35  3743.5 1296.66
  3854.2 1291.27  3942.8 1294.61  3994.8 1291.33  4052.1 1292.98  4101.5 1289.23
  4158.8 1292.57    4343 1291.65  4364.5 1287.79  4459.1 1287.06  4546.9 1286.62
  4637.2 1284.98  4891.2 1289.14  4921.5 1287.82  5003.5 1280.67  5006.3 1280.17
  5009.5 1280.67  5012.7 1283.23    5043 1287.69    5069 1290.24  5182.8 1291.06
  5314.1 1298.57  5381.4 1304.71  5406.7 1315.06  5433.2 1317.39  5658.9 1325.57
#Mann= 11 ,-1 , 0
    3239     .05       0  4459.1      .1       0  4546.9     .05       0
  4637.2      .1       0  4891.2     .16       0  5003.5     .07       0
  5009.5     .16       0  5182.8      .1       0  5314.1     .16       0
  5381.4      .1       0  5433.2     .16       0
#XS Ineff= 6 ,-1
  3785.8 4029.55 1293.64  4041.6 4158.77 1292.56 4171.75 4342.99 1291.68
 4351.28 4891.59 1289.08 5093.46 5152.37 1290.63 5164.55 5177.02 1290.76
Permanent Ineff=
       T       T       T       T       T       T
Bank Sta=4921.5,5043
XS Rating Curve= 0 ,0
Exp/Cntr=0.3,0.1

Type RM Length L Ch R = 1 ,16386   ,661,661,661
BEGIN DESCRIPTION:
FLAT CREEK 2 33.0
END DESCRIPTION:
XS GIS Cut Line= 3
      2894566.33     10063201.16      2895774.67     10062461.58
      2896237.89     10061998.36
#Sta/Elev= 30
  3827.2 1293.03  3891.8 1294.19  3935.2 1290.65  3958.7 1290.36  3986.5 1292.22
  4010.6 1290.81  4052.5 1287.62  4065.9 1287.81  4087.6 1290.69  4123.9 1285.09
  4163.5 1284.11  4385.4  1284.2  4445.3 1284.64  4634.6  1281.9  4882.2  1282.8
  4924.8 1285.23  4946.1 1283.95  4973.2 1280.62  5001.2 1276.77  5003.9 1276.27
  5007.2 1276.77  5025.6 1282.27  5062.2 1284.06  5201.5 1289.47  5236.6 1289.43
  5287.5  1292.5  5358.2 1292.73  5502.4 1298.16  5694.5 1306.98    5899 1318.42
#Mann= 10 ,-1 , 0
  3827.2     .05       0  4010.6      .1       0  4163.5     .05       0
  4385.4      .1       0  4445.3     .05       0  4973.2     .16       0
  5001.2     .07       0  5007.2     .16       0  5502.4      .1       0
  5694.5     .16       0
#XS Ineff= 2 , 0
         4925.01 1285.23
Permanent Ineff=
       T       T
Bank Sta=4946.1,5062.2
XS Rating Curve= 0 ,0
Exp/Cntr=0.3,0.1

Type RM Length L Ch R = 1 ,15725   ,602,602,602
BEGIN DESCRIPTION:
FLAT CREEK 2 32.0
END DESCRIPTION:
XS GIS Cut Line= 4
      2894701.76     10063258.45      2895925.71     10063169.91
      2896154.88     10062867.83      2896358.01     10062393.85
#Sta/Elev= 30
  3600.8 1293.58  3647.6 1289.71  3715.4 1290.64  3757.9  1286.7  3785.9 1288.48
    3798 1289.52  3814.7  1288.4  3848.2 1285.67  3933.6 1283.18  3948.4 1281.45
  4018.6 1280.83  4058.7 1281.92  4098.8 1280.07  4310.8 1281.08  4527.5 1282.12
    4562 1282.29  4670.3 1282.21  4810.5 1279.33  4891.3  1278.1    4935 1279.44
  4943.5 1278.92  4955.8 1278.64  4988.2 1274.55  4990.9 1274.05  4994.2 1274.55
    5091 1279.91  5155.5 1286.55  5450.9 1300.27  5656.3 1306.93  5722.8 1310.57
#Mann= 12 ,-1 , 0
  3600.8     .05       0  3715.4      .1       0  3785.9     .05       0
  3814.7      .1       0  3933.6     .05       0  4310.8      .1       0
  4527.5     .05       0    4562      .1       0  4810.5     .05       0
  4943.5     .16       0  4988.2     .07       0  4994.2     .16       0
#XS Ineff= 3 ,-1
  3600.8 4612.22  1282.5 4769.78 4834.87 1279.68 4855.66 4933.57 1279.29
Permanent Ineff=
       T       T       T
Bank Sta=4935,5091
XS Rating Curve= 0 ,0
Exp/Cntr=0.3,0.1