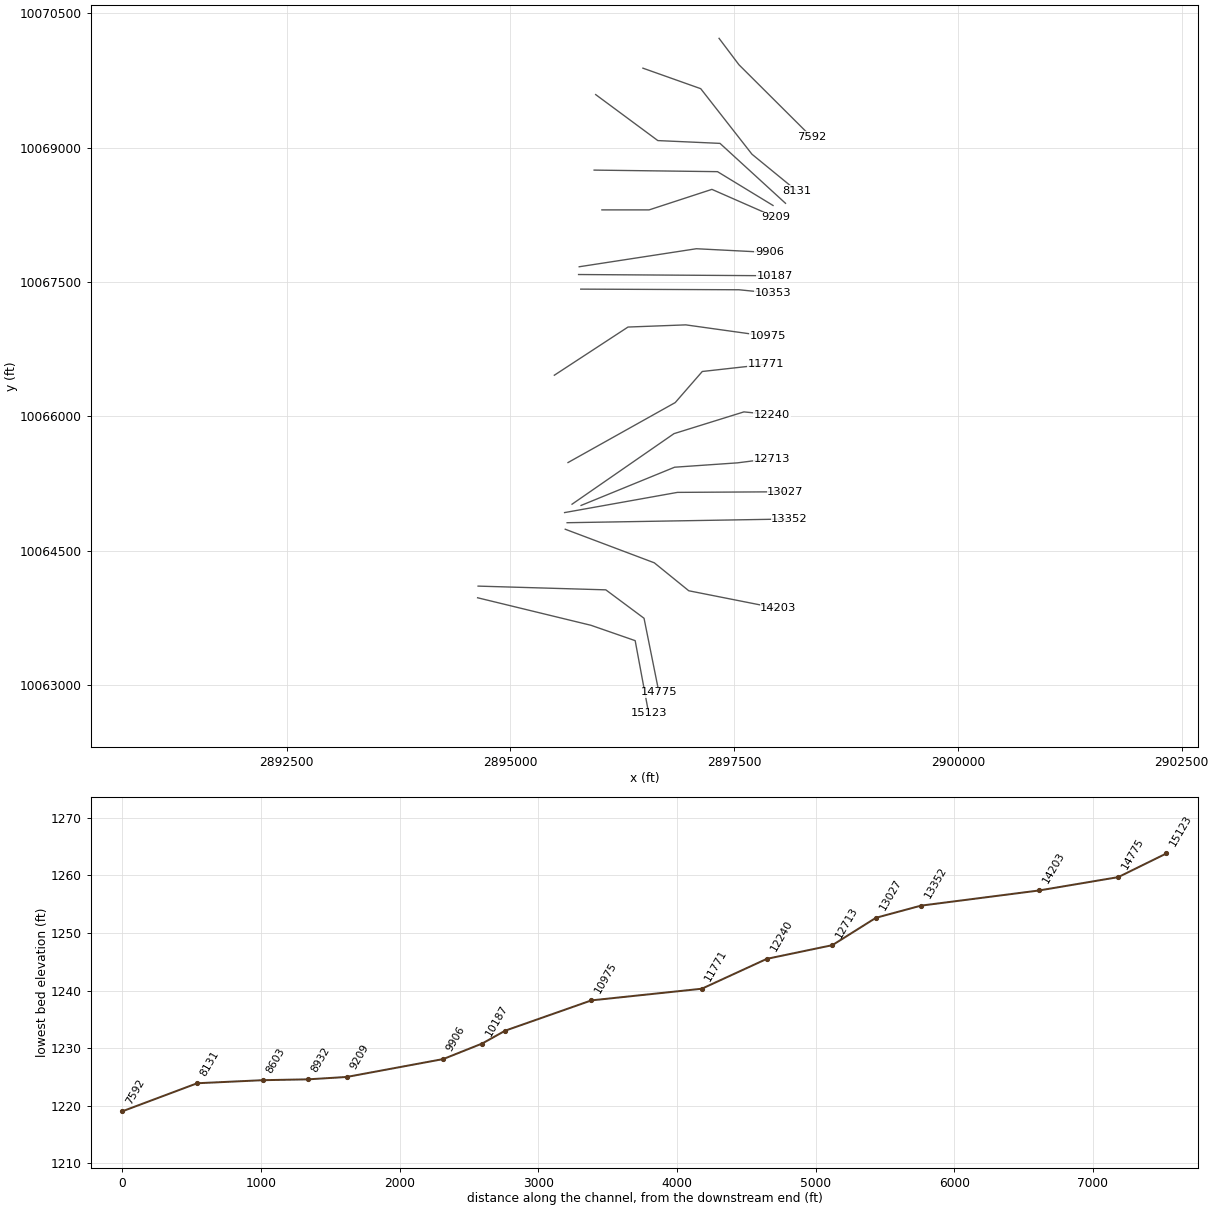
HEC-RAS study FLAT CREEK 2.prj: FLAT CREEK 2 Base Level Engineering

--- FLAT CREEK 2.g01 (geometry) --- (continued)

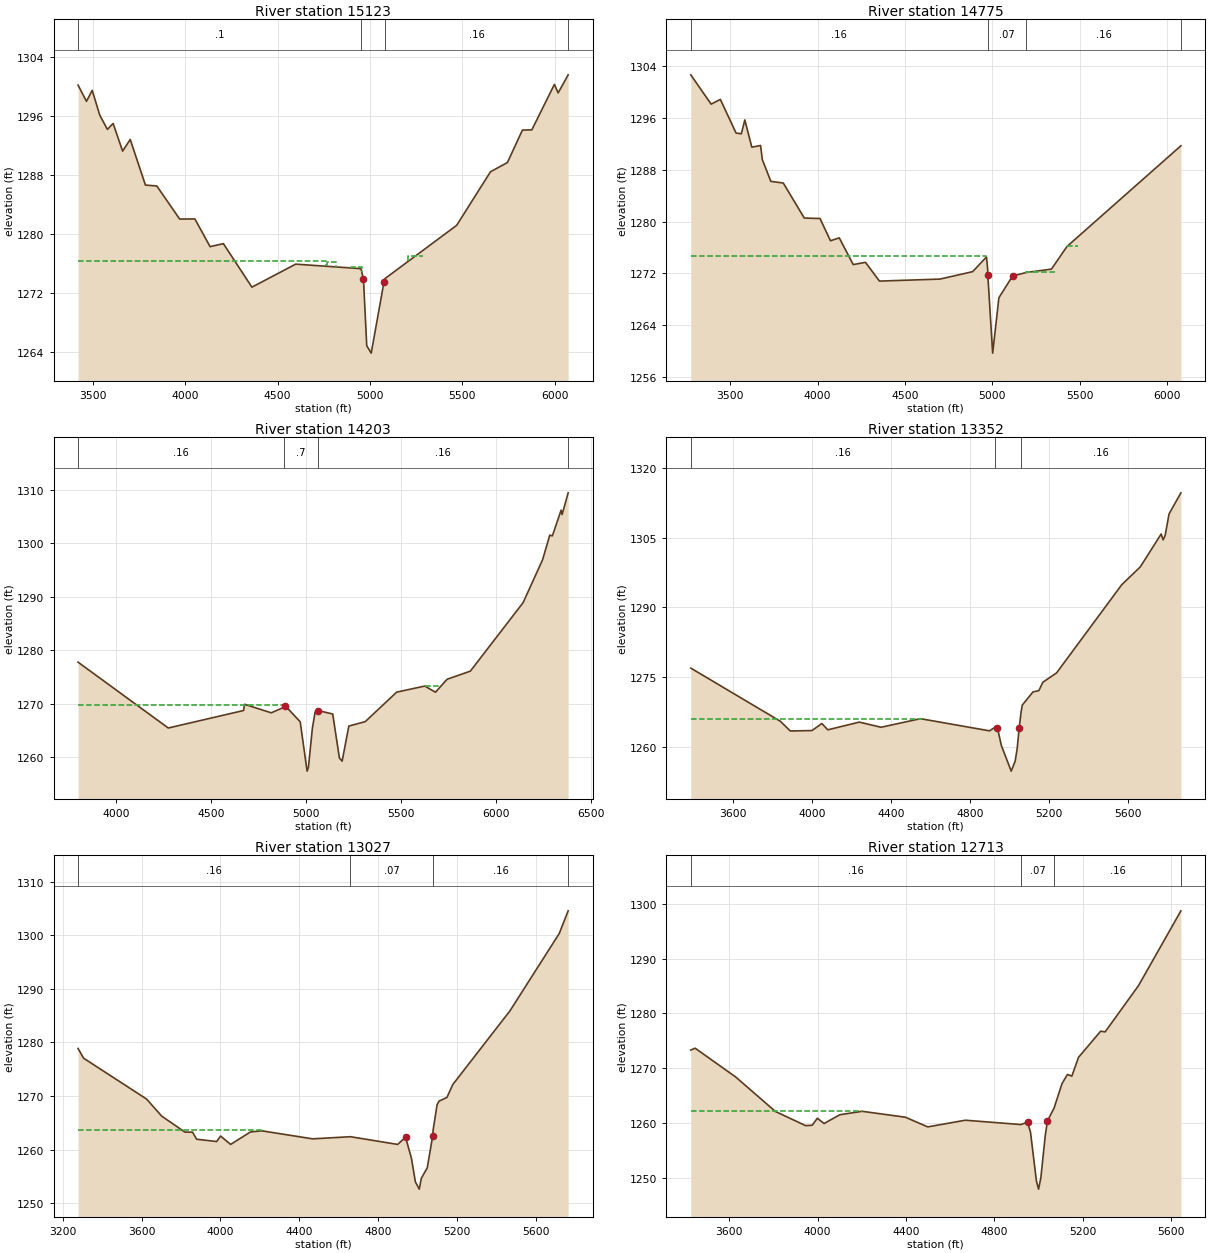
Type RM Length L Ch R = 1 ,15123   ,348,348,348
BEGIN DESCRIPTION:
FLAT CREEK 2 31.0
END DESCRIPTION:
XS GIS Cut Line= 4
      2894634.03       10063972.      2895899.67      10063664.7
      2896394.46     10063492.83       2896545.5     10062680.35
#Sta/Elev= 30
  3419.9 1300.14  3465.6 1297.94  3496.5 1299.43  3537.7 1296.05  3578.8 1294.13
  3609.7 1294.94  3661.1 1291.19  3702.3 1292.77  3784.6 1286.59  3846.4 1286.46
  3969.9 1281.98  4052.2    1282  4134.5 1278.24  4206.5 1278.65  4360.9 1272.75
  4597.6 1275.87  4951.2 1275.26  4964.5 1273.88  4982.4  1264.8  5006.6 1263.81
  5075.7 1273.47    5081 1273.91    5469 1281.13    5652 1288.39  5743.6 1289.64
  5824.9 1294.04  5875.8 1294.07  5997.9 1300.23  6018.2 1299.08  6072.5 1301.53
#Mann= 4 ,-1 , 0
  3419.9      .1       0  4951.2     .07       0    5081     .16       0
  6072.5     .05       0
#XS Ineff= 4 ,-1
  3419.9  4763.3 1276.29  4766.2  4816.2 1276.16 4895.49 4956.12 1275.45
  5207.7 5286.41 1276.99
Permanent Ineff=
       T       T       T       T
Bank Sta=4964.5,5075.7
XS Rating Curve= 0 ,0
Exp/Cntr=0.3,0.1

Type RM Length L Ch R = 1 ,14775   ,572,572,572
BEGIN DESCRIPTION:
FLAT CREEK 2 30.0
END DESCRIPTION:
XS GIS Cut Line= 4
      2894639.26      10064102.2      2896066.34     10064060.54
      2896493.42     10063742.83      2896660.09     10062914.71
#Sta/Elev= 30
  3274.8 1302.69  3391.4 1298.16  3444.1 1298.89  3534.1 1293.69  3564.1 1293.58
  3584.1 1295.72  3624.1 1291.51  3674.2 1291.77  3684.2  1289.6  3732.8 1286.23
  3804.2 1285.97  3924.3 1280.56  4014.3 1280.49  4074.2 1277.05  4124.4  1277.5
  4204.4 1273.37  4274.4 1273.72  4354.5 1270.82    4701 1271.13  4887.8 1272.28
  4966.9 1274.55  4973.3 1272.82 4974.72  1271.7  5002.3 1259.69    5038 1268.25
  5116.4 1271.61  5194.4 1272.15  5338.7 1272.67  5427.7 1276.17  6079.5 1291.73
#Mann= 4 ,-1 , 0
  3274.8     .16       0  4973.3     .07       0  5194.4     .16       0
  6079.5      .1       0
#XS Ineff= 3 ,-1
  3274.8 4966.76 1274.71 5193.47 5370.45 1272.23 5428.12 5487.78 1276.21
Permanent Ineff=
       T       T       T
Bank Sta=4974.72,5116.4
XS Rating Curve= 0 ,0
Exp/Cntr=0.3,0.1

Type RM Length L Ch R = 1 ,14203   ,851,851,851
BEGIN DESCRIPTION:
FLAT CREEK 2 29.0
END DESCRIPTION:
XS GIS Cut Line= 4
      2895613.18     10064737.63      2896608.01     10064362.62
      2896993.42     10064050.12      2897993.38     10063852.21
#Sta/Elev= 30
  3798.8 1277.74  4273.5 1265.43  4669.6  1268.7    4675 1269.86  4815.3 1268.27
  4882.9 1269.31  4889.4 1269.56  4967.7 1266.59  5003.9 1257.37  5010.8 1258.05
  5031.6 1265.37    5046  1268.4  5060.4  1268.7  5138.7 1268.05  5173.9 1259.82
  5188.3 1259.24  5223.5 1265.79  5309.7 1266.62  5475.4 1272.14    5623 1273.27
  5679.4 1272.12  5740.5 1274.54  5862.8 1276.06  6140.5 1288.87    6243 1296.89
  6280.7 1301.48  6294.2 1301.34  6340.4 1306.15  6345.5 1305.33  6377.5 1309.39
#Mann= 4 ,-1 , 0
  3798.8     .16       0  4882.9      .7       0  5060.4     .16       0
  6377.5     .16       0
#XS Ineff= 3 ,-1
  3798.8 4875.57 1269.75 5068.18 5426.14 1268.55 5622.95 5693.78 1273.22
Permanent Ineff=
       T       T       T
Bank Sta=4889.4,5060.4
XS Rating Curve= 0 ,0
Exp/Cntr=0.3,0.1

Type RM Length L Ch R = 1 ,13352   ,325,325,325
BEGIN DESCRIPTION:
Mapping XS 3b0ceef1
END DESCRIPTION:
XS GIS Cut Line= 2
      2895634.07     10064810.54      2898118.42      10064852.2
#Sta/Elev= 30
  3384.6 1276.94  3839.1 1265.47  3889.1 1263.39  3999.1 1263.48  4049.1    1265
  4079.1 1263.64  4239.1  1265.3  4349.1 1264.19  4549.2 1266.04  4899.2 1263.42
  4929.2 1264.25  4939.2 1264.05  4959.2 1260.25    5009 1254.74  5029.2 1256.91
  5039.2 1259.56  5049.2 1263.95  5059.2 1267.52  5065.1 1268.96  5119.2 1271.79
  5149.2 1272.09  5169.2 1273.88  5239.3 1275.92  5569.3  1294.9  5663.3 1298.74
  5769.3 1305.83  5779.3 1304.57  5789.3 1305.49  5809.3 1310.16  5869.3  1314.7
#Mann= 3 ,-1 , 0
  3384.6     .16       0  4929.2     .07       0  5059.2     .16       0
#XS Ineff= 2 , 0
         4559.14 1266.03
Permanent Ineff=
       T       T
Bank Sta=4939.2,5049.2
XS Rating Curve= 0 ,0
Exp/Cntr=0.3,0.1

Type RM Length L Ch R = 1 ,13027   ,314,314,314
BEGIN DESCRIPTION:
FLAT CREEK 2 28.0
END DESCRIPTION:
XS GIS Cut Line= 3
      2895605.95     10064923.74      2896866.34     10065149.42
      2898074.08     10065156.37
#Sta/Elev= 30
  3277.7 1278.87  3305.9 1277.06  3625.7 1269.43  3702.5 1266.25  3820.2 1263.27
  3859.3 1263.25  3879.6 1261.94  3981.2 1261.51  4001.5 1262.53  4052.3 1260.97
    4153  1263.3  4211.8  1263.5  4468.9 1262.01  4660.3 1262.41  4900.3 1260.97
  4940.3 1262.32  4970.3 1258.37  4990.3 1253.98    5010 1252.63  5020.3 1254.65
  5050.3 1256.58 5077.84 1262.47  5080.3 1263.64  5100.3 1268.36  5110.3 1269.05
  5150.3 1269.73  5180.3 1272.15  5470.3 1285.89  5720.3  1300.3  5765.9 1304.55
#Mann= 4 ,-1 , 0
  3277.7     .16       0  4660.3     .07       0  5080.3     .16       0
  5765.9     .16       0
#XS Ineff= 2 , 0
         4211.93 1263.67
Permanent Ineff=
       T       T
Bank Sta=4940.3,5077.84
XS Rating Curve= 0 ,0
Exp/Cntr=0.3,0.1

Type RM Length L Ch R = 1 ,12713   ,473,473,473
BEGIN DESCRIPTION:
FLAT CREEK 2 27.0
END DESCRIPTION:
XS GIS Cut Line= 4
      2895789.98      10065003.6      2896835.09     10065430.67
      2897536.48     10065479.29      2897918.43      10065527.9
#Sta/Elev= 30
  3426.6 1273.29  3446.6 1273.63  3630.4 1268.35  3809.4 1262.07  3945.7 1259.49
  3975.9 1259.55  3999.1 1260.83  4029.9 1259.87  4100.6 1261.47  4202.1  1262.1
  4397.2 1261.02  4498.7 1259.25  4668.2 1260.47  4919.8 1259.68  4949.9  1260.1
  4963.2 1258.32    4990 1249.39  4999.8 1247.88  5010.1 1249.94  5030.1 1257.67
  5040.1 1260.34  5070.2 1262.72  5105.7 1267.14  5130.4 1268.83  5150.4 1268.53
  5180.5 1271.96  5280.8 1276.74    5301 1276.61  5452.2 1285.08  5643.7 1298.73
#Mann= 4 ,-1 , 0
  3426.6     .16       0  4919.8     .07       0  5070.2     .16       0
  5643.7      .1       0
#XS Ineff= 2 , 0
         4202.03 1262.12
Permanent Ineff=
       T       T
Bank Sta=4949.9,5040.1
XS Rating Curve= 0 ,0
Exp/Cntr=0.3,0.1

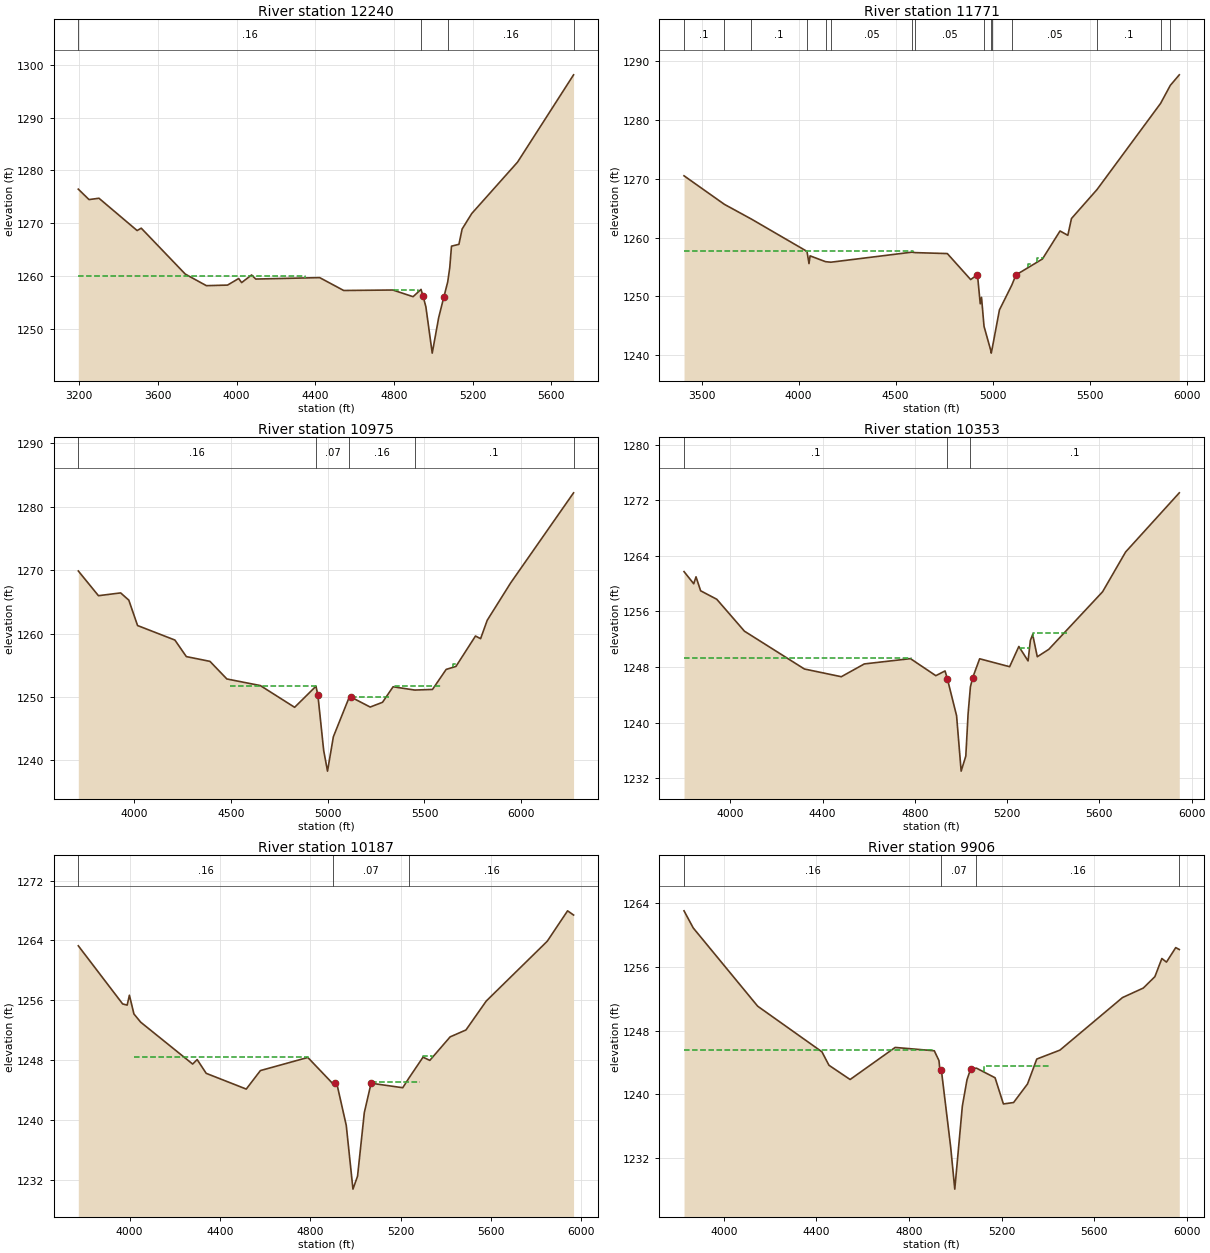
Type RM Length L Ch R = 1 ,12240   ,469,469,469
BEGIN DESCRIPTION:
FLAT CREEK 2 26.0
END DESCRIPTION:
XS GIS Cut Line= 4
      2895689.24     10065017.47      2896828.14     10065805.67
      2897609.39     10066048.73       2897921.9     10066017.48
#Sta/Elev= 30
  3195.3 1276.47  3249.7  1274.5  3300.3 1274.75  3494.3 1268.65  3515.2  1269.1
  3738.9 1260.43  3846.3 1258.24  3953.8 1258.35  4010.5 1259.59  4025.4 1258.82
  4076.1 1260.26    4097 1259.49  4422.1 1259.76  4544.3 1257.33    4794 1257.42
  4896.9 1256.16  4937.3 1257.54  4947.2  1256.3  4961.9 1254.26  4994.2  1245.5
    5027  1252.2  5053.6 1256.15  5072.9 1258.94  5083.4 1261.68  5092.1  1265.7
  5129.9 1266.05  5146.2 1268.94    5195 1271.86  5427.8 1281.57  5712.6 1298.06
#Mann= 4 ,-1 , 0
  3195.3     .16       0  4937.3     .07       0  5072.9     .16       0
  5712.6      .1       0
#XS Ineff= 2 ,-1
  3195.3    4350 1260.05 4796.59 4922.73 1257.42
Permanent Ineff=
       T       T
Bank Sta=4947.2,5053.6
XS Rating Curve= 0 ,0
Exp/Cntr=0.3,0.1

Type RM Length L Ch R = 1 ,11771   ,796,796,796
BEGIN DESCRIPTION:
FLAT CREEK 2 25.0
END DESCRIPTION:
XS GIS Cut Line= 4
      2895644.11     10065482.76      2896842.03      10066152.9
      2897144.12     10066500.12      2897859.41     10066579.98
#Sta/Elev= 30
  3409.5 1270.52  3617.4 1265.66  3757.1 1263.14  4043.3 1257.64  4053.6 1255.56
  4059.3 1256.88  4138.8 1255.89  4166.3  1255.8  4584.3 1257.51  4601.4 1257.43
  4766.6 1257.27  4886.8 1252.84  4921.9 1253.67  4936.2 1248.71  4942.8 1249.81
  4955.7 1244.88  4990.1 1240.81  4992.9 1240.31  4996.1 1240.81  5035.1 1247.67
  5098.6 1251.88  5120.4 1253.63  5256.8 1256.35  5347.4 1261.12  5387.6 1260.38
  5406.4 1263.24  5538.4 1268.19  5865.8 1282.86  5915.9 1285.93  5962.1 1287.72
#Mann= 15 ,-1 , 0
  3409.5      .1       0  3617.4     .16       0  3757.1      .1       0
  4043.3     .05       0  4138.8      .1       0  4166.3     .05       0
  4584.3      .1       0  4601.4     .05       0  4955.7     .16       0
  4990.1     .07       0  4996.1     .16       0  5098.6     .05       0
  5538.4      .1       0  5865.8     .05       0  5915.9      .1       0
#XS Ineff= 4 ,-1
  3409.5 4588.64 1257.77 5183.99 5197.48 1255.45    5227 5263.49 1256.52
  5316.9  5324.3 1259.09
Permanent Ineff=
       T       T       T       T
Bank Sta=4921.9,5120.4
XS Rating Curve= 0 ,0
Exp/Cntr=0.3,0.1

Type RM Length L Ch R = 1 ,10975   ,622,622,622
BEGIN DESCRIPTION:
FLAT CREEK 2 24.0
END DESCRIPTION:
XS GIS Cut Line= 4
      2895491.33     10066458.44      2896314.26     10066996.65
      2896960.09     10067020.95      2897880.27     10066892.47
#Sta/Elev= 30
  3711.5 1269.87  3815.6 1265.97  3930.2 1266.41  3972.4 1265.27  4017.7 1261.26
  4210.6 1258.97  4269.7 1256.36  4391.6 1255.61  4479.1 1252.83    4652 1251.79
  4829.1 1248.36  4939.2 1251.68  4949.2 1250.31  4979.2 1241.55    4999 1238.29
  5029.2 1243.71  5109.3 1249.81  5119.3 1249.99  5219.4  1248.4  5283.2 1249.15
  5337.8  1251.6  5449.9 1251.08  5541.4 1251.18  5612.1 1254.34  5662.6 1254.81
  5763.5 1259.61  5789.9 1259.19  5824.1 1262.09  5945.3 1267.99  6270.2  1282.2
#Mann= 5 ,-1 , 0
  3711.5     .16       0  4939.2     .07       0  5109.3     .16       0
  5449.9      .1       0  6270.2     .16       0
#XS Ineff= 4 ,-1
 4493.75 4936.93 1251.78 5127.84 5315.34 1250.05 5346.02 5591.48 1251.78
 5647.11 5669.66 1255.12
Permanent Ineff=
       T       T       T       T
Bank Sta=4949.2,5119.3
XS Rating Curve= 0 ,0
Exp/Cntr=0.3,0.1

Type RM Length L Ch R = 1 ,10353   ,166,166,166
BEGIN DESCRIPTION:
FLAT CREEK 2 23.0
END DESCRIPTION:
XS GIS Cut Line= 3
      2895786.43     10067420.26      2897553.84     10067413.31
       2897932.3     10067375.12
#Sta/Elev= 30
  3798.7 1261.73  3840.7 1259.98  3850.7 1260.98  3870.7 1258.97  3940.7 1257.75
  4060.7 1253.16  4320.7 1247.72  4480.7 1246.61  4580.7 1248.45  4780.7 1249.21
  4890.7 1246.76  4930.7 1247.44  4940.7 1246.31  4980.7    1241  5000.5 1233.03
  5020.7  1235.2  5030.7 1241.33  5040.7 1245.16  5050.7 1246.49  5080.7 1249.19
  5210.7 1248.05  5250.7 1250.96  5290.7 1248.88  5300.7 1251.83  5310.7 1252.68
  5330.7 1249.48  5380.7 1250.55  5613.9 1258.83  5713.9 1264.56  5946.5 1273.06
#Mann= 3 ,-1 , 0
  3798.7      .1       0  4940.7     .07       0  5040.7      .1       0
#XS Ineff= 4 ,-1
  3798.7 4781.25 1249.34 5082.39  5235.8 1248.84 5261.36 5301.14 1250.78
  5312.5 5458.81  1252.9
Permanent Ineff=
       T       T       T       T
Bank Sta=4940.7,5050.7
XS Rating Curve= 0 ,0
Exp/Cntr=0.3,0.1

Type RM Length L Ch R = 1 ,10187   ,281,281,281
BEGIN DESCRIPTION:
FLAT CREEK 2 22.0
END DESCRIPTION:
XS GIS Cut Line= 2
      2895762.14     10067583.45      2897954.99     10067569.57
#Sta/Elev= 30
  3772.9 1263.29  3969.2 1255.53  3989.2 1255.37  3999.2 1256.69  4019.2 1254.19
  4049.2 1253.09  4279.2  1247.5  4299.2  1248.1  4339.2 1246.26  4516.5 1244.16
  4579.2 1246.63  4789.2 1248.38  4899.3  1244.9  4909.3    1245  4919.3 1244.66
  4959.3 1239.32    4989  1230.8  5009.3 1232.52  5039.3 1241.02  5069.3 1244.94
  5209.3 1244.34  5239.3 1245.74  5299.3 1248.42  5329.3 1247.99  5419.3 1251.13
  5489.3 1252.05  5579.3 1255.92  5849.3  1263.9  5939.3 1267.96  5965.8  1267.4
#Mann= 3 ,-1 , 0
  3772.9     .16       0  4899.3     .07       0  5239.3     .16       0
#XS Ineff= 3 ,-1
 4018.47 4791.19 1248.47 5073.86 5284.09 1245.07 5301.14 5339.49 1248.57
Permanent Ineff=
       T       T       T
Bank Sta=4909.3,5069.3
XS Rating Curve= 0 ,0
Exp/Cntr=0.3,0.1

Type RM Length L Ch R = 1 ,9906    ,697,697,697
BEGIN DESCRIPTION:
FLAT CREEK 2 21.0
END DESCRIPTION:
XS GIS Cut Line= 3
      2895769.16     10067670.27      2897078.14     10067871.65
       2897893.8       10067830.
#Sta/Elev= 30
  3827.4 1263.06  3867.2 1260.91  4145.8 1251.08  4423.6 1245.35    4454 1243.66
  4545.4 1241.87  4740.2  1245.9  4909.3 1245.48  4929.5 1244.25  4934.9 1242.68
    4940 1243.04  4980.1  1233.4  4997.9  1228.1  5030.7 1238.55  5050.9 1241.86
  5066.5 1243.19  5091.4  1243.3  5172.1 1242.09  5208.1  1238.8  5252.2 1238.98
  5312.3 1241.31  5352.4 1244.44  5452.5 1245.56  5722.8 1252.16    5813 1253.36
    5863 1254.79  5893.1 1257.07  5913.1 1256.62  5953.1 1258.44  5968.5  1258.2
#Mann= 4 ,-1 , 0
  3827.4     .16       0    4940     .07       0  5091.4     .16       0
  5968.5      .1       0
#XS Ineff= 2 ,-1
  3827.4 4907.67 1245.63 5122.16 5410.51 1243.57
Permanent Ineff=
       T       T
Bank Sta=4940,5066.5
XS Rating Curve= 0 ,0
Exp/Cntr=0.3,0.1

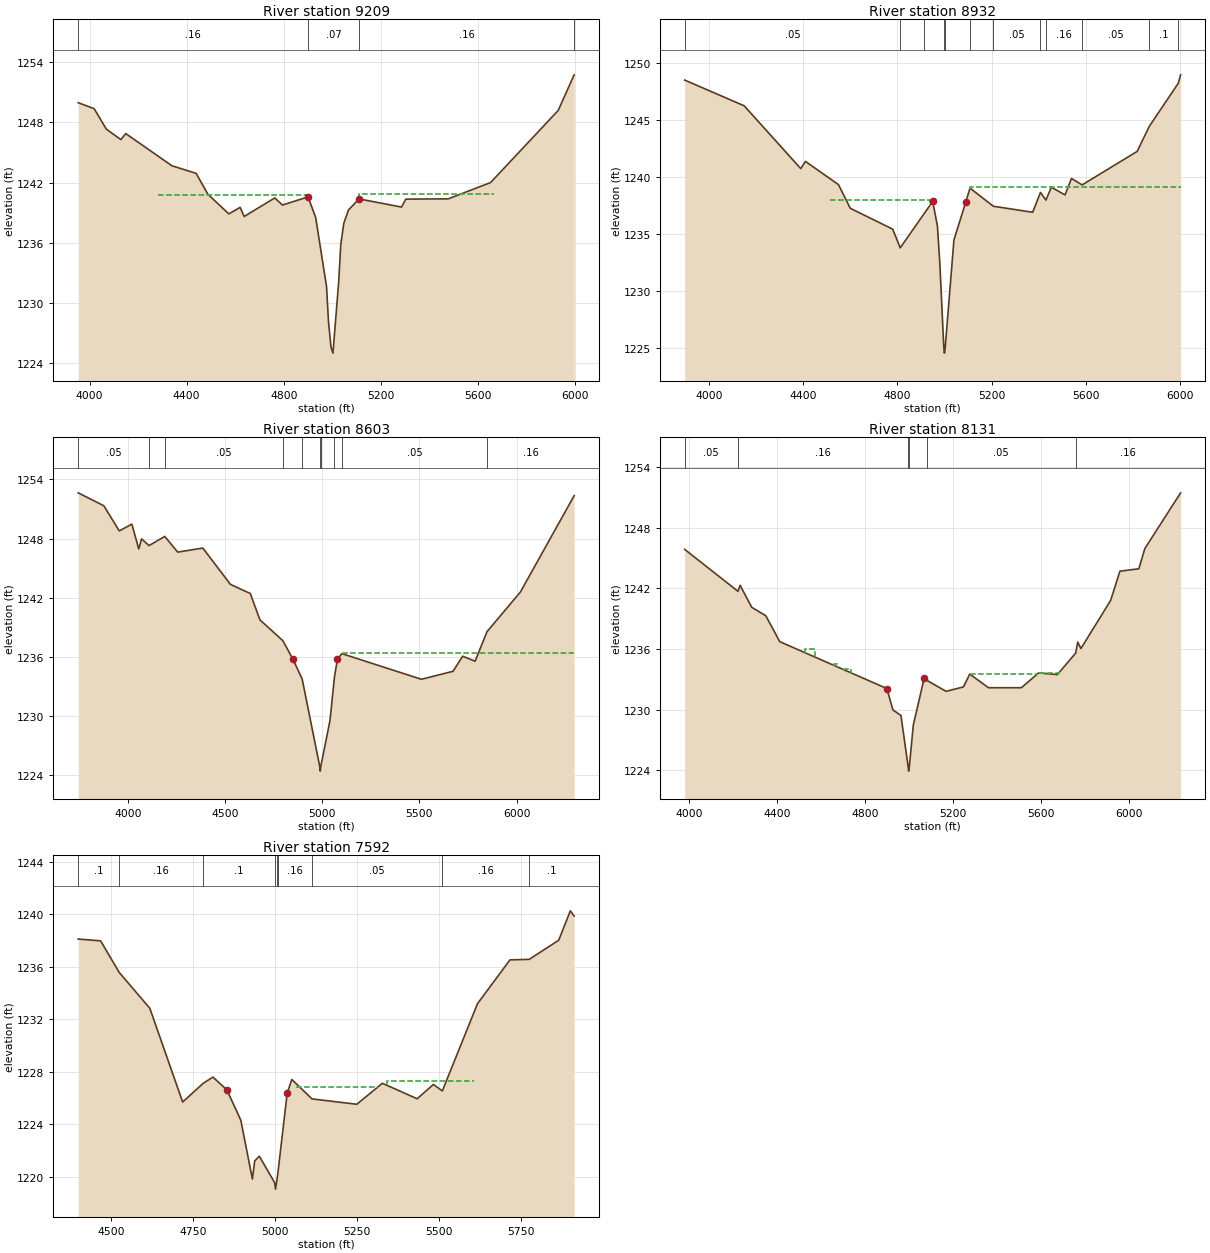
Type RM Length L Ch R = 1 ,9209    ,277,277,277
BEGIN DESCRIPTION:
FLAT CREEK 2 20.0
END DESCRIPTION:
XS GIS Cut Line= 4
      2896022.58     10068305.67      2896550.37     10068305.67
      2897251.76     10068534.84      2897963.52     10068222.36
#Sta/Elev= 30
  3953.2 1249.97  4019.1 1249.37  4069.1 1247.33  4129.1 1246.29  4149.1 1246.89
  4339.1 1243.68  4439.1 1242.92  4487.5 1240.83  4573.7 1238.88  4620.3 1239.53
  4636.8 1238.62    4763 1240.47  4794.6 1239.76  4899.8 1240.57  4931.4 1238.53
  4976.3 1231.61    4984 1228.21  4994.5 1225.59  5002.6 1224.99    5026 1232.01
  5034.8  1235.8  5047.1 1237.92  5066.6 1239.27  5110.2 1240.37    5285 1239.56
  5302.6 1240.35  5477.4 1240.38  5651.8    1242  5930.6  1249.2  5996.2 1252.75
#Mann= 4 ,-1 , 0
  3953.2     .16       0  4899.8     .07       0  5110.2     .16       0
  5996.2     .16       0
#XS Ineff= 2 ,-1
 4282.67 4900.57 1240.76  5110.8 5666.19 1240.85
Permanent Ineff=
       T       T
Bank Sta=4899.8,5110.2
XS Rating Curve= 0 ,0
Exp/Cntr=0.3,0.1

Type RM Length L Ch R = 1 ,8932    ,329,329,329
BEGIN DESCRIPTION:
FLAT CREEK 2 19.0
END DESCRIPTION:
XS GIS Cut Line= 3
      2895935.77     10068750.12      2897314.26     10068732.76
       2897934.6     10068355.01
#Sta/Elev= 30
  3896.8 1248.54  4149.5 1246.28  4389.5 1240.77  4409.5  1241.4  4549.5 1239.37
  4599.6 1237.29  4779.6 1235.46  4811.7 1233.82  4910.5 1236.74  4949.6  1237.9
  4969.6 1235.72  4979.6 1232.52  4996.6 1225.08  4999.3 1224.58  5002.6 1225.08
  5039.6 1234.51  5089.6 1237.82  5107.9 1239.06  5206.7 1237.47  5373.7 1236.94
  5406.9 1238.68  5430.1 1238.01  5453.1 1239.14  5511.2 1238.46  5538.4 1239.91
  5583.7 1239.34  5817.3 1242.28  5868.5 1244.47  5991.8 1248.26  6001.7    1249
#Mann= 12 ,-1 , 0
  3896.8     .05       0  4811.7     .16       0  4910.5     .12       0
  4996.6     .07       0  5002.6     .12       0  5107.9      .1       0
  5206.7     .05       0  5406.9      .1       0  5430.1     .16       0
  5583.7     .05       0  5868.5      .1       0  5991.8     .16       0
#XS Ineff= 2 ,-1
  4512.5 4936.93 1238.06 5107.39  6001.7 1239.19
Permanent Ineff=
       T       T
Bank Sta=4949.6,5089.6
XS Rating Curve= 0 ,0
Exp/Cntr=0.3,0.1

Type RM Length L Ch R = 1 ,8603    ,472,472,472
BEGIN DESCRIPTION:
FLAT CREEK 2 18.0
END DESCRIPTION:
XS GIS Cut Line= 4
      2895953.11      10069593.9      2896647.59     10069079.98
      2897342.03     10069048.73      2898074.01      10068379.2
#Sta/Elev= 30
  3744.8 1252.64  3876.6 1251.33    3956 1248.78  4020.7 1249.47  4056.2 1246.95
  4070.8 1247.97    4109 1247.29    4190 1248.22  4256.6 1246.63  4385.9 1247.04
  4527.9 1243.36  4629.7 1242.44  4679.7 1239.76  4797.7 1237.65  4849.9 1235.75
  4896.7 1233.78    4987 1224.93  4989.8 1224.43    4993 1224.93  5040.1 1229.58
  5063.1    1234  5078.3 1235.78  5100.9 1236.34  5510.2 1233.74    5673 1234.55
  5722.4 1236.08  5786.5 1235.57  5847.5 1238.56  6019.6 1242.59  6295.9 1252.35
#Mann= 10 ,-1 , 0
  3744.8     .05       0    4109      .1       0    4190     .05       0
  4797.7     .16       0  4896.7     .12       0    4987     .07       0
    4993     .12       0  5063.1     .16       0  5100.9     .05       0
  5847.5     .16       0
#XS Ineff= 2 , 0
                         5109.09         1236.43
Permanent Ineff=
       T       T
Bank Sta=4849.9,5078.3
XS Rating Curve= 0 ,0
Exp/Cntr=0.3,0.1

Type RM Length L Ch R = 1 ,8131    ,539,539,539
BEGIN DESCRIPTION:
FLAT CREEK 2 17.0
END DESCRIPTION:
XS GIS Cut Line= 4
      2896480.94       10069889.      2897126.76     10069659.84
      2897699.67      10068927.2      2898194.83     10068522.07
#Sta/Elev= 30
    3981 1245.86  4223.2 1241.71    4233  1242.3  4286.1 1240.12  4349.8 1239.29
  4413.4 1236.72  4900.3 1232.08  4927.9 1229.96  4964.5 1229.41  4996.8  1224.4
  4999.5  1223.9  5002.8  1224.4  5020.6 1228.46  5070.3 1233.12  5080.9 1232.91
  5169.8  1231.8  5248.5 1232.24  5277.4 1233.51  5362.4 1232.16  5511.9 1232.16
  5590.3 1233.62  5675.8 1233.46    5759 1235.59  5768.4 1236.68  5782.8 1236.04
  5917.8  1240.8  5960.1  1243.7  6046.2 1243.94  6073.5 1245.94  6236.1 1251.46
#Mann= 6 ,-1 , 0
    3981     .05       0  4223.2     .16       0  4996.8     .07       0
  5002.8     .16       0  5080.9     .05       0    5759     .16       0
#XS Ineff= 6 ,-1
 4530.34 4572.51 1235.95 4661.67 4678.53 1234.54 4704.44 4736.97 1234.04
 5073.58 5269.61 1233.05 5284.06 5581.52  1233.5 5590.26 5689.61 1233.62
Permanent Ineff=
       T       T       T       T       T       T
Bank Sta=4900.3,5070.3
XS Rating Curve= 0 ,0
Exp/Cntr=0.3,0.1

Type RM Length L Ch R = 1 ,7592    ,696,696,696
BEGIN DESCRIPTION:
FLAT CREEK 2 16.0
END DESCRIPTION:
XS GIS Cut Line= 3
      2897331.63     10070222.32      2897553.84      10069927.2
      2898362.86     10069121.65
#Sta/Elev= 30
  4399.9 1238.11  4468.2 1237.97  4524.9 1235.56  4618.1 1232.83  4718.1 1225.68
  4780.8 1227.11  4810.4 1227.58  4852.8 1226.61  4895.3  1224.3  4930.6 1219.81
  4937.7 1221.19  4951.8 1221.55  4998.3 1219.54  5001.1 1219.04  5004.3 1219.54
    5008  1220.2  5036.7 1226.37  5050.8  1227.4  5112.3 1225.92  5248.8 1225.51
  5326.6 1227.11  5432.7 1225.93  5482.1 1227.02  5509.4 1226.53  5616.5 1233.18
  5715.5 1236.52  5774.2 1236.56    5864 1238.02  5899.4 1240.26    5911 1239.86
#Mann= 9 ,-1 , 0
  4399.9      .1       0  4524.9     .16       0  4780.8      .1       0
  4998.3     .07       0  5004.3      .1       0    5008     .16       0
  5112.3     .05       0  5509.4     .16       0  5774.2      .1       0
#XS Ineff= 3 ,-1
 4656.14 4811.59 1227.54 5064.91  5310.6 1226.86 5341.36 5607.27 1227.28
Permanent Ineff=
       T       T       T
Bank Sta=4852.8,5036.7
XS Rating Curve= 0 ,0
Exp/Cntr=0.3,0.1