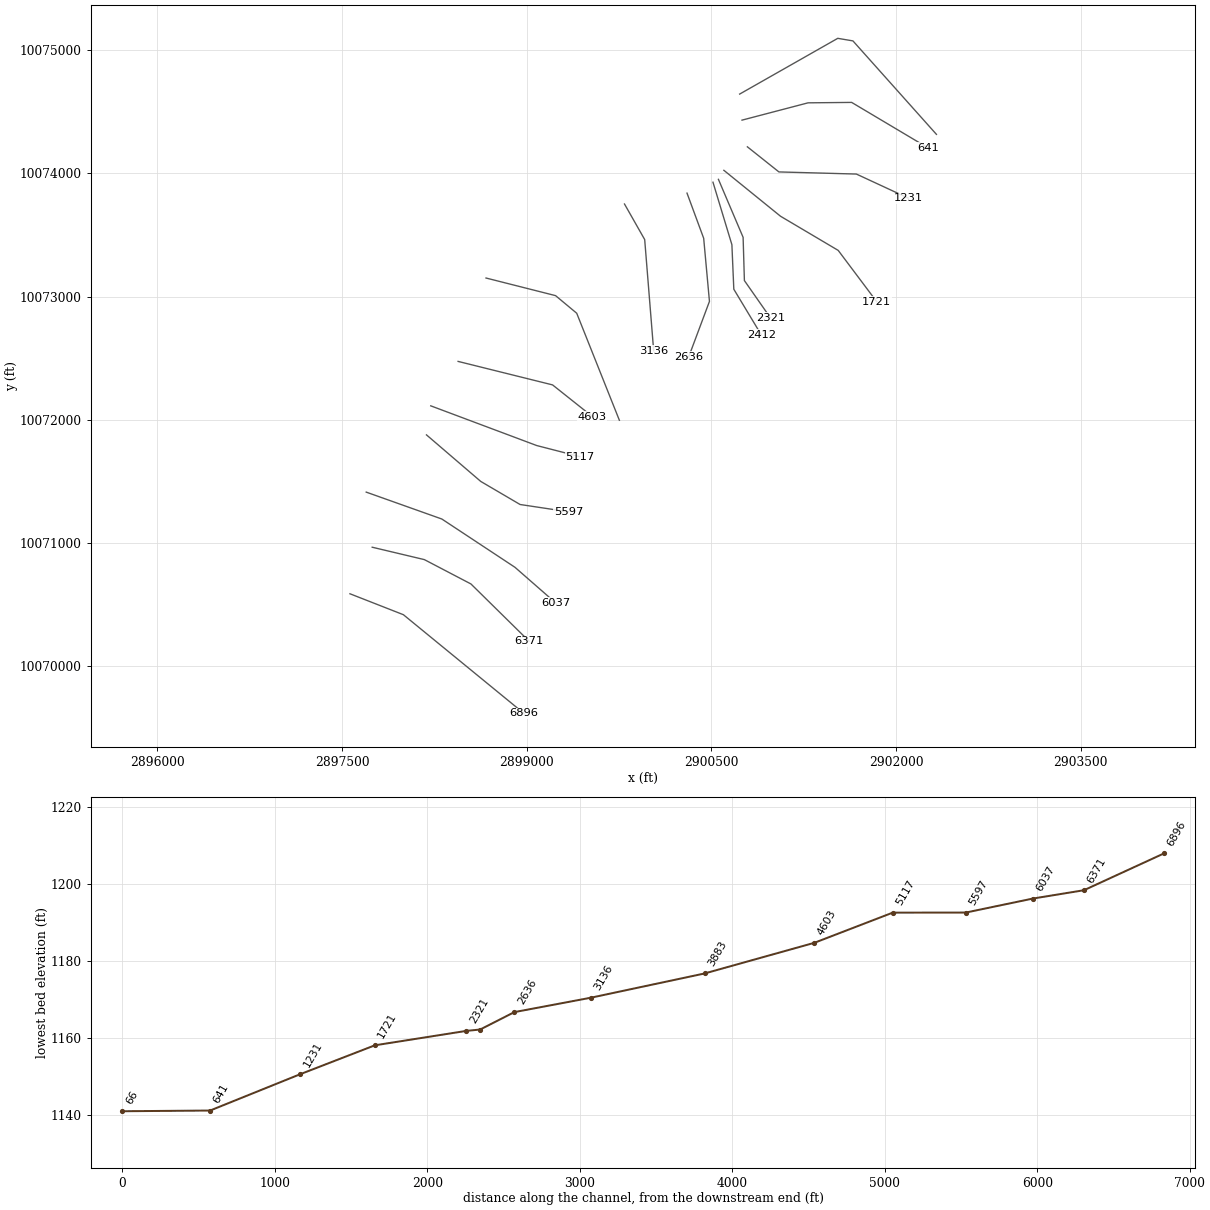
HEC-RAS study FLAT CREEK 2.prj: FLAT CREEK 2 Base Level Engineering

--- FLAT CREEK 2.g01 (geometry) --- (continued)

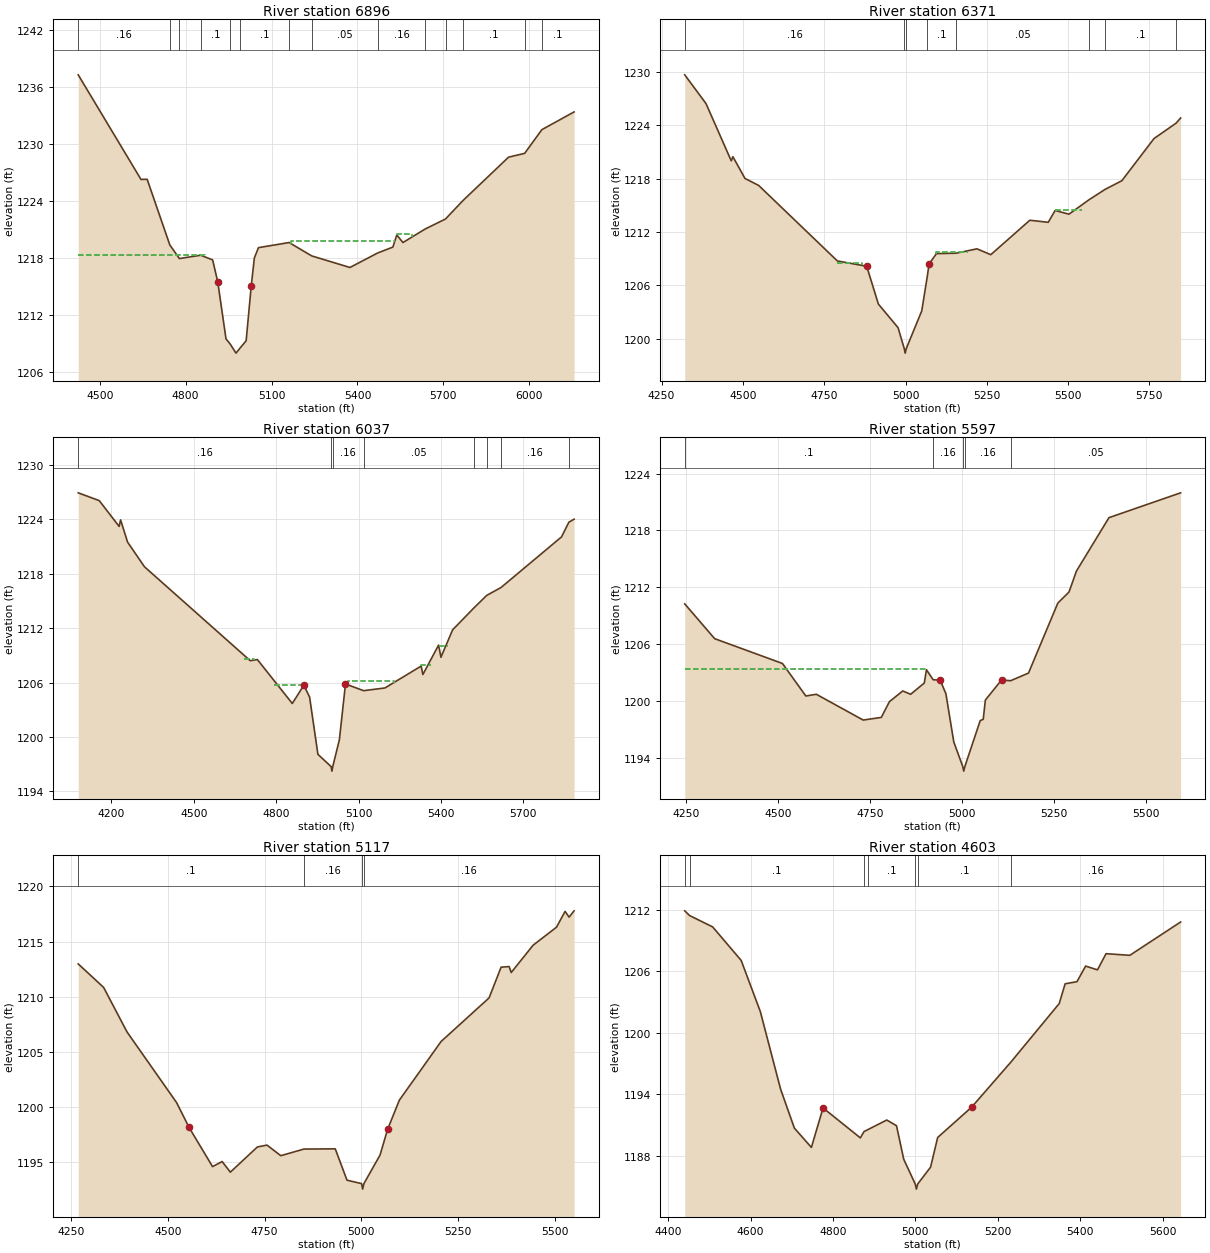
Type RM Length L Ch R = 1 ,6896    ,525,525,525
BEGIN DESCRIPTION:
FLAT CREEK 2 14.0
END DESCRIPTION:
XS GIS Cut Line= 3
      2897564.27     10070583.45      2897998.28     10070413.31
      2898977.44     10069611.24
#Sta/Elev= 30
  4424.7 1237.31    4644 1226.28  4665.5  1226.3  4744.6 1219.38    4778 1217.94
  4852.4 1218.29  4894.2  1217.8  4912.2 1215.46  4940.9 1209.47  4955.2 1208.94
  4975.8 1207.97  4990.4 1208.52  5011.2 1209.27 5028.98 1215.03  5039.9    1218
  5054.3 1219.09  5161.4 1219.63  5240.2 1218.22  5373.7    1217  5470.1 1218.52
  5523.7 1219.15  5537.4 1220.43  5558.9 1219.63  5636.8 1221.06  5707.5 1222.11
    5769 1224.07  5927.8 1228.63  5983.9 1229.03  6044.1 1231.53  6156.6  1233.4
#Mann= 14 ,-1 , 0
  4424.7     .16       0  4744.6      .1       0    4778     .16       0
  4852.4      .1       0  4955.2     .07       0  4990.4      .1       0
  5161.4      .1       0  5240.2     .05       0  5470.1     .16       0
  5636.8      .1       0  5707.5     .16       0    5769      .1       0
  5983.9     .05       0  6044.1      .1       0
#XS Ineff= 3 ,-1
  4424.7 4868.41 1218.36 5167.28 5530.83 1219.79 5537.18 5589.49  1220.5
Permanent Ineff=
       T       T       T
Bank Sta=4912.2,5028.98
XS Rating Curve= 0 ,0
Exp/Cntr=0.3,0.1

Type RM Length L Ch R = 1 ,6371    ,334,334,334
BEGIN DESCRIPTION:
FLAT CREEK 2 13.0
END DESCRIPTION:
XS GIS Cut Line= 4
      2897744.83     10070961.92      2898168.42     10070861.23
      2898546.89     10070663.31      2899018.75      10070198.4
#Sta/Elev= 30
  4321.1 1229.67  4386.5 1226.44  4464.1 1220.01  4469.2 1220.47  4506.3 1218.03
  4548.5 1217.24  4790.4 1208.76  4880.7 1208.16  4916.6 1203.91  4977.1 1201.26
  4996.2  1198.9    4999  1198.4  5002.2  1198.9  5049.9 1203.14  5066.8 1206.97
  5072.5 1208.42  5095.1 1209.58  5156.1 1209.63  5219.8 1210.12  5262.2 1209.46
  5382.3 1213.33  5438.9  1213.1  5460.2 1214.43  5502.6 1214.01    5565 1215.65
  5613.8  1216.8  5665.2 1217.77  5764.2 1222.51  5831.7 1224.23    5846 1224.82
#Mann= 8 ,-1 , 0
  4321.1     .16       0  4996.2     .07       0  5002.2     .16       0
  5066.8      .1       0  5156.1     .05       0    5565     .16       0
  5613.8      .1       0  5831.7     .05       0
#XS Ineff= 4 ,-1
 4789.96 4866.67 1208.57 5095.21 5192.42 1209.75 5220.09 5294.58 1210.11
 5460.38 5544.08 1214.47
Permanent Ineff=
       T       T       T       T
Bank Sta=4880.7,5072.5
XS Rating Curve= 0 ,0
Exp/Cntr=0.3,0.1

Type RM Length L Ch R = 1 ,6037    ,440,440,440
BEGIN DESCRIPTION:
FLAT CREEK 2 12.0
END DESCRIPTION:
XS GIS Cut Line= 4
      2897696.25     10071409.82      2898310.78     10071191.09
      2898904.53     10070798.73      2899236.88     10070507.92
#Sta/Elev= 30
    4079 1226.89  4155.7 1226.03    4228 1223.19  4233.3 1223.91  4258.8 1221.46
  4320.5 1218.74  4705.4  1208.4  4731.3 1208.53  4858.5 1203.69  4900.6  1205.7
  4921.6 1204.39  4951.8 1198.09  4999.9 1196.74  5002.7 1196.24  5005.9 1196.74
    5030  1199.7  5052.2 1205.84  5118.2  1205.1    5196  1205.4  5327.8 1207.81
    5334 1206.88  5391.2 1210.12  5399.8 1208.78  5442.3  1211.8  5519.1 1214.19
  5566.4 1215.59  5618.9 1216.47    5839 1222.04  5865.5 1223.65  5884.6 1223.99
#Mann= 8 ,-1 , 0
    4079     .16       0  4999.9     .07       0  5005.9     .16       0
  5118.2     .05       0  5519.1      .1       0  5566.4     .05       0
  5618.9     .16       0  5865.5      .1       0
#XS Ineff= 5 ,-1
 4684.09 4718.18 1208.62 4790.91 4894.32 1205.73 5061.36 5228.41 1206.13
 5326.14 5363.64 1207.92 5392.05 5423.86 1210.07
Permanent Ineff=
       T       T       T       T       T
Bank Sta=4900.6,5052.2
XS Rating Curve= 0 ,0
Exp/Cntr=0.3,0.1

Type RM Length L Ch R = 1 ,5597    ,480,480,480
BEGIN DESCRIPTION:
FLAT CREEK 2 11.0
END DESCRIPTION:
XS GIS Cut Line= 4
      2898185.79     10071875.12      2898626.76     10071496.65
       2898946.2     10071309.15      2899338.57     10071250.12
#Sta/Elev= 30
  4246.6 1210.25  4327.9 1206.58  4512.3 1203.96  4575.9 1200.53  4604.4 1200.71
  4731.8 1197.99  4781.1 1198.27  4803.1 1199.93  4839.4 1201.06  4860.9 1200.71
    4898  1201.9  4903.8  1203.3  4922.1 1202.24    4941 1202.21  4956.7 1200.77
  4978.1 1195.69  5002.4  1193.1  5005.2  1192.6  5008.4  1193.1    5050 1197.93
  5058.2 1198.07    5064  1200.1    5108 1202.22  5132.7 1202.14  5181.3 1202.95
  5261.1 1210.34  5291.4  1211.5  5311.6 1213.71  5400.1 1219.35  5594.9 1221.97
#Mann= 5 ,-1 , 0
  4246.6      .1       0  4922.1     .16       0  5002.4     .07       0
  5008.4     .16       0  5132.7     .05       0
#XS Ineff= 2 , 0
         4903.98 1203.36
Permanent Ineff=
       T       T
Bank Sta=4941,5108
XS Rating Curve= 0 ,0
Exp/Cntr=0.3,0.1

Type RM Length L Ch R = 1 ,5117    ,514,514,514
BEGIN DESCRIPTION:
FLAT CREEK 2 10.0
END DESCRIPTION:
XS GIS Cut Line= 3
      2898220.54     10072111.22      2899081.62     10071788.31
        2899431.     10071698.37
#Sta/Elev= 30
  4268.8 1212.98  4334.4 1210.85  4394.9 1206.81  4522.9 1200.41  4554.9 1198.17
  4615.7 1194.61  4640.4 1195.07  4661.7 1194.11  4731.4 1196.39  4756.3 1196.56
  4791.9  1195.6  4851.6  1196.2  4932.5 1196.22  4962.8 1193.38  5000.5 1193.07
  5003.3 1192.57  5006.5 1193.07  5048.2 1195.66  5067.6 1197.98    5098 1200.63
  5205.8 1205.95  5329.7  1209.9  5360.7 1212.68  5381.4 1212.74  5386.9  1212.2
  5443.3 1214.67  5503.9 1216.31  5525.9 1217.74  5536.3 1217.22  5549.2 1217.79
#Mann= 4 ,-1 , 0
  4268.8      .1       0  4851.6     .16       0  5000.5     .07       0
  5006.5     .16       0
Bank Sta=4554.9,5067.6
XS Rating Curve= 0 ,0
Exp/Cntr=0.3,0.1

Type RM Length L Ch R = 1 ,4603    ,720,720,720
BEGIN DESCRIPTION:
FLAT CREEK 2 9.0
END DESCRIPTION:
XS GIS Cut Line= 3
      2898442.71     10072472.35      2899210.09     10072281.37
      2899533.04      10072024.4
#Sta/Elev= 30
  4440.4 1211.88  4452.2 1211.42  4508.2 1210.31  4577.4 1207.04  4623.8 1202.06
    4673 1194.49  4706.5 1190.68  4747.8  1188.8  4776.1 1192.65  4866.6 1189.73
  4875.4 1190.34  4885.1 1190.54  4930.7 1191.47  4954.3 1190.92  4971.9 1187.65
  4999.8 1185.23  5002.6 1184.73  5005.8 1185.23    5037 1186.87  5054.3 1189.77
  5136.8 1192.73  5231.9 1197.12  5349.2 1202.83  5363.6 1204.76  5392.4 1204.97
  5413.3 1206.49  5442.1 1206.12  5462.9  1207.7  5520.6 1207.54  5643.9 1210.79
#Mann= 7 ,-1 , 0
  4440.4     .05       0  4452.2      .1       0  4875.4     .16       0
  4885.1      .1       0  4999.8     .07       0  5005.8      .1       0
  5231.9     .16       0
Bank Sta=4776.1,5136.8
XS Rating Curve= 0 ,0
Exp/Cntr=0.3,0.1

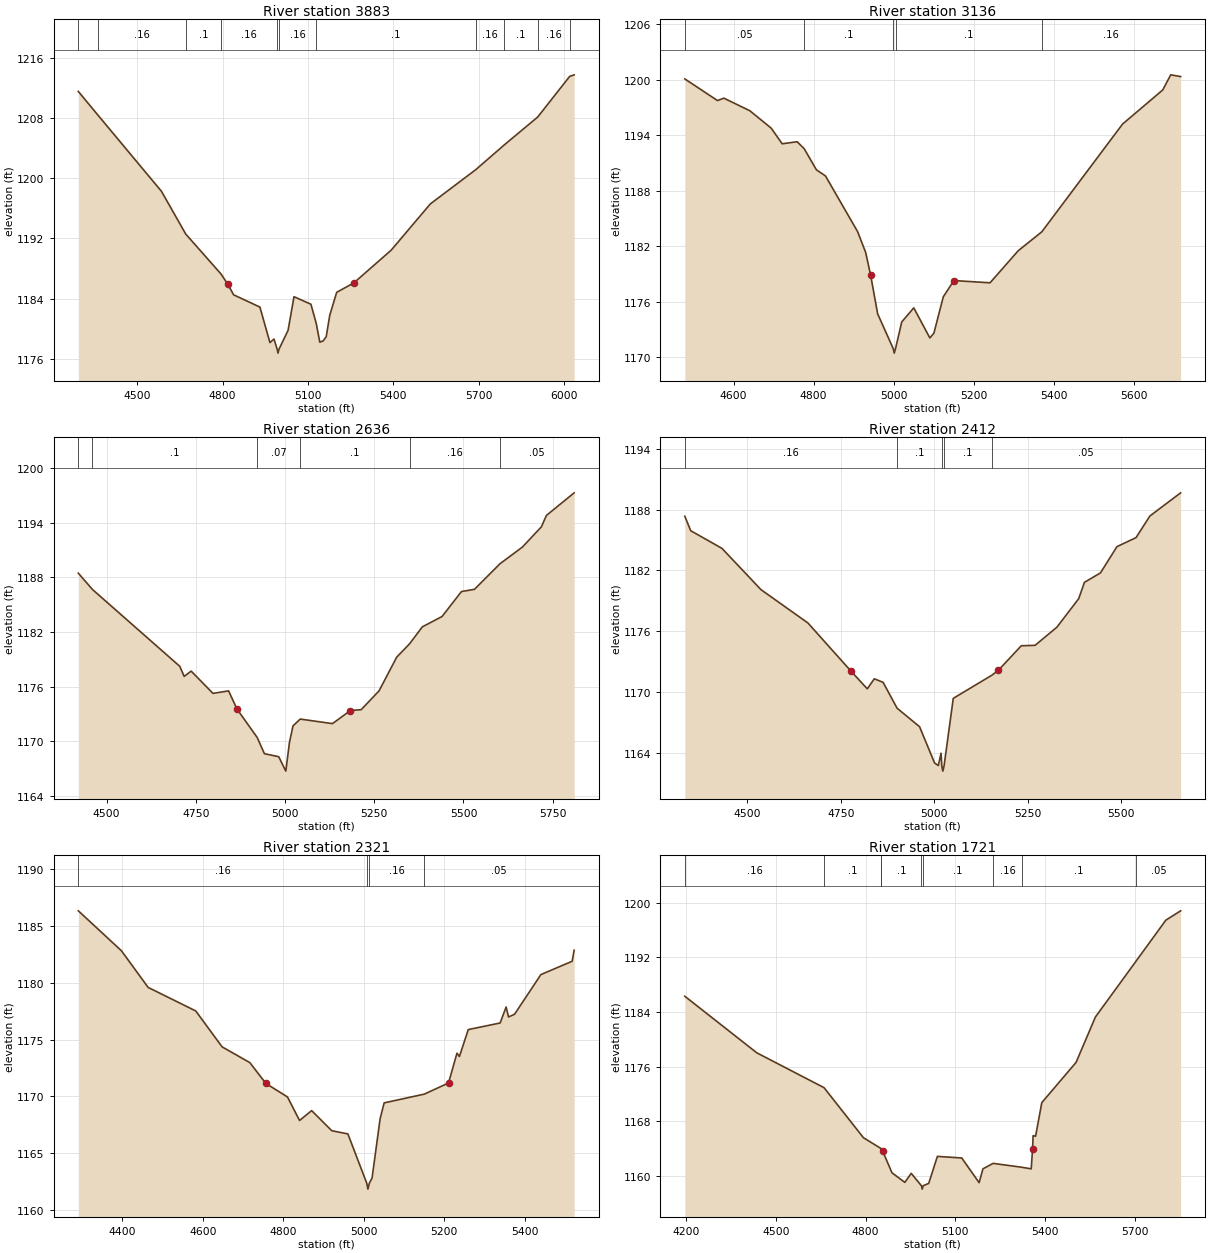
Type RM Length L Ch R = 1 ,3883    ,747,747,747
BEGIN DESCRIPTION:
FLAT CREEK 2 8.0
END DESCRIPTION:
XS GIS Cut Line= 4
       2898669.3     10073150.29      2899234.39     10073007.06
      2899406.27     10072863.83      2899752.62     10071994.05
#Sta/Elev= 30
  4293.2 1211.54  4360.7 1208.46  4585.4 1198.27  4670.9 1192.58  4794.7 1187.28
  4818.5 1185.93  4839.1 1184.51  4931.5 1182.88  4966.7 1178.16    4981 1178.63
  4992.3 1177.26  4995.1 1176.76  4998.3 1177.26  5030.5 1179.79  5051.3 1184.26
  5110.8 1183.26  5129.5 1180.71    5142 1178.22  5153.8 1178.38  5164.6 1178.95
  5177.1  1181.8  5201.3 1184.84  5261.5 1186.09  5392.8 1190.44  5530.5 1196.59
  5690.7 1201.16  5790.6 1204.44    5908 1208.14  6020.3 1213.54  6036.1 1213.75
#Mann= 11 ,-1 , 0
  4293.2      .1       0  4360.7     .16       0  4670.9      .1       0
  4794.7     .16       0  4992.3     .07       0  4998.3     .16       0
  5129.5      .1       0  5690.7     .16       0  5790.6      .1       0
    5908     .16       0  6020.3      .1       0
Bank Sta=4818.5,5261.5
XS Rating Curve= 0 ,0
Exp/Cntr=0.3,0.1

Type RM Length L Ch R = 1 ,3136    ,500,500,500
BEGIN DESCRIPTION:
FLAT CREEK 2 7.0
END DESCRIPTION:
XS GIS Cut Line= 3
      2899794.28     10073751.86      2899958.35     10073462.79
      2900031.27     10072559.12
#Sta/Elev= 30
  4478.2 1200.08  4559.9 1197.74  4575.8    1198  4640.7 1196.64  4694.1 1194.76
  4721.5 1193.07    4759 1193.29  4776.7 1192.53  4807.2 1190.25  4829.7  1189.6
    4910 1183.58    4930 1181.35  4942.5 1178.89  4960.1  1174.7  4998.9 1170.95
  5001.6 1170.45  5004.9 1170.95  5020.3 1173.82  5050.4 1175.34  5090.6 1172.09
  5100.6  1172.6  5124.2 1176.54  5150.7 1178.29    5241 1178.05  5311.3 1181.51
  5370.4 1183.56  5572.1  1195.2  5672.4 1198.88  5692.5 1200.52  5717.2 1200.33
#Mann= 5 ,-1 , 0
  4478.2     .05       0  4776.7      .1       0  4998.9     .07       0
  5004.9      .1       0  5370.4     .16       0
Bank Sta=4942.5,5150.7
XS Rating Curve= 0 ,0
Exp/Cntr=0.3,0.1

Type RM Length L Ch R = 1 ,2636    ,224,224,224
BEGIN DESCRIPTION:
FLAT CREEK 2 6.0
END DESCRIPTION:
XS GIS Cut Line= 4
      2900302.09     10073840.42      2900437.52     10073473.21
      2900484.39     10072960.19      2900315.42     10072507.86
#Sta/Elev= 30
  4420.8 1188.47  4460.4 1186.68    4705 1178.24  4717.4 1177.13    4737 1177.71
  4798.1 1175.26  4841.8 1175.54 4865.45 1173.54  4922.1 1170.41  4942.2 1168.64
  4982.4  1168.3  5002.2 1166.72  5012.5  1169.9  5022.5  1171.7  5042.6 1172.44
    5133 1171.94  5183.2 1173.38  5213.3 1173.47  5263.5 1175.54  5312.9 1179.24
    5349 1180.71  5384.7 1182.57    5440 1183.71  5494.4 1186.45  5530.9  1186.7
  5602.2  1189.5  5665.2 1191.34  5718.5 1193.57  5732.3 1194.81  5810.2  1197.3
#Mann= 6 ,-1 , 0
  4420.8     .16       0  4460.4      .1       0  4922.1     .07       0
  5042.6      .1       0    5349     .16       0  5602.2     .05       0
Bank Sta=4865.45,5183.2
XS Rating Curve= 0 ,0
Exp/Cntr=0.3,0.1

Type RM Length L Ch R = 1 ,2412    ,91,91,91
BEGIN DESCRIPTION:
FLAT CREEK 2 5.0
END DESCRIPTION:
XS GIS Cut Line= 4
      2900513.05     10073928.92      2900666.69     10073421.13
      2900682.31     10073059.15      2900905.65     10072687.77
#Sta/Elev= 30
  4332.3 1187.35  4348.2 1185.92  4431.7 1184.18    4536 1180.11  4661.6 1176.82
  4776.5 1172.08  4820.4 1170.32  4839.2 1171.31  4862.8 1170.96  4900.1 1168.41
  4960.3 1166.58  5000.3 1163.01  5010.4 1162.75  5017.7 1163.97  5019.7  1162.7
  5022.5  1162.2  5025.7  1162.7  5050.4 1169.38  5153.9 1171.67  5170.5 1172.13
  5232.3 1174.57  5269.2 1174.61  5327.5  1176.4  5385.8 1179.21  5401.3 1180.83
  5444.1 1181.76  5488.2 1184.35  5539.3 1185.24  5576.2 1187.37  5658.5 1189.66
#Mann= 5 ,-1 , 0
  4332.3     .16       0  4900.1      .1       0  5019.7     .07       0
  5025.7      .1       0  5153.9     .05       0
Bank Sta=4776.5,5170.5
XS Rating Curve= 0 ,0
Exp/Cntr=0.3,0.1

Type RM Length L Ch R = 1 ,2321    ,600,600,600
BEGIN DESCRIPTION:
FLAT CREEK 2 4.0
END DESCRIPTION:
XS GIS Cut Line= 4
      2900557.33     10073952.33      2900757.83     10073481.02
      2900768.25     10073129.46       2900978.7     10072828.07
#Sta/Elev= 30
    4291 1186.33  4398.2 1182.81  4464.4 1179.59  4582.6 1177.52  4648.1 1174.36
  4717.1 1172.97  4756.8 1171.14  4810.5 1169.95  4840.5 1167.88  4870.5 1168.75
  4920.5 1166.98  4960.5  1166.7  5007.6 1162.34  5010.3 1161.84  5013.6 1162.34
  5020.6 1162.82  5040.6 1168.04  5050.6 1169.43  5150.3  1170.2  5210.5 1171.18
  5231.4  1173.8  5237.5 1173.51  5259.5 1175.88  5338.7 1176.46  5353.5 1177.87
  5359.6 1176.99  5374.5 1177.23  5439.9 1180.72  5517.5 1181.89  5522.5 1182.86
#Mann= 4 ,-1 , 0
    4291     .16       0  5007.6     .07       0  5013.6     .16       0
  5150.3     .05       0
Bank Sta=4756.8,5210.5
XS Rating Curve= 0 ,0
Exp/Cntr=0.3,0.1

Type RM Length L Ch R = 1 ,1721    ,490,490,490
BEGIN DESCRIPTION:
FLAT CREEK 2 3.0
END DESCRIPTION:
XS GIS Cut Line= 4
      2900601.56     10074025.75      2901061.65     10073652.46
       2901530.4     10073374.68      2901842.61      10072958.4
#Sta/Elev= 30
  4195.3 1186.32    4436 1178.04  4660.8 1172.94  4792.5 1165.62  4850.3 1164.06
  4851.7 1163.98  4856.8 1163.66    4888 1160.48  4930.9 1159.08  4952.3  1160.4
  4986.4 1158.59  4989.1 1158.09  4992.4 1158.59  5010.8 1158.93  5039.8 1162.88
  5121.2 1162.65  5179.3 1159.04  5192.1 1161.06  5226.2 1161.86    5322 1161.29
  5353.5 1161.06 5357.95 1163.89  5359.8 1165.92  5368.1 1165.83  5388.9 1170.75
  5503.5 1176.64  5568.1 1183.28  5703.9 1191.45  5803.5 1197.45    5853 1198.82
#Mann= 9 ,-1 , 0
  4195.3     .16       0  4660.8      .1       0  4850.3     .16       0
  4851.7      .1       0  4986.4     .07       0  4992.4      .1       0
  5226.2     .16       0    5322      .1       0  5703.9     .05       0
Bank Sta=4856.8,5357.95
XS Rating Curve= 0 ,0
Exp/Cntr=0.3,0.1

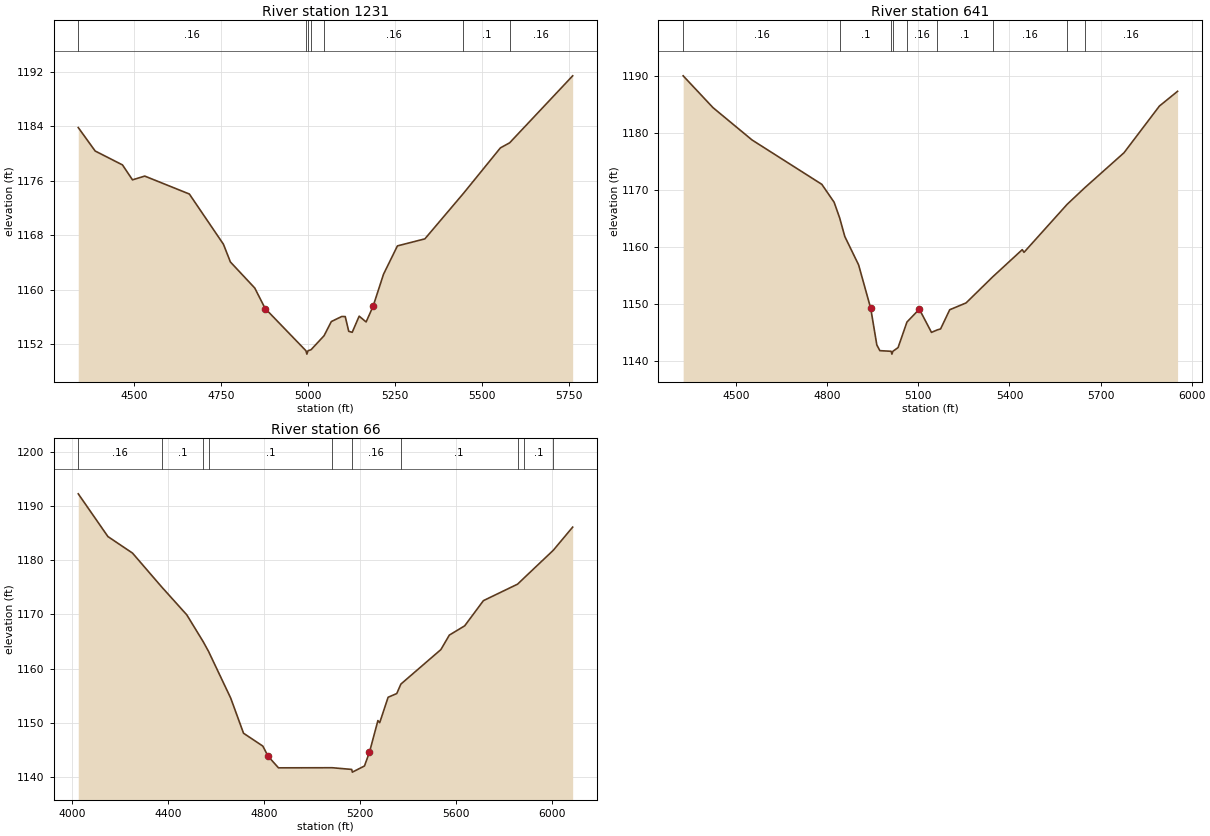
Type RM Length L Ch R = 1 ,1231    ,590,590,590
BEGIN DESCRIPTION:
FLAT CREEK 2 2.0
END DESCRIPTION:
XS GIS Cut Line= 4
      2900792.56     10074216.69      2901048.63     10074012.71
      2901677.97     10073995.34        2902099.     10073800.02
#Sta/Elev= 30
  4338.7 1183.81  4387.3 1180.37  4465.8 1178.33  4494.6 1176.14  4529.8 1176.69
    4658 1174.06    4756 1166.69    4776 1164.09    4846 1160.27    4876 1157.26
  4993.1 1151.07  4995.8 1150.57  4999.1 1151.07  5007.7 1151.21  5045.2 1153.27
  5066.1 1155.35  5096.1 1156.09  5106.1 1156.08  5116.1 1153.92  5126.1 1153.77
  5146.1 1156.14  5166.1 1155.29  5186.1 1157.58  5216.1 1162.29  5256.1 1166.45
    5335 1167.48  5445.3 1174.12  5552.1 1180.83  5578.6 1181.57  5759.8  1191.4
#Mann= 7 ,-1 , 0
  4338.7     .16       0  4993.1     .07       0  4999.1     .16       0
  5007.7      .1       0  5045.2     .16       0  5445.3      .1       0
  5578.6     .16       0
Bank Sta=4876,5186.1
XS Rating Curve= 0 ,0
Exp/Cntr=0.3,0.1

Type RM Length L Ch R = 1 ,641     ,575,575,575
BEGIN DESCRIPTION:
Mapping XS 820ee491
END DESCRIPTION:
XS GIS Cut Line= 4
      2900748.91      10074433.7      2901285.36     10074574.33
      2901639.53      10074577.8      2902257.57     10074209.75
#Sta/Elev= 30
  4325.6 1190.05  4423.8 1184.46  4552.6 1178.77  4782.2 1170.98  4822.6 1167.84
  4840.9 1165.09  4857.8 1161.82  4903.3 1156.83  4943.3 1149.16  4963.3 1142.76
  4973.3 1141.75  5010.3 1141.64    5013 1141.14  5016.3 1141.64  5033.3 1142.29
  5062.5 1146.78  5103.3 1149.04  5143.3 1144.96    5163 1145.41  5173.3 1145.57
  5203.3 1148.94  5257.2 1150.14  5344.7 1154.71  5442.2  1159.5    5448 1159.03
  5589.7 1167.45  5647.4 1170.35  5777.1 1176.52  5893.9 1184.74  5953.7 1187.33
#Mann= 9 ,-1 , 0
  4325.6     .16       0  4840.9      .1       0  5010.3     .07       0
  5016.3      .1       0  5062.5     .16       0    5163      .1       0
  5344.7     .16       0  5589.7      .1       0  5647.4     .16       0
#XS Ineff= 2 , 0
                         5104.09         1148.94
Permanent Ineff=
       T       T
Bank Sta=4943.3,5103.3
XS Rating Curve= 0 ,0
Exp/Cntr=0.3,0.1

Type RM Length L Ch R = 1 ,66      ,0,0,0
BEGIN DESCRIPTION:
FLAT CREEK 2 1.0
END DESCRIPTION:
XS GIS Cut Line= 4
      2900729.77     10074645.49      2901526.68     10075098.63
      2901649.94      10075077.8      2902328.18     10074318.04
#Sta/Elev= 30
  4025.9 1192.21  4149.5 1184.34  4251.9  1181.3  4373.2 1175.08  4478.2 1169.92
  4547.2 1164.93  4568.7  1163.2  4661.2 1154.59  4714.6 1148.12  4795.1 1145.75
  4816.9 1143.88  4860.2 1141.75  5083.9 1141.77  5165.3 1141.46  5168.1 1140.96
  5218.5 1142.09  5239.4 1144.64  5274.5 1150.45    5282 1150.07  5317.1 1154.75
  5353.1 1155.43  5370.2 1157.17    5537 1163.53  5572.1 1166.19  5636.1  1167.9
  5714.2 1172.54  5856.7 1175.58  5882.7 1176.68  6005.2 1181.81  6086.1 1186.08
#Mann= 10 ,-1 , 0
  4025.9     .16       0  4373.2      .1       0  4547.2     .16       0
  4568.7      .1       0  5083.9     .07       0  5165.3     .16       0
  5370.2      .1       0  5856.7     .16       0  5882.7      .1       0
  6005.2     .16       0
Bank Sta=4816.9,5239.4
XS Rating Curve= 0 ,0
Exp/Cntr=0.3,0.1

Chan Stop Cuts=-1
Use User Specified Reach Order=0
Composite Channel Slope=5