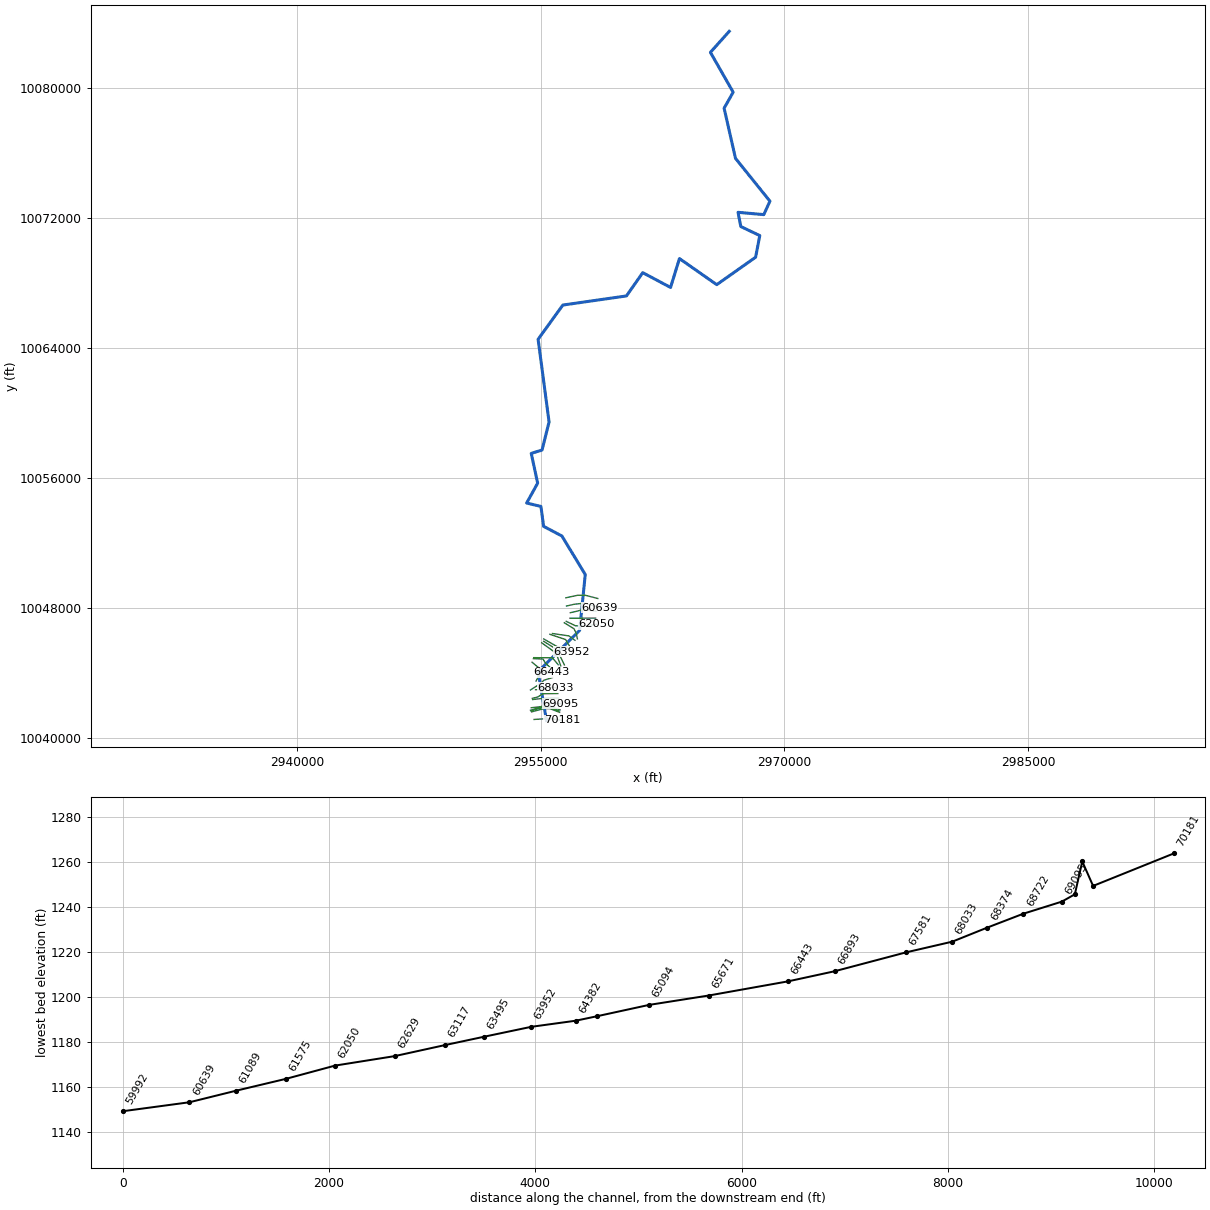
--- FLAT CREEK.prj (project) ---

Proj Title=FLAT CREEK Base Level Engineering
Current Plan=p01
Default Exp/Contr=0.3,0.1
English Units
Geom File=g01
Flow File=f01
Plan File=p01
Y Axis Title=Elevation
X Axis Title(PF)=Main Channel Distance
X Axis Title(XS)=Station
BEGIN DESCRIPTION:
FLAT CREEK
END DESCRIPTION:
DSS File=dss
DSS Export Rating Curves= 0
DSS Export Rating Curve Sorted= 0
DSS Export Volume Flow Curves= 0
DXF OffsetX= 0
DXF OffsetY= 0
DXF ScaleX= 1
DXF ScaleY= 10

--- FLAT CREEK.p01 (plan) ---

Plan Title=Multiple Run
Program Version=4.10
Short Identifier=Multiple Run
Geom File=g01
Flow File=f01
Subcritical Flow
K Sum by GR= 0
Std Step Tol= 0.01
Critical Tol= 0.01
Num of Std Step Trials= 20
Max Error Tol= 0.3
Flow Tol Ratio= 0.001
Split Flow NTrial= 30
Split Flow Tol= 0.02
Split Flow Ratio= 0.02
Log Output Level= 0
Friction Slope Method= 1
Unsteady Friction Slope Method= 2
Unsteady Bridges Friction Slope Method= 1
Parabolic Critical Depth
Global Vel Dist= 1 , 1 , 1
Global Log Level= 0
CheckData=True
Encroach Param=-1 ,0,0, 0
BEGIN DESCRIPTION:
Multiple Run
END DESCRIPTION:
Computation Interval=1HOUR
Output Interval=1HOUR
Run HTab= 0
Run UNet= 0
Run PostProcess= 0
Run WQNet= 0
UNET Theta= 1
UNET Theta Warmup= 1
UNET ZTol= 0.02
UNET ZSATol= 0.05
UNET MxIter= 20
UNET MaxInSteps= 0
UNET DtIC= 0
UNET DtMin= 0
UNET MaxCRTS= 20
UNET WFStab= 2
UNET SFStab= 1
UNET WFX= 1
UNET SFX= 1
UNET DSS MLevel= 4
UNET DZMax Abort= 100
UNET Convert EG Bridges= 0
UNET Use Existing IB Tables=-1
UNET Froude Reduction=False
UNET Froude Limit= 1
UNET Froude Power= 10
UNET Time Slicing=0,0, 5
UNET Junction Losses=0
Instantaneous Interval=1HOUR
DSS File=dss
Write IC File= 0
Write IC File at Sim End=0
Echo Input=False
Echo Parameters=False
Echo Output=False
Write Detailed= 0
WQ AD Non Conservative
WQ ULTIMATE=-1
WQ Max Comp Step=1HOUR
WQ Output Interval=15MIN
WQ Output Selected Increments= 0
WQ Output face flow=0
WQ Output face velocity=0
WQ Output face area=0
WQ Output face dispersion=0
WQ Output cell volume=0
WQ Output cell surface area=0
WQ Output cell continuity=0
WQ Output cumulative cell continuity=0
WQ Output face conc=0
WQ Output face dconc_dx=0
WQ Output face courant=0
WQ Output face peclet=0
WQ Output face adv mass=0
WQ Output face disp mass=0
WQ Output cell mass=0
WQ Output cell source sink temp=0
WQ Output cell source sink nsm=0
WQ Output MaxMinRange=-1
WQ Daily Max Min Mean=-1
WQ Daily Range=0
WQ Daily Time=0
WQ Create Restart=0
WQ Fixed Restart=0
WQ System Summary=0
WQ Use Fixed Temperature=0
Sorting and Armoring Iterations= 10
XS Update Threshold= 0.02
Hydraulics Update Threshold= 0.02
Energy Slope Method= 1
Volume Change Method= 0
XS Weighting Method= 0
Number of US Weighted Cross Sections= 1
Number of DS Weighted Cross Sections= 1
Upstream XS Weight=0.25
Main XS Weight=0.5
Downstream XS Weight=0.25
Number of DS XS's Weighted with US Boundary= 1
Upstream Boundary Weight= 1
Weight of XSs Associated with US Boundary= 0
Number of US XS's Weighted with DS Boundary= 1
Downstream Boundary Weight= 0.5
Weight of XSs Associated with DS Boundary= 0.5
Sediment Output Level= 4
Mass or Volume Output= 0
Output Increment Type= 1
Profile and TS Output Increment= 10
XS Output Flag= 0
XS Output Increment= 10
Disregard all LS=0
Disregard all Conn=0
Disregard all Breaches=0
Disregard all Pumps=0

--- FLAT CREEK.f01 (steady flow) ---

Flow Title=Multiple
Program Version=4.10
Number of Profiles= 7
Profile Names=10-year,25-year,50-year,1pct_min,100-year,1pct_plu,500-year
River Rch & RM=FLAT CREEK,Reach-1         ,70181
     935    1362    1736    1621    2192    2965    3507
River Rch & RM=FLAT CREEK,Reach-1         ,67581
    1398    2075    2677    2527    3417    4621    5586
River Rch & RM=FLAT CREEK,Reach-1         ,63117
    2015    3045    3975    3792    5128    6935    8569
River Rch & RM=FLAT CREEK,Reach-1         ,60639
    2317    3504    4577    4363    5900    7979    9845
River Rch & RM=FLAT CREEK,Reach-1         ,51781
    3129    4784    6294    6036    8164   11040   13793
River Rch & RM=FLAT CREEK,Reach-1         ,44472
    3387    5190    6838    6566    8879   12008   15037
River Rch & RM=FLAT CREEK,Reach-1         ,40393
    3565    5462    7195    6905    9339   12630   15801
River Rch & RM=FLAT CREEK,Reach-1         ,33871
    3845    5909    7799    7498   10141   13714   17220
River Rch & RM=FLAT CREEK,Reach-1         ,33435
    3845    5909    7799    7498   10141   13714   17220
River Rch & RM=FLAT CREEK,Reach-1         ,31798
    5600    8712   11595   11230   15187   20538   26165
River Rch & RM=FLAT CREEK,Reach-1         ,23653
    5874    9149   12187   11812   15974   21603   27559
River Rch & RM=FLAT CREEK,Reach-1         ,20999
    8159   12826   17195   16761   22667   30654   39547
River Rch & RM=FLAT CREEK,Reach-1         ,15583
    8217   12906   17292   16844   22779   30807   39689
River Rch & RM=FLAT CREEK,Reach-1         ,10584
    8238   12923   17300   16837   22769   30793   39597
River Rch & RM=FLAT CREEK,Reach-1         ,5147
    8877   13950   18697   18215   24633   33314   42924
River Rch & RM=FLAT CREEK,Reach-1         ,4817
    8877   13950   18697   18215   24633   33314   42924
Boundary for River Rch & Prof#=FLAT CREEK,Reach-1         , 1
Up Type= 0
Dn Type= 3
Dn Slope=0.005
Boundary for River Rch & Prof#=FLAT CREEK,Reach-1         , 2
Up Type= 0
Dn Type= 3
Dn Slope=0.005
Boundary for River Rch & Prof#=FLAT CREEK,Reach-1         , 3
Up Type= 0
Dn Type= 3
Dn Slope=0.005
Boundary for River Rch & Prof#=FLAT CREEK,Reach-1         , 4
Up Type= 0
Dn Type= 3
Dn Slope=0.005
Boundary for River Rch & Prof#=FLAT CREEK,Reach-1         , 5
Up Type= 0
Dn Type= 3
Dn Slope=0.005
Boundary for River Rch & Prof#=FLAT CREEK,Reach-1         , 6
Up Type= 0
Dn Type= 3
Dn Slope=0.005
Boundary for River Rch & Prof#=FLAT CREEK,Reach-1         , 7
Up Type= 0
Dn Type= 3
Dn Slope=0.005
DSS Import GetInterval= 0
DSS Import GetPeak= 0
DSS Import FillOption= 0

--- FLAT CREEK.g01 (geometry) ---

Geom Title=Existing Conditions
Program Version=4.10

River Reach=FLAT CREEK      ,Reach-1
Reach XY= 30
      2955358.07     10041054.21      2954841.33     10044052.42
      2957398.47     10046593.73      2957744.57       10050033.
       2956307.9     10052403.58      2955182.52     10052997.72
      2955016.51     10054222.79      2954137.83     10054432.12
      2954815.43     10055656.87      2954420.06     10057488.07
       2955086.4     10057694.01      2955518.33     10059419.04
      2954843.55     10064512.09      2956366.08      10066618.1
      2960280.85     10067179.67      2961283.91     10068611.91
      2962994.81     10067701.64      2963542.82     10069480.01
      2965837.05     10067873.48      2968230.09     10069562.25
      2968487.41     10070893.42      2967320.21     10071450.68
      2967147.71     10072326.74      2968732.51     10072184.48
      2969111.92     10073010.37      2966992.96     10075646.91
      2966291.41      10078734.7      2966848.98     10079717.66
      2965448.87     10082173.16      2966608.09      10083466.9

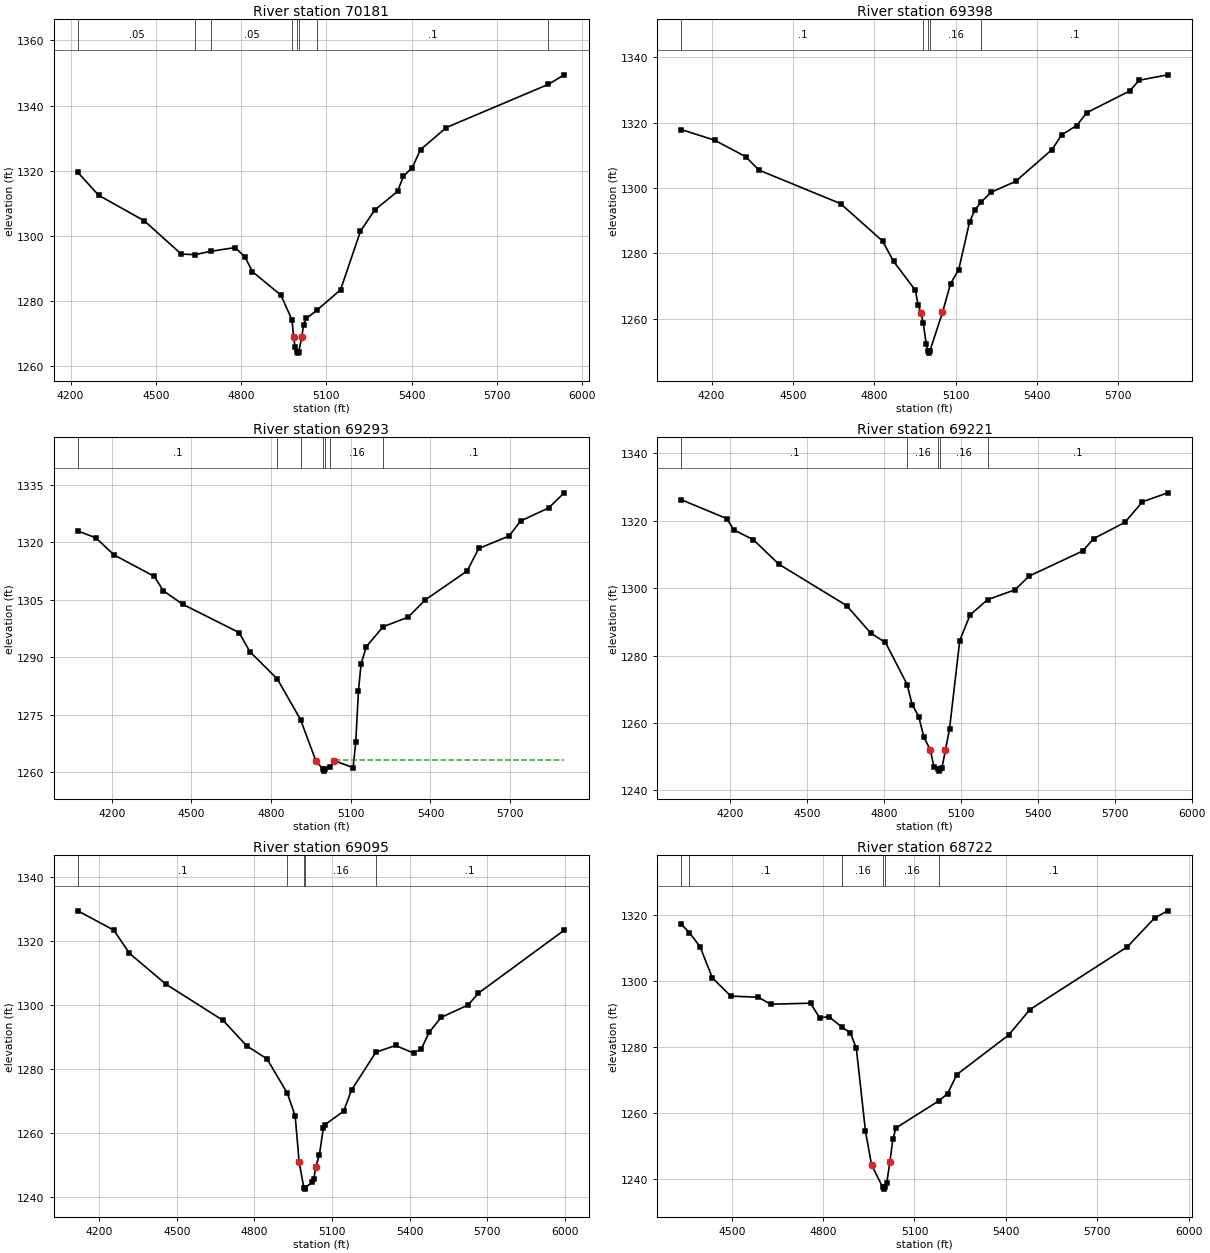
Type RM Length L Ch R = 1 ,70181   ,783,783,783
BEGIN DESCRIPTION:
FLAT CREEK 143.0
END DESCRIPTION:
XS GIS Cut Line= 4
       2954595.5     10041111.56      2955179.25     10041150.62
      2955665.36     10041152.79      2956299.08     10041063.81
#Sta/Elev= 30
  4225.5 1319.43  4298.6 1312.42    4459 1304.58  4589.3 1294.34  4637.5 1294.16
  4693.5  1295.2  4778.5 1296.34  4812.7 1293.55  4839.8 1288.93  4939.8 1281.73
  4978.9 1274.09 4984.43 1269.01  4989.8 1265.65  4996.8  1264.4  4999.5  1263.9
  5002.8  1264.4 5013.07 1268.76  5019.8 1272.68  5029.8 1274.59    5067 1277.12
  5149.8 1283.38  5219.8 1301.39  5269.8 1307.86  5350.3 1313.62  5370.5 1318.22
  5401.8  1320.9  5431.1 1326.45    5522 1333.24  5879.7 1346.46  5936.6 1349.43
#Mann= 8 ,-1 , 0
  4225.5     .05       0  4637.5     .16       0  4693.5     .05       0
  4978.9     .16       0  4996.8     .07       0  5002.8     .16       0
    5067      .1       0  5879.7     .16       0
Bank Sta=4984.43,5013.07
XS Rating Curve= 0 ,0
Exp/Cntr=0.3,0.1

Type RM Length L Ch R = 1 ,69398   ,105,105,105
BEGIN DESCRIPTION:
Mapping XS 1582488d
END DESCRIPTION:
XS GIS Cut Line= 4
      2954442.23     10041577.63      2955191.36     10041778.83
      2955561.65     10041778.83      2956167.43     10041549.79
#Sta/Elev= 30
  4088.9 1317.89  4211.6 1314.63  4326.4 1309.58  4374.9 1305.48  4675.9 1295.21
  4830.7 1283.75  4871.7  1277.5  4951.7 1268.67  4961.7  1264.3  4971.7 1261.85
  4980.6 1258.79  4991.7 1252.31  4998.7 1249.92  5001.4 1249.42  5004.7 1249.92
  5051.7 1261.87  5081.7 1270.72  5111.7    1275  5151.7 1289.59  5171.7 1293.33
  5195.3 1295.77  5230.8 1298.69  5321.1    1302    5456 1311.78  5491.5 1316.28
  5546.5 1319.12  5584.3 1323.09  5741.7 1329.69  5777.2    1333  5882.5 1334.66
#Mann= 5 ,-1 , 0
  4088.9      .1       0  4980.6     .16       0  4998.7     .07       0
  5004.7     .16       0  5195.3      .1       0
Bank Sta=4971.7,5051.7
XS Rating Curve= 0 ,0
Exp/Cntr=0.3,0.1

Type RM Length L Ch R = 1 ,69293   ,72,72,72
BEGIN DESCRIPTION:
Mapping XS efe637bd
END DESCRIPTION:
XS GIS Cut Line= 4
      2954404.56     10041641.08       2955233.5     10041875.45
      2955476.56     10041868.94      2956163.97     10041632.57
#Sta/Elev= 30
  4072.1 1322.94  4140.3  1321.1  4208.3 1316.68  4359.7 1311.09  4393.7 1307.36
  4466.8 1303.82  4678.9 1296.45  4720.2 1291.44  4823.6  1284.3  4910.7 1273.73
  4968.5 1262.99  4995.5 1260.82  4998.3 1260.32  5001.5 1260.82  5020.8 1261.31
  5038.5 1263.03  5108.6 1261.23  5118.6 1267.92  5128.6 1281.12  5138.6 1288.31
  5158.6 1292.79  5221.4 1297.95  5316.2 1300.46  5379.6 1304.92  5538.2  1312.5
  5581.5 1318.35  5695.8  1321.6  5739.2 1325.51  5844.9 1328.92  5903.6 1332.86
#Mann= 7 ,-1 , 0
  4072.1      .1       0  4823.6     .16       0  4910.7      .1       0
  4995.5     .07       0  5001.5      .1       0  5020.8     .16       0
  5221.4      .1       0
#XS Ineff= 2 , 0
                         5046.59          1263.3
Permanent Ineff=
       T       T
Bank Sta=4968.5,5038.5
XS Rating Curve= 0 ,0
Exp/Cntr=0.3,0.1

Type RM Length L Ch R = 1 ,69221   ,126,126,126
BEGIN DESCRIPTION:
FLAT CREEK 142.0
END DESCRIPTION:
XS GIS Cut Line= 4
       2954371.6     10041678.23      2955234.17     10041939.36
      2955527.41     10041928.66      2956193.11     10041706.04
#Sta/Elev= 30
  4010.1 1326.23    4187 1320.64  4214.7 1317.28    4291 1314.37  4389.8 1307.13
  4654.6 1294.82  4748.6 1286.65  4805.9 1283.88  4890.6 1271.39  4909.9 1265.42
  4935.6  1261.9  4955.7 1255.79 4980.68 1252.02  4995.7 1246.77  5012.7 1246.19
  5015.4 1245.69  5018.7 1246.19  5025.7 1246.51 5039.77 1251.89  5055.7 1258.23
  5095.7 1284.45  5135.8 1292.04  5204.1 1296.59  5311.3  1299.5  5365.7 1303.56
  5574.9 1311.02  5618.4 1314.73  5739.5 1319.51  5807.9 1325.62  5906.7 1328.29
#Mann= 5 ,-1 , 0
  4010.1      .1       0  4890.6     .16       0  5012.7     .07       0
  5018.7     .16       0  5204.1      .1       0
Bank Sta=4980.68,5039.77
XS Rating Curve= 0 ,0
Exp/Cntr=0.3,0.1

Type RM Length L Ch R = 1 ,69095   ,373,373,373
BEGIN DESCRIPTION:
FLAT CREEK 141.0
END DESCRIPTION:
XS GIS Cut Line= 4
      2954420.53     10041833.78       2955042.1     10041903.22
      2955385.85     10042125.45      2956229.63     10042087.25
#Sta/Elev= 30
    4118 1329.39  4257.3 1323.32  4317.2 1316.13    4458 1306.48  4679.4 1295.13
  4770.4  1287.2    4849 1283.12  4927.9 1272.32  4957.8 1265.28    4973 1250.94
  4991.1 1242.93  4993.8 1242.43  4997.1 1242.93  5024.4 1244.63  5030.4 1245.73
  5036.8 1249.31  5051.5 1253.24  5066.6 1261.54  5072.6 1262.56  5145.2 1266.79
  5175.4 1273.37  5269.5  1285.2  5345.6 1287.31  5415.6 1284.94  5445.7 1286.33
  5475.7 1291.45  5521.5 1296.08  5625.9 1299.96  5665.9 1303.67  5997.4 1323.34
#Mann= 5 ,-1 , 0
    4118      .1       0  4927.9     .16       0  4991.1     .07       0
  4997.1     .16       0  5269.5      .1       0
Bank Sta=4973,5036.8
XS Rating Curve= 0 ,0
Exp/Cntr=0.3,0.1

Type RM Length L Ch R = 1 ,68722   ,348,348,348
BEGIN DESCRIPTION:
FLAT CREEK 140.0
END DESCRIPTION:
XS GIS Cut Line= 3
      2954507.38     10042337.25      2955000.43     10042396.28
      2956101.16     10042396.28
#Sta/Elev= 30
  4334.4 1317.06  4360.5 1314.58  4395.9 1310.28  4436.2 1300.87  4496.6 1295.39
  4587.3 1295.03  4627.6 1292.93  4758.5 1293.24  4788.7 1288.79  4818.9 1289.18
  4862.7 1285.92    4889 1284.34    4909  1279.6    4939 1254.56    4959 1244.38
    4996 1237.55  4998.8 1237.05    5002 1237.55    5009 1239.03    5019 1245.16
    5029 1252.15    5039 1255.53  5180.2 1263.74    5209 1265.93    5239 1271.68
    5409  1283.6    5479 1291.31    5799 1310.26    5889 1319.04  5931.7 1321.15
#Mann= 6 ,-1 , 0
  4334.4     .16       0  4360.5      .1       0  4862.7     .16       0
    4996     .07       0    5002     .16       0  5180.2      .1       0
Bank Sta=4959,5019
XS Rating Curve= 0 ,0
Exp/Cntr=0.3,0.1

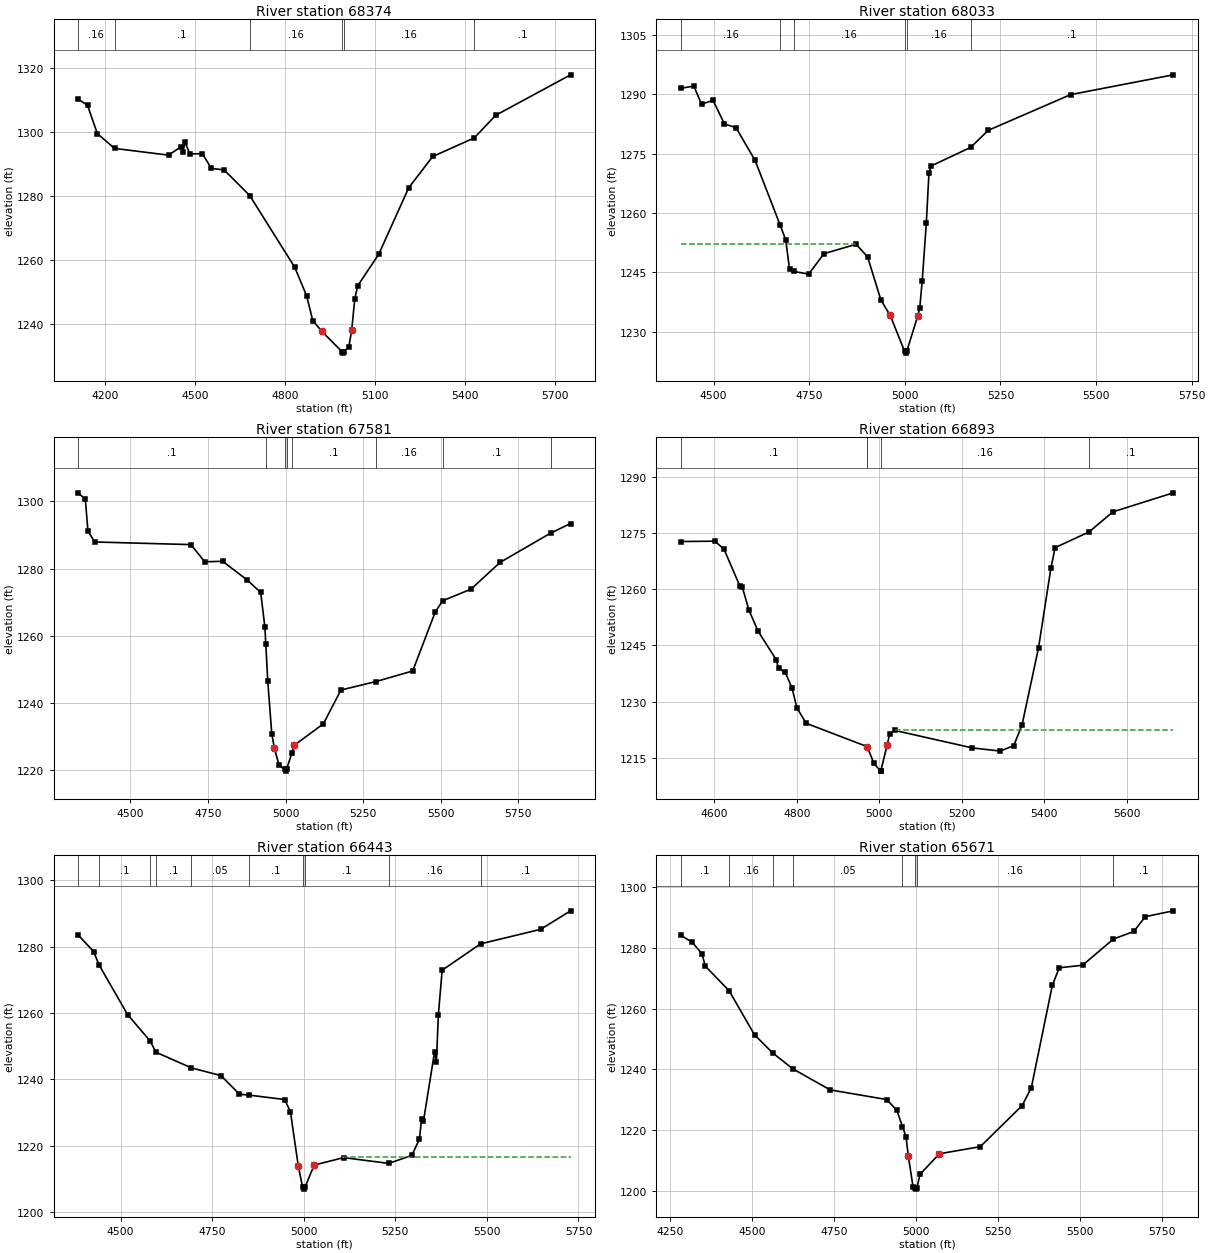
Type RM Length L Ch R = 1 ,68374   ,341,341,341
BEGIN DESCRIPTION:
FLAT CREEK 139.0
END DESCRIPTION:
XS GIS Cut Line= 4
      2954486.55     10042410.17      2954826.82     10042496.97
       2955128.9     10042694.89      2956057.89     10042708.76
#Sta/Elev= 30
  4110.2 1310.32  4141.4  1308.4  4174.1 1299.56  4231.4 1294.92  4411.5 1292.81
  4452.7 1295.42  4459.6 1293.95  4466.9 1296.93    4482  1293.2  4524.2 1293.26
  4554.4 1288.66  4596.6 1288.21  4682.2 1280.17  4832.1 1257.75  4872.1 1248.76
  4892.1 1241.09  4922.1 1237.77  4989.1  1231.4  4991.8  1230.9  4995.1  1231.4
  5012.1 1232.73  5022.1 1238.05  5032.1 1247.78  5042.1 1251.98  5112.1 1261.81
  5212.1 1282.61  5292.1 1292.39  5430.4 1298.19  5502.1 1305.28  5751.6 1317.93
#Mann= 6 ,-1 , 0
  4110.2     .16       0  4231.4      .1       0  4682.2     .16       0
  4989.1     .07       0  4995.1     .16       0  5430.4      .1       0
Bank Sta=4922.1,5022.1
XS Rating Curve= 0 ,0
Exp/Cntr=0.3,0.1

Type RM Length L Ch R = 1 ,68033   ,452,452,452
BEGIN DESCRIPTION:
FLAT CREEK 138.0
END DESCRIPTION:
XS GIS Cut Line= 4
      2954684.44     10042943.15      2955087.24     10042955.31
       2955503.9     10043125.45      2955933.95     10043063.02
#Sta/Elev= 30
  4414.3 1291.57  4448.3 1292.11  4468.4 1287.55  4498.4 1288.52  4528.4 1282.53
  4558.4 1281.62  4608.4 1273.32  4673.7 1257.04  4688.5 1253.24  4698.5 1245.85
  4710.3 1245.25  4748.5 1244.58  4788.5 1249.75  4872.6 1252.13  4902.7 1248.92
  4937.5 1237.98  4961.5  1234.2  4999.2  1225.1    5002  1224.6  5005.2  1225.1
  5033.6 1233.97    5039 1236.04  5045.4 1242.83  5056.2 1257.52    5063 1270.08
  5068.4 1271.91  5172.1 1276.62    5218 1280.93  5433.6 1289.97  5701.9 1294.97
#Mann= 6 ,-1 , 0
  4414.3     .16       0  4673.7      .1       0  4710.3     .16       0
  4999.2     .07       0  5005.2     .16       0  5172.1      .1       0
#XS Ineff= 2 , 0
          4871.7 1252.24
Permanent Ineff=
       T       T
Bank Sta=4961.5,5033.6
XS Rating Curve= 0 ,0
Exp/Cntr=0.3,0.1

Type RM Length L Ch R = 1 ,67581   ,688,688,688
BEGIN DESCRIPTION:
FLAT CREEK 137.0
END DESCRIPTION:
XS GIS Cut Line= 4
      2954371.93     10042927.51      2955017.79     10043338.99
      2955189.67     10043521.28      2955735.02     10043692.68
#Sta/Elev= 30
  4331.3 1302.51  4354.5 1300.58  4362.8 1291.11    4385  1287.9  4694.8 1287.12
  4739.6 1282.01  4797.2 1282.16  4875.9 1276.64    4920 1272.91  4933.5 1262.57
  4936.4 1257.57  4942.8 1246.53  4955.6 1230.97  4963.9 1226.68  4979.2 1221.53
  4997.3 1220.29  5000.1 1219.79  5003.3 1220.29  5020.7 1225.22  5027.4 1227.43
  5122.1 1233.85  5178.7 1243.89  5291.8 1246.42  5410.2 1249.56  5482.7 1267.05
  5506.7 1270.43    5598 1273.87  5692.3 1281.85  5854.9 1290.53  5919.3 1293.39
#Mann= 8 ,-1 , 0
  4331.3      .1       0  4936.4     .16       0  4997.3     .07       0
  5003.3     .16       0  5020.7      .1       0  5291.8     .16       0
  5506.7      .1       0  5854.9     .16       0
Bank Sta=4963.9,5027.4
XS Rating Curve= 0 ,0
Exp/Cntr=0.3,0.1

Type RM Length L Ch R = 1 ,66893   ,450,450,450
BEGIN DESCRIPTION:
FLAT CREEK 136.0
END DESCRIPTION:
XS GIS Cut Line= 3
      2954715.72     10043474.43      2954996.96     10044010.86
       2955584.5     10043969.27
#Sta/Elev= 30
  4518.5 1272.74  4601.1 1272.83  4623.2 1270.69  4661.6 1260.87  4667.3 1260.66
  4683.7 1254.42  4705.7 1248.82  4749.9 1241.18  4755.5 1238.84  4771.9 1237.78
  4788.3 1233.61    4800 1228.31  4822.6  1224.2  4970.5 1217.97  4986.9 1213.52
    5003 1211.43  5003.5 1211.43 5018.86 1218.31  5025.3 1221.46  5037.1 1222.31
    5226 1217.62  5293.5 1216.79  5326.2 1218.24  5346.3 1223.76  5386.4 1244.42
  5416.4 1265.69  5426.5  1271.1    5509 1275.31  5566.8 1280.66  5713.2 1285.74
#Mann= 5 ,-1 , 0
  4518.5      .1       0  4970.5     .05       0  4970.5     .07       0
  5003.5     .16       0    5509      .1       0
#XS Ineff= 2 , 0
                         5037.95         1222.32
Permanent Ineff=
       T       T
Bank Sta=4970.5,5018.86
XS Rating Curve= 0 ,0
Exp/Cntr=0.3,0.1

Type RM Length L Ch R = 1 ,66443   ,772,772,772
BEGIN DESCRIPTION:
FLAT CREEK 135.0
END DESCRIPTION:
XS GIS Cut Line= 4
      2954470.92     10044635.86      2954825.08     10044338.99
      2955179.25     10044135.86      2955637.54     10044016.08
#Sta/Elev= 30
  4384.3 1283.52  4426.6 1278.53  4440.9 1274.58    4519 1259.56  4581.4  1251.5
  4596.3 1248.21  4693.5 1243.47    4774 1241.15  4824.7 1235.53  4849.8 1235.29
  4947.9 1233.94  4963.7 1230.29  4985.3 1213.81  4997.2 1207.44  4999.9 1206.94
  5003.2 1207.44  5028.4 1214.18    5109 1216.44  5232.2 1214.69  5295.2 1217.11
  5315.9 1222.06  5321.8 1228.06  5326.9 1227.43    5357  1248.2  5362.2 1245.27
  5367.6 1259.56  5377.9 1272.91  5482.7 1280.85  5646.7 1285.22  5728.4  1290.8
#Mann= 10 ,-1 , 0
  4384.3     .16       0  4440.9      .1       0  4581.4     .16       0
  4596.3      .1       0  4693.5     .05       0  4849.8      .1       0
  4997.2     .07       0  5003.2      .1       0  5232.2     .16       0
  5482.7      .1       0
#XS Ineff= 2 , 0
                         5108.18         1216.65
Permanent Ineff=
       T       T
Bank Sta=4985.3,5028.4
XS Rating Curve= 0 ,0
Exp/Cntr=0.3,0.1

Type RM Length L Ch R = 1 ,65671   ,577,577,577
BEGIN DESCRIPTION:
FLAT CREEK 133.0
END DESCRIPTION:
XS GIS Cut Line= 4
      2954554.28     10044854.61        2955148.     10044828.57
      2955293.83     10044578.57      2955746.96      10044161.9
#Sta/Elev= 30
  4283.9 1284.08  4318.1 1281.84  4348.1 1278.08  4358.2    1274  4430.8 1265.87
  4508.3 1251.36  4563.5 1245.41  4625.1 1240.17  4738.5 1233.26  4910.8 1230.08
  4941.7 1226.48  4958.7 1221.18  4969.5 1217.83  4976.4 1211.55    4991 1201.27
  4996.6 1201.11  4999.3 1200.61  5002.6 1201.11  5012.5 1205.53  5071.2 1212.25
  5195.6 1214.58  5323.2 1228.11    5351 1233.96  5415.1 1267.73  5436.1 1273.43
    5507 1274.26  5601.1  1282.9  5662.9 1285.37  5698.1 1290.25  5783.2 1292.17
#Mann= 8 ,-1 , 0
  4283.9      .1       0  4430.8     .16       0  4563.5      .1       0
  4625.1     .05       0  4958.7     .16       0  4996.6     .07       0
  5002.6     .16       0  5601.1      .1       0
Bank Sta=4976.4,5071.2
XS Rating Curve= 0 ,0
Exp/Cntr=0.3,0.1

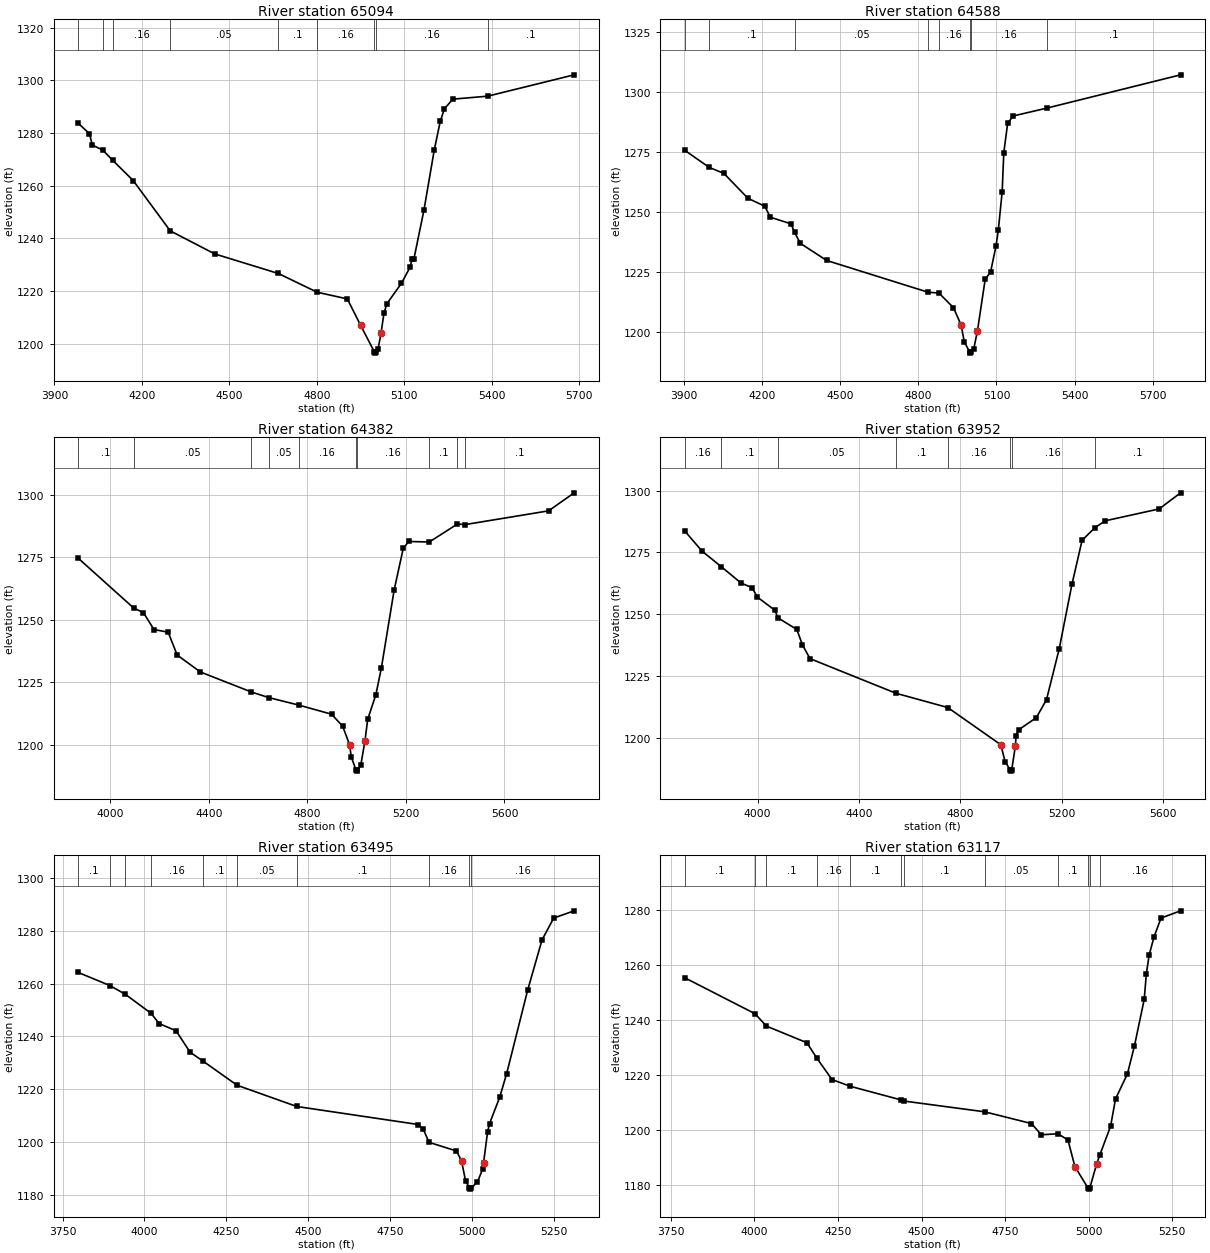
Type RM Length L Ch R = 1 ,65094   ,506,506,506
BEGIN DESCRIPTION:
FLAT CREEK 132.0
END DESCRIPTION:
XS GIS Cut Line= 3
      2954580.25     10044917.11      2955726.12      10044906.7
      2956080.32     10044479.57
#Sta/Elev= 30
  3982.2 1283.71  4020.4 1279.78  4030.4 1275.45  4065.7 1273.57  4100.1 1269.68
  4170.4 1261.98  4297.5 1242.87  4450.4 1234.11  4668.2 1226.69  4801.5 1219.57
  4904.8 1217.03  4950.5 1207.02  4997.5 1196.94  5000.2 1196.44  5003.5 1196.94
  5010.5 1198.05  5020.5 1204.01  5030.5 1211.52  5040.5 1215.19  5090.5 1222.95
  5120.5 1229.13  5126.8 1232.23  5133.3 1232.23  5167.7 1250.73  5202.9 1273.45
  5223.7 1284.49    5238 1289.24  5266.7  1292.9  5386.3 1294.03    5683 1302.14
#Mann= 9 ,-1 , 0
  3982.2     .16       0  4065.7      .1       0  4100.1     .16       0
  4297.5     .05       0  4668.2      .1       0  4801.5     .16       0
  4997.5     .07       0  5003.5     .16       0  5386.3      .1       0
Bank Sta=4950.5,5020.5
XS Rating Curve= 0 ,0
Exp/Cntr=0.3,0.1

Type RM Length L Ch R = 1 ,64588   ,206,206,206
BEGIN DESCRIPTION:
FLAT CREEK 131.0
END DESCRIPTION:
XS GIS Cut Line= 4
      2955064.68     10045828.56      2955799.04     10045302.53
      2956033.42      10044969.2      2956236.55     10044411.88
#Sta/Elev= 30
  3903.1 1275.73  3997.3 1268.61  4053.3 1266.14  4145.4  1255.8  4210.5 1252.47
  4231.4 1247.92  4311.2 1245.15  4324.9 1241.56  4346.9 1237.04  4447.6 1229.94
  4837.1 1216.72    4879 1216.38  4934.6 1210.31  4963.9 1203.14  4976.4  1196.1
  4996.9 1191.88  4999.7 1191.38  5002.9 1191.88  5012.8 1193.19  5026.9 1200.63
  5056.5 1222.01  5077.5 1225.21  5098.4 1236.11  5107.1 1242.59  5121.9 1258.61
    5128 1274.71  5142.8 1286.92  5163.7 1290.02  5293.6 1293.31  5807.1 1307.15
#Mann= 8 ,-1 , 0
  3903.1     .16       0  3997.3      .1       0  4324.9     .05       0
  4837.1      .1       0    4879     .16       0  4996.9     .07       0
  5002.9     .16       0  5293.6      .1       0
Bank Sta=4963.9,5026.9
XS Rating Curve= 0 ,0
Exp/Cntr=0.3,0.1

Type RM Length L Ch R = 1 ,64382   ,430,430,430
BEGIN DESCRIPTION:
FLAT CREEK 130.0
END DESCRIPTION:
XS GIS Cut Line= 3
      2955184.47     10045922.31      2956007.37      10045406.7
      2956460.51     10044469.16
#Sta/Elev= 30
  3870.4 1274.64  4094.8 1254.74  4134.7 1252.86  4177.3 1246.12    4235 1245.03
  4271.5  1235.9  4365.8  1229.1  4572.2 1221.11  4643.3 1218.84  4764.5 1215.86
  4898.1 1212.19  4943.3 1207.36  4971.5 1199.92  4978.1 1195.06  4997.3 1189.89
    5000 1189.39  5003.3 1189.89  5016.7  1191.7  5033.6 1201.41  5044.8 1210.12
    5078 1219.99  5100.2 1230.64  5152.2 1261.95  5189.1 1278.61  5211.3 1281.38
  5294.6 1281.17  5408.7 1288.35  5441.5 1288.17    5779 1293.65  5882.8 1300.87
#Mann= 10 ,-1 , 0
  3870.4      .1       0  4094.8     .05       0  4572.2      .1       0
  4643.3     .05       0  4764.5     .16       0  4997.3     .07       0
  5003.3     .16       0  5294.6      .1       0  5408.7     .16       0
  5441.5      .1       0
Bank Sta=4971.5,5033.6
XS Rating Curve= 0 ,0
Exp/Cntr=0.3,0.1

Type RM Length L Ch R = 1 ,63952   ,457,457,457
BEGIN DESCRIPTION:
FLAT CREEK 129.0
END DESCRIPTION:
XS GIS Cut Line= 4
      2955189.67     10046068.15      2956028.21     10045588.99
      2956642.79     10045547.32      2956912.62     10045287.87
#Sta/Elev= 30
  3712.7 1283.64  3780.4 1275.56  3856.5 1269.25  3934.6 1262.64  3977.8 1260.77
  3999.4 1256.93  4068.4 1251.63  4079.9 1248.58  4154.8 1243.88  4176.4 1237.74
  4206.6 1232.11  4546.2 1218.11    4750 1212.37  4959.4 1197.33  4976.2 1190.56
  4996.5 1187.18  4999.2 1186.68  5002.5 1187.18 5017.05 1196.97  5019.5 1201.01
  5029.5 1203.35  5099.7 1208.29  5139.8 1215.58  5189.9 1236.12    5240 1262.09
  5280.1 1279.91  5330.9 1285.02  5371.7 1287.78  5583.9 1292.56  5668.8 1299.07
#Mann= 8 ,-1 , 0
  3712.7     .16       0  3856.5      .1       0  4079.9     .05       0
  4546.2      .1       0    4750     .16       0  4996.5     .07       0
  5002.5     .16       0  5330.9      .1       0
Bank Sta=4959.4,5017.05
XS Rating Curve= 0 ,0
Exp/Cntr=0.3,0.1

Type RM Length L Ch R = 1 ,63495   ,378,378,378
BEGIN DESCRIPTION:
FLAT CREEK 128.0
END DESCRIPTION:
XS GIS Cut Line= 3
      2955564.68     10046354.61      2956533.42      10046031.7
      2956788.62     10045609.82
#Sta/Elev= 30
  3798.3 1264.19  3894.3 1259.27  3941.3 1255.99  4020.7 1248.73  4044.7  1244.9
  4096.8 1242.14  4139.6 1234.04  4177.8 1230.79  4283.3 1221.54  4465.4 1213.52
  4836.7  1206.7  4852.1 1204.82  4869.3 1199.97  4953.1 1196.69  4968.6 1192.98
  4980.7 1185.44  4992.8 1182.77  4995.6 1182.27  4998.8 1182.77  5017.2 1185.01
  5032.7  1189.7 5035.91 1192.32  5048.2 1203.97    5054 1207.02    5085 1216.97
  5106.4 1225.97  5170.4 1257.48  5214.4 1276.51    5250 1284.77  5312.5 1287.51
#Mann= 10 ,-1 , 0
  3798.3      .1       0  3894.3     .16       0  3941.3      .1       0
  4020.7     .16       0  4177.8      .1       0  4283.3     .05       0
  4465.4      .1       0  4869.3     .16       0  4992.8     .07       0
  4998.8     .16       0
Bank Sta=4968.6,5035.91
XS Rating Curve= 0 ,0
Exp/Cntr=0.3,0.1

Type RM Length L Ch R = 1 ,63117   ,488,488,488
BEGIN DESCRIPTION:
FLAT CREEK 127.0
END DESCRIPTION:
XS GIS Cut Line= 3
      2955726.12     10046401.49      2956736.54     10046255.65
      2957111.57      10045984.8
#Sta/Elev= 30
  3791.6 1255.39  4001.9 1242.32  4035.4 1237.85  4156.8 1231.79  4186.9 1226.14
  4232.2 1218.38  4287.2 1215.93  4438.1 1211.01  4448.8 1210.56  4688.4 1206.68
  4828.8  1202.4  4858.3 1198.32  4908.2 1198.69    4938 1196.42  4958.8 1186.74
  4997.6 1179.06  5000.3 1178.56  5003.6 1179.06  5023.8 1187.69  5033.3 1190.96
  5065.6 1201.46  5080.3 1211.35  5115.9 1220.45  5136.8 1230.55  5166.2 1247.57
  5172.6 1256.91  5180.9 1263.64  5195.6  1270.3  5216.5 1277.11  5275.1 1279.74
#Mann= 12 ,-1 , 0
  3791.6      .1       0  4001.9     .16       0  4035.4      .1       0
  4186.9     .16       0  4287.2      .1       0  4438.1     .16       0
  4448.8      .1       0  4688.4     .05       0  4908.2      .1       0
  4997.6     .07       0  5003.6      .1       0  5033.3     .16       0
Bank Sta=4958.8,5023.8
XS Rating Curve= 0 ,0
Exp/Cntr=0.3,0.1

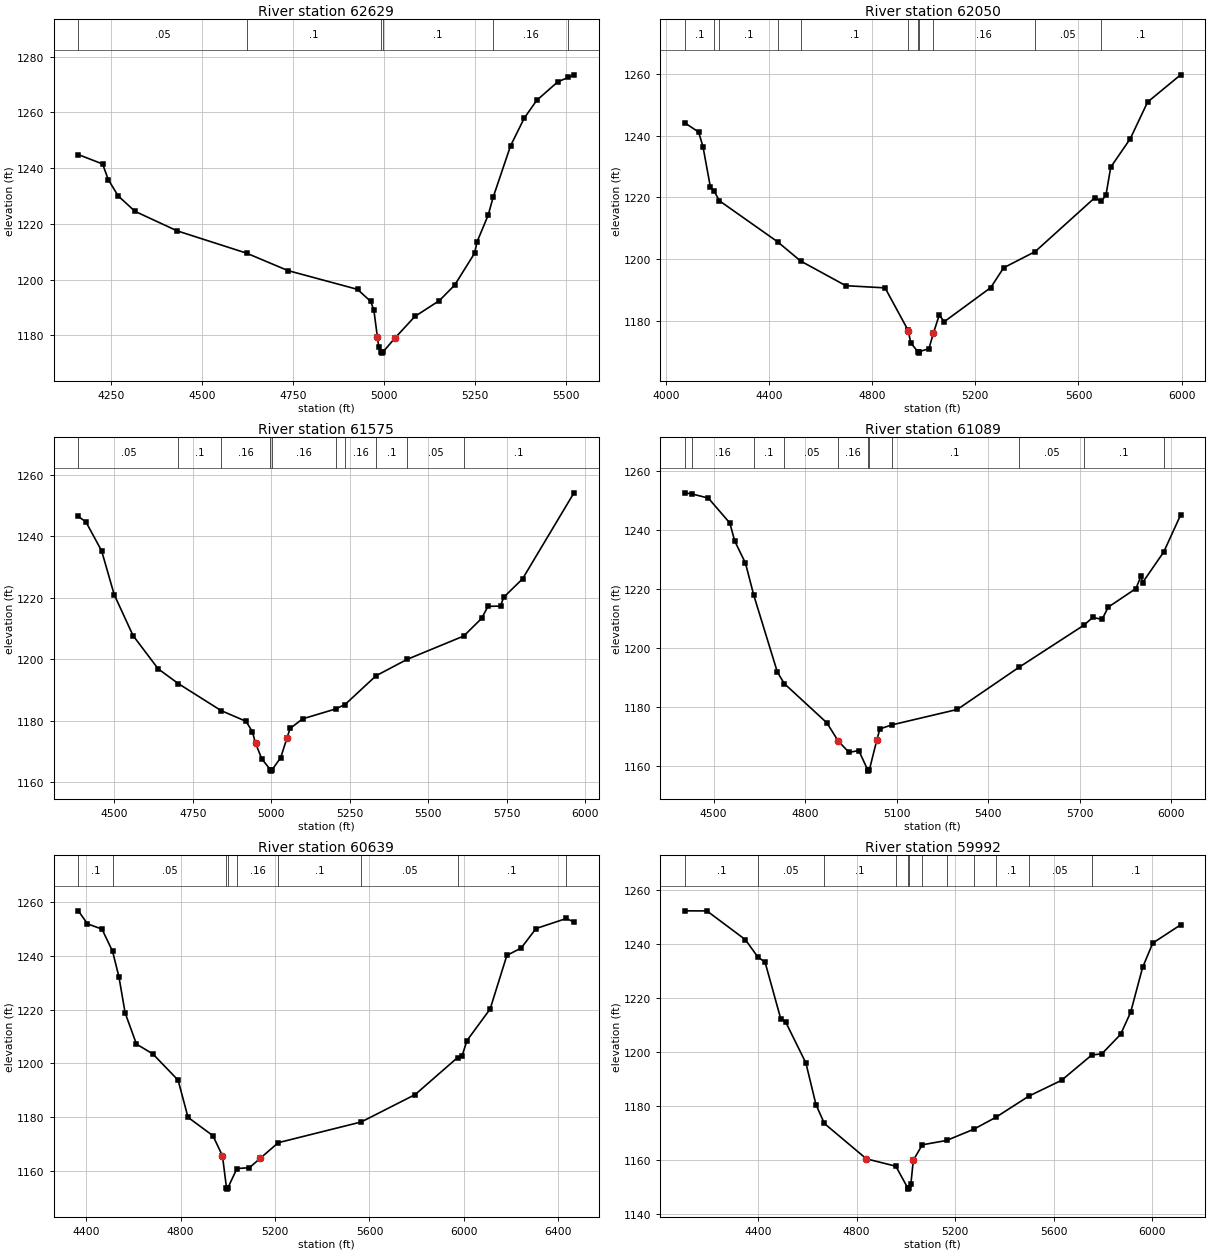
Type RM Length L Ch R = 1 ,62629   ,579,579,579
BEGIN DESCRIPTION:
FLAT CREEK 126.0
END DESCRIPTION:
XS GIS Cut Line= 4
      2956455.28     10047062.95      2957054.25     10046693.15
      2957184.46     10046427.53      2957262.57      10046073.4
#Sta/Elev= 30
    4159 1244.86  4225.8 1241.48  4241.2  1235.9  4268.5 1230.04  4314.5 1224.52
  4430.4 1217.51  4621.4  1209.5  4735.4 1203.24  4926.4 1196.51  4962.5  1192.2
  4971.4 1189.06 4980.91 1179.52  4984.8 1175.97  4990.9 1174.14  4993.7 1173.64
  4996.9 1174.14  5029.3 1179.04  5083.9 1186.78  5151.4 1192.48  5193.4 1198.03
  5248.3 1209.49  5254.8 1213.51  5285.5 1223.12  5299.2 1229.54    5347 1247.98
  5384.5 1257.89  5418.7 1264.27    5477 1270.98  5505.6 1272.53  5521.4 1273.47
#Mann= 6 ,-1 , 0
    4159     .05       0  4621.4      .1       0  4990.9     .07       0
  4996.9      .1       0  5299.2     .16       0  5505.6      .1       0
Bank Sta=4980.91,5029.3
XS Rating Curve= 0 ,0
Exp/Cntr=0.3,0.1

Type RM Length L Ch R = 1 ,62050   ,475,475,475
BEGIN DESCRIPTION:
FLAT CREEK 125.0
END DESCRIPTION:
XS GIS Cut Line= 4
      2956575.08     10047151.49        2957148.     10046875.45
      2957908.42     10046870.24      2958423.77     10046979.55
#Sta/Elev= 30
  4073.3 1244.22  4126.4 1241.26  4143.4 1236.41  4171.6 1223.52  4186.6 1222.08
  4206.2 1218.97  4432.8 1205.59    4522 1199.35  4697.4 1191.33  4849.7 1190.62
  4938.7 1176.88  4939.7 1176.54  4949.7 1172.68  4976.7 1169.91  4979.5 1169.41
  4982.7 1169.91  5019.7 1170.84  5037.4 1175.95  5059.7 1181.74  5079.7 1179.65
  5259.7 1190.71  5309.7 1197.15  5432.1 1202.41    5664 1219.96  5687.8 1218.72
  5706.7 1220.73  5725.3 1229.86  5800.9 1239.08  5868.4 1251.03  5996.5 1259.87
#Mann= 11 ,-1 , 0
  4073.3      .1       0  4186.6     .05       0  4206.2      .1       0
  4432.8     .05       0    4522      .1       0  4938.7     .05       0
  4976.7    .035       0  4982.7     .05       0  5037.4     .16       0
  5432.1     .05       0  5687.8      .1       0
Bank Sta=4939.7,5037.4
XS Rating Curve= 0 ,0
Exp/Cntr=0.3,0.1

Type RM Length L Ch R = 1 ,61575   ,486,486,486
BEGIN DESCRIPTION:
FLAT CREEK 124.0
END DESCRIPTION:
XS GIS Cut Line= 2
      2956804.29      10047344.2      2958382.38      10047349.4
#Sta/Elev= 30
  4385.7 1246.52  4409.9 1244.75  4459.9 1235.31  4499.9 1221.06  4559.9 1207.71
  4639.9 1196.86  4704.2 1192.04  4840.1 1183.26  4919.9 1179.74  4939.9 1176.34
  4949.9  1172.6  4969.9  1167.5  4996.9 1164.02  4999.6 1163.52  5002.9 1164.02
  5029.9 1167.87  5049.9 1174.29  5059.9 1177.42  5099.9 1180.56  5204.8 1183.78
  5234.7 1185.21  5333.4 1194.59    5432 1199.92  5612.9 1207.56  5669.9 1213.32
  5689.9 1217.23  5729.9 1217.31  5739.9 1220.18  5799.9 1226.17  5963.8 1254.23
#Mann= 10 ,-1 , 0
  4385.7     .05       0  4704.2      .1       0  4840.1     .16       0
  4996.9     .07       0  5002.9     .16       0  5204.8      .1       0
  5234.7     .16       0  5333.4      .1       0    5432     .05       0
  5612.9      .1       0
Bank Sta=4949.9,5049.9
XS Rating Curve= 0 ,0
Exp/Cntr=0.3,0.1

Type RM Length L Ch R = 1 ,61089   ,450,450,450
BEGIN DESCRIPTION:
FLAT CREEK 123.0
END DESCRIPTION:
XS GIS Cut Line= 4
      2956825.07     10047682.73      2957309.46     10047792.11
      2957580.29     10047885.86      2958413.57     10047771.29
#Sta/Elev= 30
  4406.2 1252.61  4429.8 1252.21  4482.7 1250.83  4553.2 1242.36  4569.1 1236.29
  4604.5 1228.74  4631.6 1217.89    4709  1191.8  4731.8 1187.88    4871 1174.61
  4909.2 1168.29  4944.1 1164.56  4975.8  1165.2  5004.6 1158.71  5007.3 1158.21
  5010.6 1158.71 5035.11 1168.84  5044.9 1172.53  5083.6 1173.88  5298.6 1179.13
  5500.2 1193.39  5713.5 1207.71  5742.7 1210.36    5773 1209.67  5793.2 1213.83
    5884 1220.14  5900.8  1224.4  5905.8 1222.17  5975.2 1232.56  6030.5  1245.1
#Mann= 11 ,-1 , 0
  4406.2      .1       0  4429.8     .16       0  4631.6      .1       0
  4731.8     .05       0  4909.2     .16       0  5004.6     .07       0
  5010.6     .16       0  5083.6      .1       0  5500.2     .05       0
  5713.5      .1       0  5975.2     .16       0
Bank Sta=4909.2,5035.11
XS Rating Curve= 0 ,0
Exp/Cntr=0.3,0.1

Type RM Length L Ch R = 1 ,60639   ,647,647,647
BEGIN DESCRIPTION:
FLAT CREEK 122.0
END DESCRIPTION:
XS GIS Cut Line= 4
      2956590.72      10048094.2      2957043.83     10048198.36
      2957705.29     10048276.49      2958632.38     10047995.24
#Sta/Elev= 30
  4366.5 1256.79  4405.2 1251.94  4466.8 1249.97  4511.7 1241.67  4538.6 1232.16
  4564.8 1218.76  4612.7 1207.14  4682.3 1203.46  4789.2 1193.69  4831.2 1179.85
  4936.8 1172.99  4977.1 1165.49  4994.2 1153.59    4997 1153.09  5000.2 1153.59
  5038.5 1160.75  5091.6  1161.1  5138.2 1164.66  5213.6  1170.4  5565.1 1178.12
  5793.4 1188.32  5973.2 1202.12    5992 1202.66  6012.9 1208.44    6111 1220.19
    6182 1240.18  6242.6 1242.93  6305.5 1250.18    6434 1253.94  6466.3 1252.59
#Mann= 9 ,-1 , 0
  4366.5      .1       0  4511.7     .05       0  4994.2    .035       0
  5000.2     .05       0  5038.5     .16       0  5213.6      .1       0
  5565.1     .05       0  5973.2      .1       0    6434     .16       0
Bank Sta=4977.1,5138.2
XS Rating Curve= 0 ,0
Exp/Cntr=0.3,0.1

Type RM Length L Ch R = 1 ,59992   ,343,343,343
BEGIN DESCRIPTION:
FLAT CREEK 121.0
END DESCRIPTION:
XS GIS Cut Line= 4
      2956549.08     10048599.41        2957273.     10048755.65
      2957746.96     10048755.65      2958517.81     10048557.73
#Sta/Elev= 30
  4103.9 1252.11  4192.9 1252.07  4348.8 1241.44  4398.5 1235.14    4429 1233.03
    4492 1212.25  4512.5 1210.92  4594.3 1195.79  4635.2 1180.38  4669.3 1173.39
  4839.6 1160.31  4959.1 1157.57    5007 1149.59  5009.7 1149.09    5013 1149.59
    5020 1150.81    5030 1159.77  5066.3 1165.49    5165 1167.11    5275 1171.25
  5364.2 1175.64  5498.4 1183.51  5631.3 1189.37  5753.8 1198.74  5794.9 1199.18
  5870.7 1206.37  5911.4 1214.52  5960.1 1231.16  6001.4 1240.19  6114.3 1246.92
#Mann= 12 ,-1 , 0
  4103.9      .1       0  4398.5     .05       0  4669.3      .1       0
  4959.1     .16       0    5007     .07       0    5013     .16       0
  5066.3     .05       0    5165      .1       0    5275     .05       0
  5364.2      .1       0  5498.4     .05       0  5753.8      .1       0
Bank Sta=4839.6,5030
XS Rating Curve= 0 ,0
Exp/Cntr=0.3,0.1