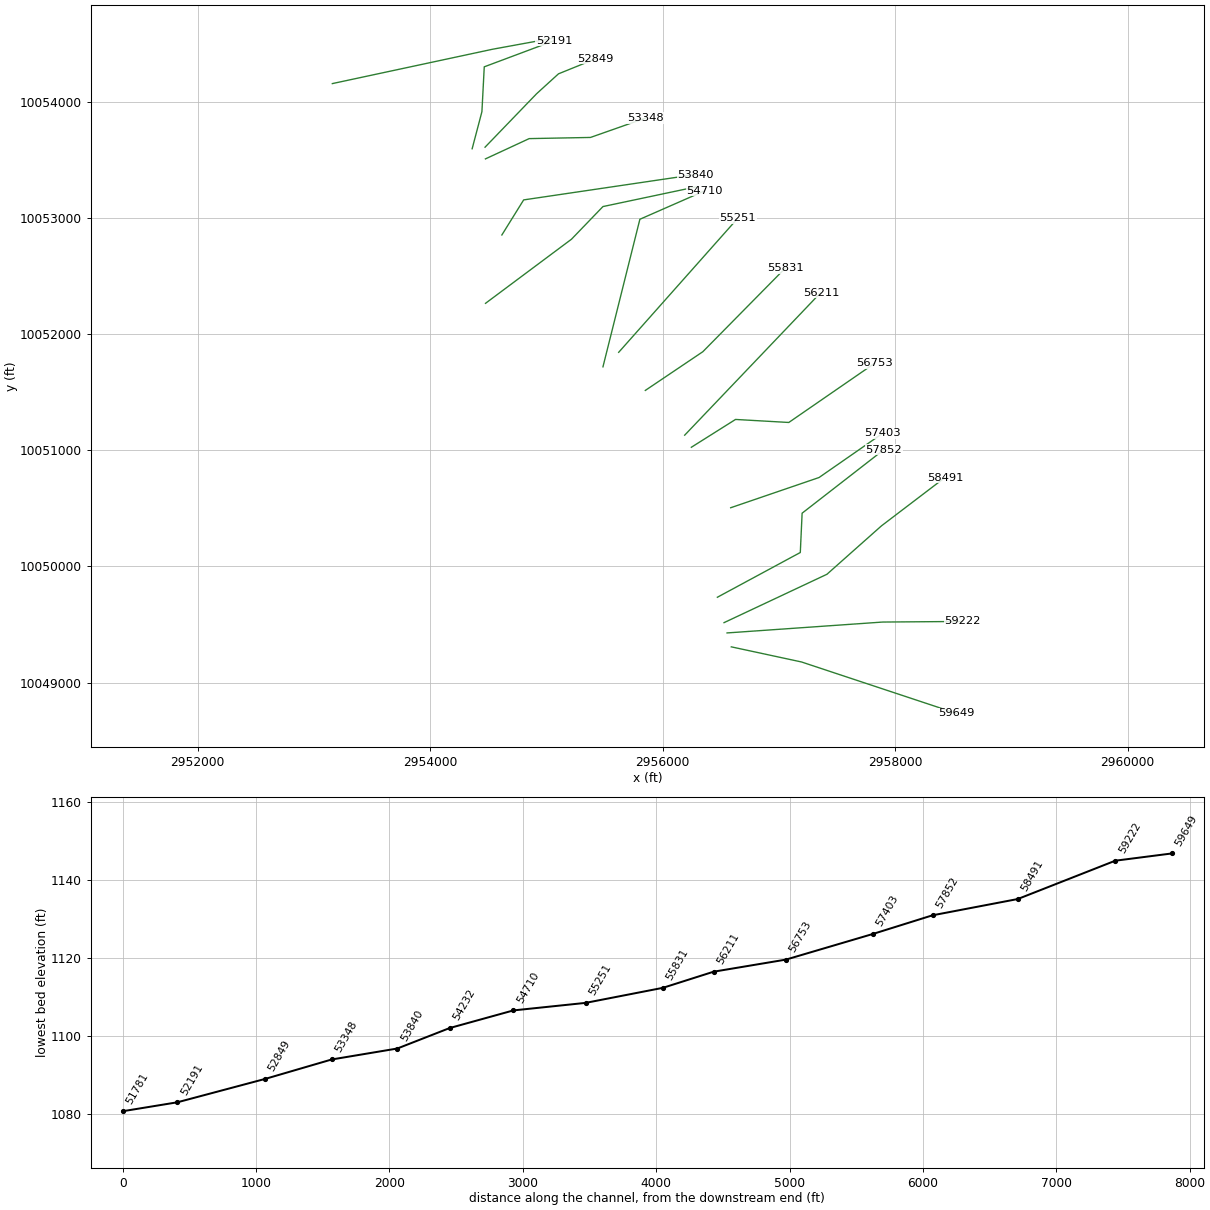
HEC-RAS study FLAT CREEK.prj: FLAT CREEK Base Level Engineering

--- FLAT CREEK.g01 (geometry) --- (continued)

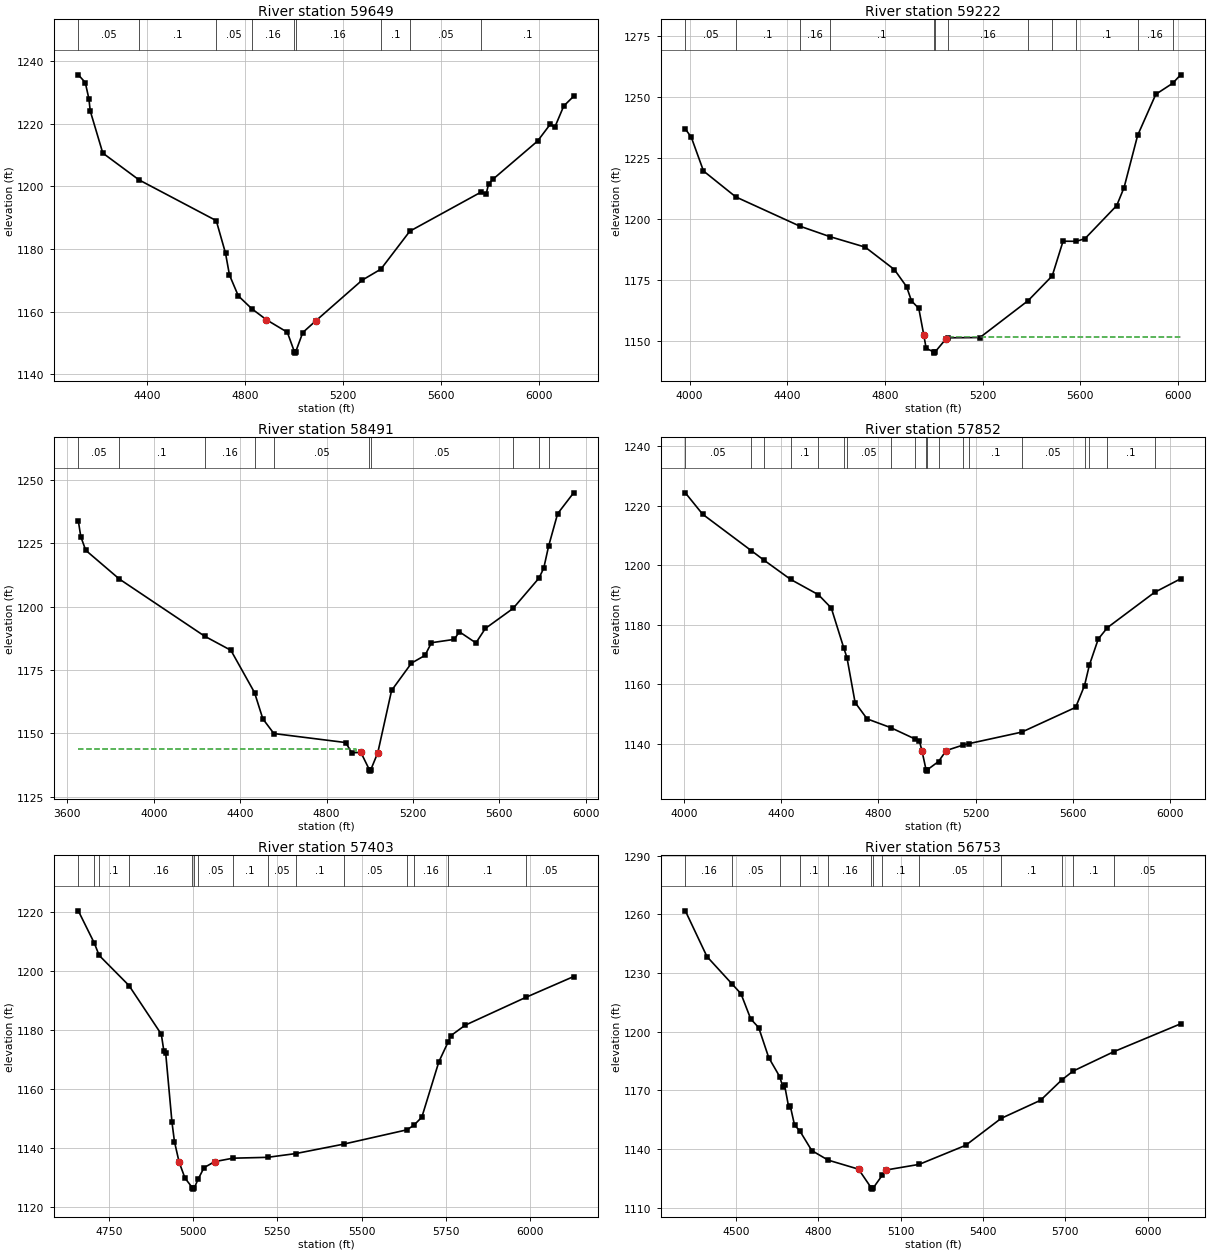
Type RM Length L Ch R = 1 ,59649   ,427,427,427
BEGIN DESCRIPTION:
FLAT CREEK 120.0
END DESCRIPTION:
XS GIS Cut Line= 3
      2956590.75     10049307.73      2957194.87     10049177.53
       2958528.2     10048734.82
#Sta/Elev= 30
  4118.2 1235.61  4146.6 1233.16  4161.4 1227.98    4167 1224.07  4218.2 1210.63
  4366.2 1202.07  4681.6 1189.06  4719.4 1178.67  4735.5 1171.72  4771.6 1165.05
  4826.7 1160.94  4886.6 1157.42  4971.8 1153.44  5000.4 1147.27  5003.2 1146.77
  5006.4 1147.27    5035 1153.35  5087.7 1157.05  5277.4 1170.06  5353.9 1173.58
  5472.2  1185.7    5763 1198.17    5784 1197.62  5793.7 1200.72  5810.4  1202.2
  5993.9 1214.47  6046.5 1219.92  6063.8  1218.8  6100.7 1225.65  6141.1 1228.76
#Mann= 9 ,-1 , 0
  4118.2     .05       0  4366.2      .1       0  4681.6     .05       0
  4826.7     .16       0  5000.4     .07       0  5006.4     .16       0
  5353.9      .1       0  5472.2     .05       0    5763      .1       0
Bank Sta=4886.6,5087.7
XS Rating Curve= 0 ,0
Exp/Cntr=0.3,0.1

Type RM Length L Ch R = 1 ,59222   ,731,731,731
BEGIN DESCRIPTION:
FLAT CREEK 119.0
END DESCRIPTION:
XS GIS Cut Line= 3
      2956554.27     10049427.53      2957892.79     10049521.28
      2958580.27     10049526.49
#Sta/Elev= 30
  3982.4 1236.73  4006.7 1233.39  4056.8 1219.53  4189.1 1208.91  4451.2 1196.94
  4573.8 1192.66  4719.3 1188.33  4838.7 1179.15  4888.8 1172.14  4908.9 1166.31
  4938.9 1163.21    4959 1152.52    4969 1146.87  4999.8  1145.4  5002.5  1144.9
  5005.8  1145.4  5049.2 1150.61    5060 1151.18  5189.5  1151.3    5387 1166.42
  5485.6 1176.56  5529.9 1190.76  5584.2 1190.71  5619.9 1191.83  5749.9 1205.38
  5779.9 1212.76  5835.5 1234.12  5909.9 1250.96  5978.8 1255.45  6011.7 1258.93
#Mann= 12 ,-1 , 0
  3982.4     .05       0  4189.1      .1       0  4451.2     .16       0
  4573.8      .1       0  4999.8     .07       0  5005.8      .1       0
    5060     .16       0    5387     .05       0  5485.6     .08       0
  5584.2      .1       0  5835.5     .16       0  5978.8     .05       0
#XS Ineff= 2 , 0
                         5061.36         1151.41
Permanent Ineff=
       T       T
Bank Sta=4959,5049.2
XS Rating Curve= 0 ,0
Exp/Cntr=0.3,0.1

Type RM Length L Ch R = 1 ,58491   ,639,639,639
BEGIN DESCRIPTION:
FLAT CREEK 118.0
END DESCRIPTION:
XS GIS Cut Line= 4
      2956528.22     10049516.08      2957413.62     10049932.74
      2957882.37      10050349.4      2958429.23     10050766.05
#Sta/Elev= 30
  3650.8 1233.94  3662.3 1227.67  3685.1 1222.28  3840.7 1210.93  4235.5 1188.37
  4357.2 1182.79  4466.7 1166.09  4505.1 1155.73  4556.2 1149.92  4888.8 1146.36
  4916.8 1142.33    4959 1142.46  4998.7 1135.58  5001.4 1135.08  5004.7 1135.58
  5037.2 1142.32  5101.2 1166.93  5193.2 1177.72    5256 1180.78  5285.7 1185.78
  5391.8  1187.1  5414.6 1190.12  5491.6  1185.7  5535.2  1191.4  5663.3 1199.29
  5783.4 1211.27  5805.5 1215.18  5827.9 1223.82  5869.9 1236.72    5944 1244.96
#Mann= 10 ,-1 , 0
  3650.8     .05       0  3840.7      .1       0  4235.5     .16       0
  4466.7      .1       0  4556.2     .05       0  4998.7    .035       0
  5004.7     .05       0  5663.3      .1       0  5783.4     .05       0
  5827.9      .1       0
#XS Ineff= 2 , 0
          4937.5 1143.83
Permanent Ineff=
       T       T
Bank Sta=4959,5037.2
XS Rating Curve= 0 ,0
Exp/Cntr=0.3,0.1

Type RM Length L Ch R = 1 ,57852   ,449,449,449
BEGIN DESCRIPTION:
FLAT CREEK 117.0
END DESCRIPTION:
XS GIS Cut Line= 4
      2956470.89     10049734.81      2957184.46     10050120.24
      2957200.08     10050458.78      2957903.23     10051005.67
#Sta/Elev= 30
  4004.3 1224.35  4075.5 1217.17  4275.7 1204.96  4328.4 1201.74    4438 1195.29
  4552.8 1190.13  4605.7 1185.67  4657.2 1172.23  4670.3    1169  4703.7 1153.95
  4753.2 1148.45  4850.3 1145.52  4948.9 1141.77    4969 1140.91    4979 1137.79
    4996 1131.41  4998.7 1130.91    5002 1131.41  5047.6 1134.14  5079.1 1137.82
  5146.3 1139.61  5173.2 1140.15  5390.3 1144.01  5612.4 1152.32  5648.9 1159.63
  5668.9  1166.5  5705.6 1175.27  5743.4  1179.1  5937.3 1190.92    6045 1195.49
#Mann= 19 ,-1 , 0
  4004.3     .05       0  4275.7      .1       0  4328.4     .16       0
    4438      .1       0  4552.8     .16       0  4657.2      .1       0
  4670.3     .05       0  4850.3      .1       0  4948.9     .05       0
    4996    .035       0    5002     .05       0  5047.6      .1       0
  5146.3     .05       0  5173.2      .1       0  5390.3     .05       0
  5648.9      .1       0  5668.9     .16       0  5743.4      .1       0
  5937.3     .05       0
Bank Sta=4979,5079.1
XS Rating Curve= 0 ,0
Exp/Cntr=0.3,0.1

Type RM Length L Ch R = 1 ,57403   ,650,650,650
BEGIN DESCRIPTION:
FLAT CREEK 115.0
END DESCRIPTION:
XS GIS Cut Line= 3
      2956585.46     10050505.64      2957345.92     10050766.07
      2957892.82      10051146.3
#Sta/Elev= 30
  4659.5 1220.56  4707.1 1209.58  4721.3 1205.44  4809.9 1195.21  4905.8 1178.69
  4913.5 1172.89  4918.8 1172.27  4937.5  1148.8  4944.8 1142.25  4958.6 1135.29
  4976.1 1129.84  4997.9 1126.61  5000.7 1126.11  5003.9 1126.61  5015.5 1129.58
  5032.6  1133.4  5064.3 1135.44  5118.3 1136.61  5221.1  1136.9  5304.4 1138.17
  5446.5 1141.37  5634.8 1146.24  5655.1 1147.77  5678.9 1150.52  5729.5 1169.34
  5757.5 1176.17  5765.3 1178.21  5807.4 1181.73  5989.1 1191.27  6129.4 1198.25
#Mann= 15 ,-1 , 0
  4659.5     .16       0  4707.1     .05       0  4721.3      .1       0
  4809.9     .16       0  4997.9     .07       0  5003.9     .16       0
  5015.5     .05       0  5118.3      .1       0  5221.1     .05       0
  5304.4      .1       0  5446.5     .05       0  5634.8      .1       0
  5655.1     .16       0  5757.5      .1       0  5989.1     .05       0
Bank Sta=4958.6,5064.3
XS Rating Curve= 0 ,0
Exp/Cntr=0.3,0.1

Type RM Length L Ch R = 1 ,56753   ,542,542,542
BEGIN DESCRIPTION:
FLAT CREEK 114.0
END DESCRIPTION:
XS GIS Cut Line= 4
      2956246.96     10051026.49      2956627.17     10051266.07
       2957085.5     10051240.03      2957823.04     10051749.04
#Sta/Elev= 30
  4315.7 1261.81  4394.6 1238.41  4485.2 1224.53  4518.4 1219.45  4553.9 1206.56
    4583 1202.12  4619.5  1186.8  4659.3 1177.12  4671.2 1171.74  4677.1 1172.86
  4692.4  1161.4  4698.3 1161.92  4713.6 1152.27  4732.5 1149.38  4776.4 1139.26
  4835.7  1134.4  4946.7 1129.76  4993.8 1120.06  4996.5 1119.56  4999.8 1120.06
  5033.8 1126.78  5046.8 1129.33  5167.6 1132.21  5337.1 1141.95  5466.3 1155.72
  5609.9 1164.98    5687 1175.36  5728.4 1179.89  5877.8 1189.87  6120.3 1204.06
#Mann= 13 ,-1 , 0
  4315.7     .16       0  4485.2     .05       0  4659.3     .16       0
  4732.5      .1       0  4835.7     .16       0  4993.8     .07       0
  4999.8     .16       0  5033.8      .1       0  5167.6     .05       0
  5466.3      .1       0    5687     .16       0  5728.4      .1       0
  5877.8     .05       0
Bank Sta=4946.7,5046.8
XS Rating Curve= 0 ,0
Exp/Cntr=0.3,0.1

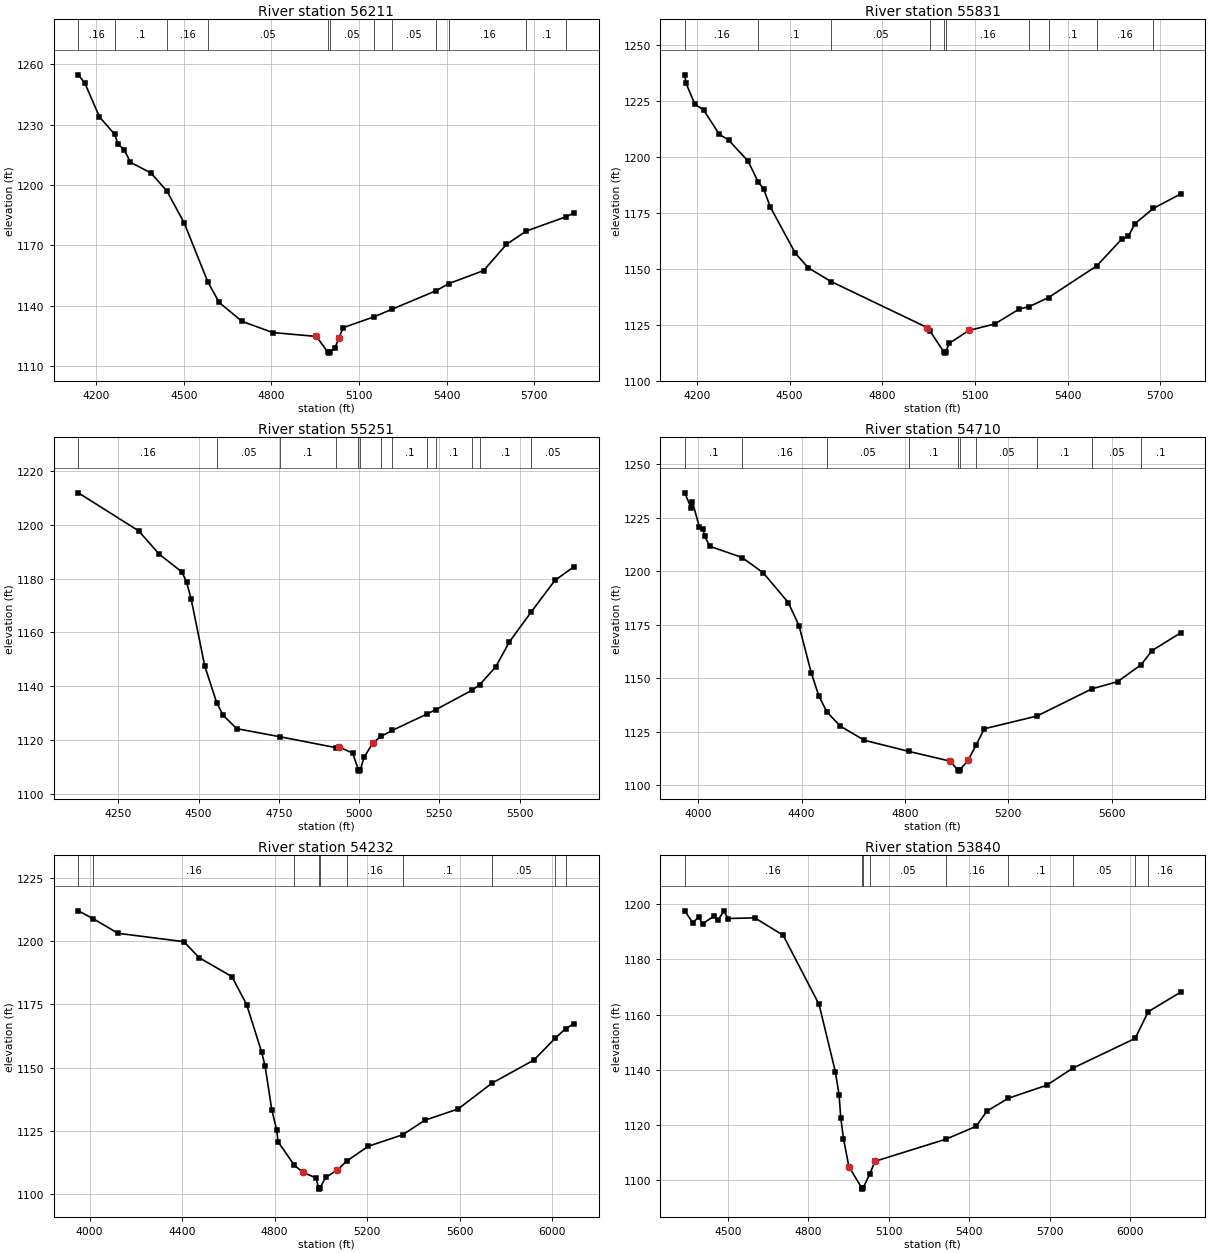
Type RM Length L Ch R = 1 ,56211   ,380,380,380
BEGIN DESCRIPTION:
FLAT CREEK 113.0
END DESCRIPTION:
XS GIS Cut Line= 2
      2956189.66     10051130.65        2957361.     10052359.26
#Sta/Elev= 30
  4139.3 1254.72  4161.8 1250.57  4211.5 1233.85  4263.8 1225.13    4275 1220.41
  4296.1 1217.55  4317.5 1211.31  4388.3 1205.91  4442.7 1196.92  4501.5 1181.22
  4582.7 1151.82  4621.6 1141.62  4699.3 1132.26  4805.6 1126.66  4954.1 1124.77
  4993.6 1116.96  4996.3 1116.46  4999.6 1116.96  5017.6 1119.02  5031.8 1124.07
  5045.9  1129.1  5152.3 1134.53  5212.9 1138.25  5364.8  1147.5  5407.8    1151
  5526.8 1157.46  5604.8 1170.46  5673.1 1177.12    5810 1184.26  5836.8 1186.15
#Mann= 12 ,-1 , 0
  4139.3     .16       0  4263.8      .1       0  4442.7     .16       0
  4582.7     .05       0  4993.6    .035       0  4999.6     .05       0
  5152.3      .1       0  5212.9     .05       0  5364.8      .1       0
  5407.8     .16       0  5673.1      .1       0    5810     .05       0
Bank Sta=4954.1,5031.8
XS Rating Curve= 0 ,0
Exp/Cntr=0.3,0.1

Type RM Length L Ch R = 1 ,55831   ,580,580,580
BEGIN DESCRIPTION:
FLAT CREEK 112.0
END DESCRIPTION:
XS GIS Cut Line= 3
       2955851.1     10051516.06      2956345.92      10051849.4
      2957053.86     10052567.76
#Sta/Elev= 30
  4160.6 1236.86  4164.4 1233.13  4193.6 1223.63  4221.4 1221.17  4272.4 1210.22
  4302.1 1207.73  4365.3 1198.26  4398.4 1188.91  4416.3 1185.61  4437.3 1177.74
  4518.2 1157.11  4560.2 1150.51  4634.3 1144.35  4945.9 1123.73  4953.9 1122.31
  4999.5 1112.83  5002.2 1112.33  5005.5 1112.83  5016.6 1116.71  5080.3 1122.47
  5165.2 1125.43  5242.9 1132.05  5275.4 1133.12  5338.3 1137.22    5494 1151.34
  5575.3 1163.37  5596.5 1164.58  5617.7 1170.24  5677.8 1177.11  5765.8 1183.55
#Mann= 10 ,-1 , 0
  4160.6     .16       0  4398.4      .1       0  4634.3     .05       0
  4953.9     .16       0  4999.5     .07       0  5005.5     .16       0
  5275.4     .05       0  5338.3      .1       0    5494     .16       0
  5677.8      .1       0
Bank Sta=4945.9,5080.3
XS Rating Curve= 0 ,0
Exp/Cntr=0.3,0.1

Type RM Length L Ch R = 1 ,55251   ,541,541,541
BEGIN DESCRIPTION:
FLAT CREEK 111.0
END DESCRIPTION:
XS GIS Cut Line= 2
      2955621.94     10051844.17      2956647.21     10052999.56
#Sta/Elev= 30
  4125.5  1211.9  4313.7 1197.74  4378.1 1189.03  4448.3 1182.47  4462.5 1178.81
  4476.8 1172.53  4519.4 1147.51  4556.6 1133.89  4576.3 1129.27  4618.9 1124.25
  4754.1 1121.24  4927.3 1117.21  4937.6 1117.45  4980.2 1115.14  4998.1 1108.97
  5000.9 1108.47  5004.1 1108.97  5015.3 1113.56  5043.8 1119.06  5069.2 1121.44
  5103.1 1123.58    5211 1129.66  5239.8 1131.37  5352.9 1138.58  5376.4 1140.65
    5426 1147.26  5468.6 1156.53    5537 1167.72    5610 1179.33  5670.2 1184.49
#Mann= 13 ,-1 , 0
  4125.5     .16       0  4556.6     .05       0  4754.1      .1       0
  4927.3     .16       0  4998.1     .07       0  5004.1     .16       0
  5069.2     .05       0  5103.1      .1       0    5211     .05       0
  5239.8      .1       0  5352.9     .16       0  5376.4      .1       0
    5537     .05       0
Bank Sta=4937.6,5043.8
XS Rating Curve= 0 ,0
Exp/Cntr=0.3,0.1

Type RM Length L Ch R = 1 ,54710   ,478,478,478
BEGIN DESCRIPTION:
FLAT CREEK 110.0
END DESCRIPTION:
XS GIS Cut Line= 3
      2955486.54      10051719.2      2955804.25     10052990.03
      2956361.52     10053234.81
#Sta/Elev= 30
  3948.3 1236.71  3972.6 1229.62  3977.8  1232.5  4004.5 1220.84    4019 1219.94
  4025.1 1216.35  4045.7 1211.68  4170.2 1206.45  4251.9 1199.29  4348.9 1185.37
  4390.1 1174.64  4437.4 1152.63  4467.4 1141.54  4498.3 1134.22  4549.9 1127.58
  4643.6 1120.95  4816.2 1115.74  4973.4 1111.26  5005.6 1107.04  5008.3 1106.54
  5011.6 1107.04  5044.6 1111.57  5074.6 1118.57  5107.4 1126.35  5310.8  1132.3
  5524.7 1145.08  5622.9 1148.38  5714.3 1156.35  5756.1  1162.9  5866.9  1171.2
#Mann= 10 ,-1 , 0
  3948.3      .1       0  4170.2     .16       0  4498.3     .05       0
  4816.2      .1       0  5005.6     .07       0  5011.6      .1       0
  5074.6     .05       0  5310.8      .1       0  5524.7     .05       0
  5714.3      .1       0
Bank Sta=4973.4,5044.6
XS Rating Curve= 0 ,0
Exp/Cntr=0.3,0.1

Type RM Length L Ch R = 1 ,54232   ,392,392,392
BEGIN DESCRIPTION:
FLAT CREEK 109.0
END DESCRIPTION:
XS GIS Cut Line= 4
      2954476.11     10052266.06      2955215.71     10052818.15
      2955486.54      10053099.4      2956299.07     10053271.29
#Sta/Elev= 30
  3951.2 1212.02  4016.1 1208.87  4122.7 1203.14  4408.3 1199.81    4473 1193.52
  4615.5 1186.01  4679.3 1174.86    4744 1156.13  4758.6 1150.71  4787.8 1133.31
  4808.6 1125.49  4815.2 1120.67  4885.2 1111.47  4922.6 1108.64  4979.1 1106.45
  4990.1 1102.52  4992.8 1102.02  4996.1 1102.52  5021.4 1106.69    5071 1109.54
  5111.2 1113.09  5205.3 1118.98  5353.7 1123.51    5450 1129.27  5593.6 1133.71
  5739.8 1143.91  5920.7 1153.02  6012.6 1161.61  6057.8 1165.41  6095.1 1167.42
#Mann= 10 ,-1 , 0
  3951.2      .1       0  4016.1     .16       0  4885.2     .05       0
  4990.1    .035       0  4996.1     .05       0  5111.2     .16       0
  5353.7      .1       0  5739.8     .05       0  6012.6      .1       0
  6057.8     .16       0
Bank Sta=4922.6,5071
XS Rating Curve= 0 ,0
Exp/Cntr=0.3,0.1

Type RM Length L Ch R = 1 ,53840   ,492,492,492
BEGIN DESCRIPTION:
FLAT CREEK 108.0
END DESCRIPTION:
XS GIS Cut Line= 3
      2954616.75     10052854.61      2954804.25      10053156.7
      2956283.42     10053375.45
#Sta/Elev= 30
  4338.4 1197.53  4368.4  1193.2  4389.7  1195.3  4405.1 1192.89  4447.6 1195.65
  4462.9 1194.23  4484.2 1197.56  4499.5 1194.78  4599.9 1195.01  4705.6 1188.71
  4839.6 1163.65  4900.4 1139.28  4914.2 1130.95  4920.6 1122.59  4930.7 1115.09
  4950.9 1104.96  4998.5 1097.28  5001.2 1096.78  5004.5 1097.28  5028.4 1102.18
  5048.3 1106.85  5313.3 1114.87    5426 1119.53  5466.5 1125.08  5546.1 1129.69
  5688.9 1134.38  5786.2 1140.55  6019.6 1151.36  6068.2 1161.03  6189.2 1168.11
#Mann= 9 ,-1 , 0
  4338.4     .16       0  4998.5     .07       0  5004.5     .16       0
  5028.4     .05       0  5313.3     .16       0  5546.1      .1       0
  5786.2     .05       0  6019.6      .1       0  6068.2     .16       0
Bank Sta=4950.9,5048.3
XS Rating Curve= 0 ,0
Exp/Cntr=0.3,0.1

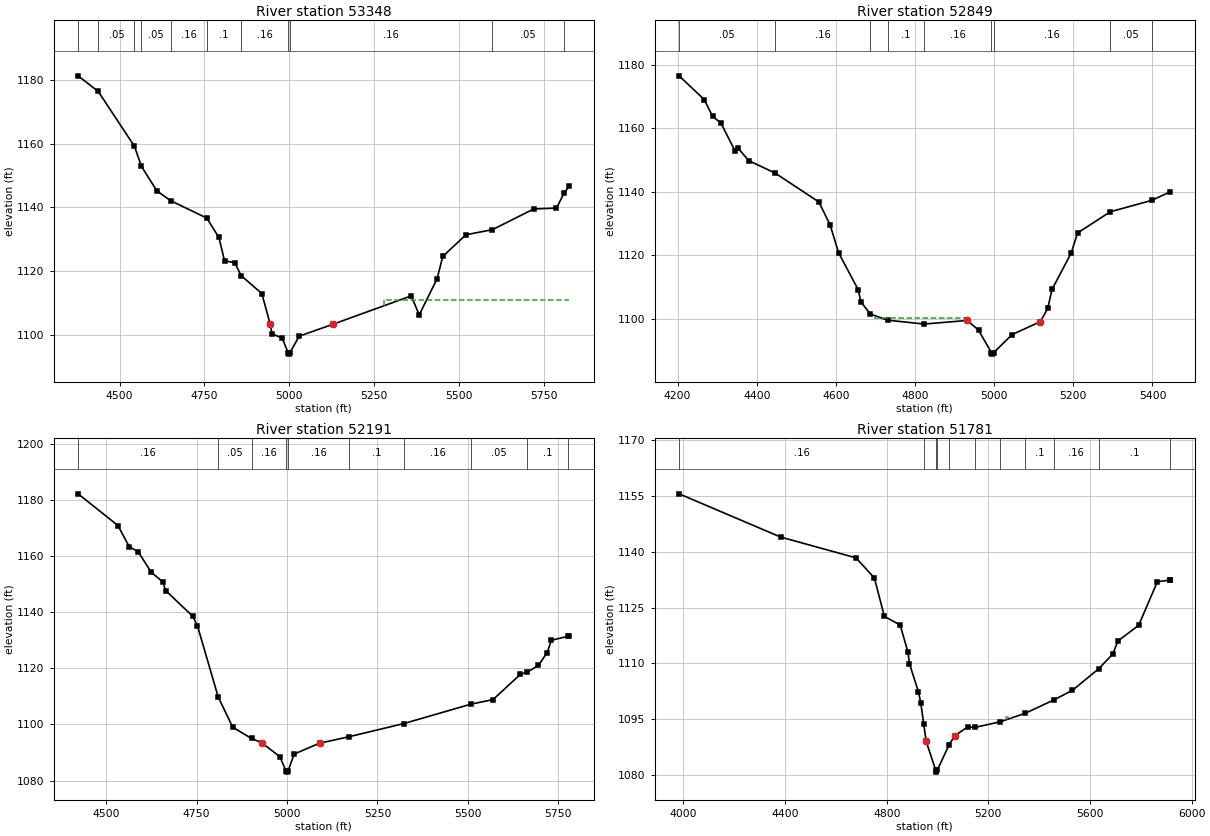
Type RM Length L Ch R = 1 ,53348   ,499,499,499
BEGIN DESCRIPTION:
FLAT CREEK 107.0
END DESCRIPTION:
XS GIS Cut Line= 4
      2954475.34     10053509.77      2954851.71     10053684.52
      2955379.27      10053694.6      2955854.93     10053862.08
#Sta/Elev= 30
  4377.5 1181.25  4436.9 1176.35  4543.5 1159.18  4564.4 1152.84  4609.7 1145.17
  4650.2 1142.11  4756.9 1136.63  4792.5 1130.56  4809.2 1123.23  4839.2 1122.64
  4858.2 1118.59  4919.2 1112.95 4943.52 1103.43  4949.2 1100.37  4979.3 1098.95
  4996.3 1094.47    4999 1093.97  5002.3 1094.47  5029.3  1099.6  5129.3 1103.36
  5359.5 1112.24  5382.9 1106.26  5435.9 1117.67  5452.4 1124.61  5520.7  1131.4
  5598.9 1133.01  5720.4 1139.49  5787.6 1139.78  5809.9 1144.47  5824.4 1146.56
#Mann= 11 ,-1 , 0
  4377.5      .1       0  4436.9     .05       0  4543.5      .1       0
  4564.4     .05       0  4650.2     .16       0  4756.9      .1       0
  4858.2     .16       0  4996.3     .07       0  5002.3     .16       0
  5598.9     .05       0  5809.9      .1       0
#XS Ineff= 2 , 0
                            5280         1110.94
Permanent Ineff=
       T       T
Bank Sta=4943.52,5129.3
XS Rating Curve= 0 ,0
Exp/Cntr=0.3,0.1

Type RM Length L Ch R = 1 ,52849   ,658,658,658
BEGIN DESCRIPTION:
FLAT CREEK 106.0
END DESCRIPTION:
XS GIS Cut Line= 4
        2954472.     10053610.58      2954915.56     10054070.94
      2955103.73     10054242.31      2955424.85     10054372.77
#Sta/Elev= 30
    4204 1176.45  4267.3 1168.99  4288.7 1163.71  4309.8 1161.59  4345.3 1152.84
  4352.2 1153.81  4380.5 1149.75  4446.2 1145.92  4557.2  1136.8  4585.5 1129.61
  4606.9 1120.86  4656.3 1109.28  4663.5  1105.4  4687.1 1101.59    4731 1099.65
  4823.2 1098.45  4932.1 1099.57  4960.5 1096.54    4993 1089.49  4995.7 1088.99
    4999 1089.49  5045.6 1095.15    5117 1099.21  5135.3 1103.33  5146.4 1109.37
  5194.6 1120.73  5210.8 1127.07  5293.7 1133.74  5398.4 1137.31  5444.4 1139.98
#Mann= 9 ,-1 , 0
    4204     .05       0  4446.2     .16       0  4687.1     .05       0
    4731      .1       0  4823.2     .16       0    4993     .07       0
    4999     .16       0  5293.7     .05       0  5398.4     .08       0
#XS Ineff= 1 ,-1
 4695.91  4925.4 1100.21
Permanent Ineff=
       T
Bank Sta=4932.1,5117
XS Rating Curve= 0 ,0
Exp/Cntr=0.3,0.1

Type RM Length L Ch R = 1 ,52191   ,410,410,410
BEGIN DESCRIPTION:
FLAT CREEK 105.0
END DESCRIPTION:
XS GIS Cut Line= 4
      2954361.12     10053597.16      2954445.13     10053916.37
      2954465.29     10054302.79      2955065.12     10054527.31
#Sta/Elev= 30
  4422.1 1182.31  4532.3 1170.99  4563.3 1163.49  4588.8 1161.57    4624 1154.38
  4656.4 1150.87  4664.3 1147.81  4739.1 1138.61  4752.2 1135.21  4809.5 1109.84
  4849.7 1099.02  4901.9    1095  4929.8 1093.48  4979.8 1088.55  4996.9  1083.5
  4999.6    1083  5002.9  1083.5  5019.9 1089.47    5090 1093.32    5172 1095.65
  5323.2 1100.34  5508.9 1107.27  5569.6 1108.88  5645.4 1117.92  5664.4 1118.71
  5695.2 1121.07  5719.1 1125.64  5730.9 1130.05  5775.9 1131.45  5779.6 1131.43
#Mann= 10 ,-1 , 0
  4422.1     .16       0  4809.5     .05       0  4901.9     .16       0
  4996.9     .07       0  5002.9     .16       0    5172      .1       0
  5323.2     .16       0  5508.9     .05       0  5664.4      .1       0
  5775.9     .05       0
Bank Sta=4929.8,5090
XS Rating Curve= 0 ,0
Exp/Cntr=0.3,0.1

Type RM Length L Ch R = 1 ,51781   ,395,395,395
BEGIN DESCRIPTION:
FLAT CREEK 103.0
END DESCRIPTION:
XS GIS Cut Line= 3
      2953158.17     10054158.31      2954535.85       10054454.
      2955049.96     10054548.09
#Sta/Elev= 30
  3983.1 1155.62  4382.3 1143.99  4678.9 1138.39  4751.6 1132.97  4790.7 1122.63
  4852.8 1120.32  4883.4 1113.06  4889.5 1109.92  4924.4  1102.4  4933.8 1099.45
  4945.8  1093.6    4955 1089.03  4992.9 1081.21  4995.7 1080.71  4998.9 1081.21
  5045.8 1088.11  5067.5  1090.5  5118.7 1092.89  5145.8 1092.73  5245.8 1094.24
  5345.8 1096.57  5457.6 1100.14  5530.8 1102.73  5634.4 1108.54  5689.6 1112.51
    5710 1116.02  5791.3 1120.22  5865.2 1131.98  5914.2 1132.37  5914.8 1132.37
#Mann= 11 ,-1 , 0
  3983.1     .16       0  4945.8     .05       0  4992.9    .035       0
  4998.9     .05       0  5045.8      .1       0  5145.8     .05       0
  5245.8     .16       0  5345.8      .1       0  5457.6     .16       0
  5634.4      .1       0  5914.2     .05       0
#XS Ineff= 2 ,-1
 5175.53  5211.6    1093 5269.09 5288.34 1095.44
Permanent Ineff=
       T       T
Bank Sta=4955,5067.5
XS Rating Curve= 0 ,0
Exp/Cntr=0.3,0.1