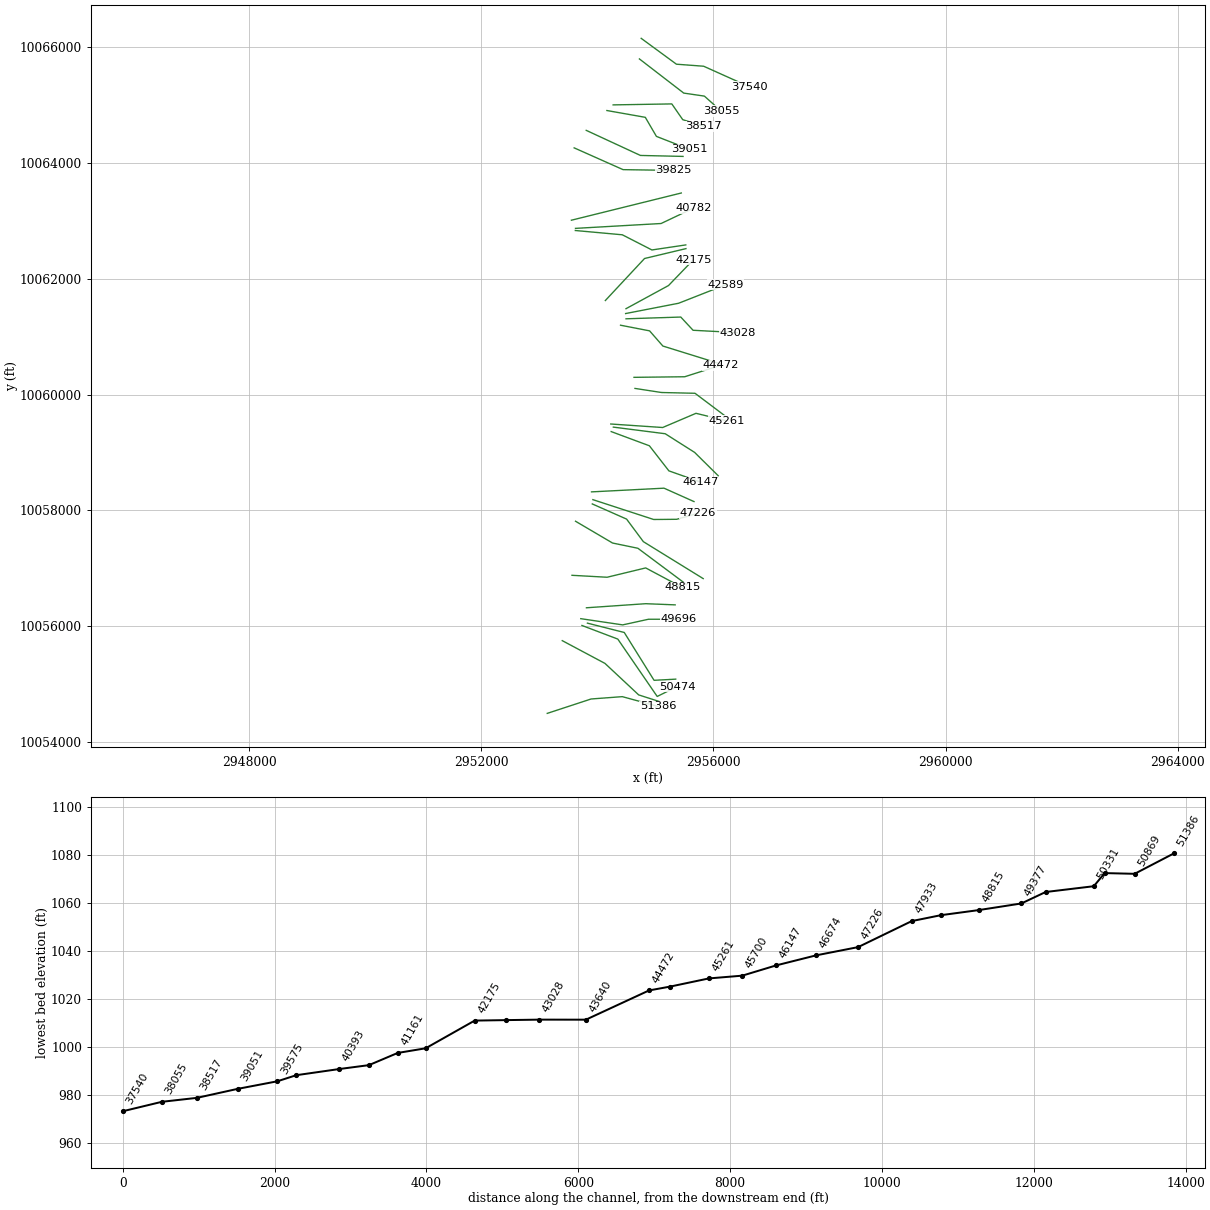
HEC-RAS study FLAT CREEK.prj: FLAT CREEK Base Level Engineering

--- FLAT CREEK.g01 (geometry) --- (continued)

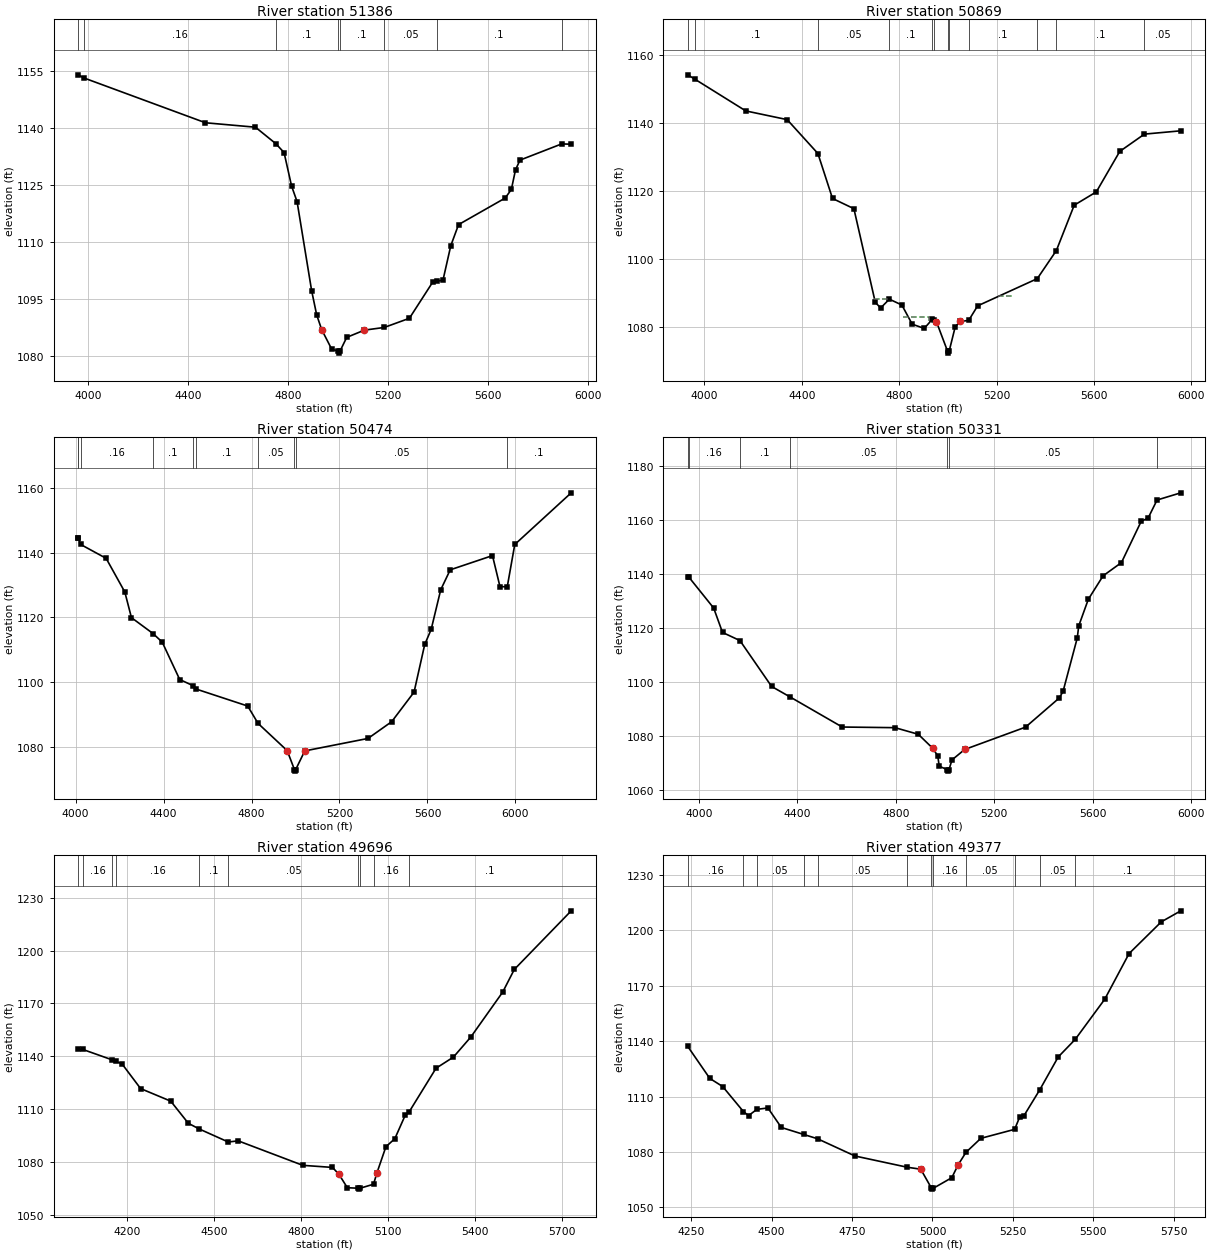
Type RM Length L Ch R = 1 ,51386   ,517,517,517
BEGIN DESCRIPTION:
FLAT CREEK 102.0
END DESCRIPTION:
XS GIS Cut Line= 4
      2953134.66     10054494.33      2953890.69     10054742.98
      2954428.32     10054783.31      2955043.27     10054615.29
#Sta/Elev= 30
  3959.2    1154  3980.7 1153.21  4468.5 1141.38  4668.5 1140.21    4750 1135.87
  4782.9 1133.54    4813 1124.71    4835 1120.61  4893.2 1097.18  4913.3 1090.83
  4933.3 1086.94  4973.5 1081.78  5000.5 1081.24  5003.3 1080.74  5006.5 1081.24
  5033.6 1084.89  5104.1 1086.79  5183.7  1087.5  5284.3 1089.91  5377.3  1099.4
    5393 1099.62  5418.8 1099.98  5449.9 1109.01    5481 1114.57  5667.6 1121.56
  5692.2 1123.82    5709 1129.01  5726.8 1131.55  5893.4 1135.81  5931.7 1135.74
#Mann= 8 ,-1 , 0
  3959.2      .1       0  3980.7     .16       0    4750      .1       0
  5000.5     .07       0  5006.5      .1       0  5183.7     .05       0
    5393      .1       0  5893.4     .05       0
Bank Sta=4933.3,5104.1
XS Rating Curve= 0 ,0
Exp/Cntr=0.3,0.1

Type RM Length L Ch R = 1 ,50869   ,395,395,395
BEGIN DESCRIPTION:
FLAT CREEK 101.0
END DESCRIPTION:
XS GIS Cut Line= 4
      2953393.42     10055751.03      2954129.27      10055357.9
      2954710.58     10054813.55      2955085.23     10054693.12
#Sta/Elev= 30
  3931.8 1154.04  3959.7 1152.82    4170 1143.43  4339.9 1140.87  4466.2  1130.9
  4526.1 1117.69  4613.9 1114.69  4701.7 1087.17  4723.7 1085.49  4759.6 1088.08
  4810.8 1086.37  4853.3 1080.73  4902.7 1079.48  4936.1 1082.19  4944.6 1081.99
  4952.5 1081.51  4998.8 1072.72  5001.6 1072.22  5004.8 1072.72  5030.2 1080.03
  5051.6 1081.53  5085.3 1081.85    5122 1086.12  5366.9 1094.12  5445.2 1102.38
  5518.5 1115.71  5609.2 1119.62  5705.5 1131.52  5806.8 1136.61    5956 1137.58
#Mann= 12 ,-1 , 0
  3931.8     .05       0  3959.7      .1       0  4466.2     .05       0
  4759.6      .1       0  4936.1     .05       0  4944.6     .16       0
  4998.8     .07       0  5004.8     .16       0  5085.3      .1       0
  5366.9     .05       0  5445.2      .1       0  5806.8     .05       0
#XS Ineff= 4 ,-1
 4696.01 4753.89 1088.21 4814.57 4924.33 1082.74 5207.09 5264.26 1089.14
 5277.77 5292.13 1089.97
Permanent Ineff=
       T       T       T       T
Bank Sta=4952.5,5051.6
XS Rating Curve= 0 ,0
Exp/Cntr=0.3,0.1

Type RM Length L Ch R = 1 ,50474   ,143,143,143
BEGIN DESCRIPTION:
FLAT CREEK 100.0
END DESCRIPTION:
XS GIS Cut Line= 4
      2953732.77     10056013.14      2954351.04     10055777.93
       2955029.8     10054786.67      2955369.21     10054954.69
#Sta/Elev= 30
  4011.9 1144.42  4012.4 1144.36  4022.9  1142.5  4138.9 1138.21  4223.9 1127.82
    4254  1119.9  4352.1 1114.99  4393.9 1112.35  4473.5  1100.8  4535.8 1098.85
  4548.8 1097.84  4782.7 1092.61  4829.6 1087.26  4962.1 1078.85    4995 1073.02
  4997.7 1072.52    5001 1073.02  5042.1 1078.76  5329.7 1082.61  5437.4 1087.79
    5539 1096.91  5587.5 1111.62  5616.8 1116.26  5660.2 1128.49  5703.4 1134.66
  5895.6 1139.05  5929.6 1129.49  5962.7  1129.4  5996.9 1142.48  6253.5 1158.43
#Mann= 10 ,-1 , 0
  4011.9     .05       0  4012.4      .1       0  4022.9     .16       0
  4352.1      .1       0  4535.8     .16       0  4548.8      .1       0
  4829.6     .05       0    4995     .04       0    5001     .05       0
  5962.7      .1       0
Bank Sta=4962.1,5042.1
XS Rating Curve= 0 ,0
Exp/Cntr=0.3,0.1

Type RM Length L Ch R = 1 ,50331   ,635,635,635
BEGIN DESCRIPTION:
FLAT CREEK 99.0
END DESCRIPTION:
XS GIS Cut Line= 4
      2953826.83     10056053.47      2954461.93     10055892.18
      2954976.04     10055065.56      2955348.99     10055085.72
#Sta/Elev= 30
    3955    1139  3958.4    1139  4060.3 1127.42  4096.1  1118.4  4166.9 1115.38
  4295.6 1098.39  4370.1 1094.53  4582.3 1083.37  4796.7 1083.13  4891.1 1080.69
    4949 1075.58  4970.3 1072.72  4976.2 1068.87  5009.8 1067.54  5012.5 1067.04
  5015.8 1067.54  5028.1  1071.2  5079.5 1075.05  5326.8 1083.33  5463.7 1094.12
  5479.1 1096.55  5536.9 1116.36  5542.8 1120.81  5581.8 1130.68  5641.8 1139.36
  5716.3 1144.26  5796.4 1159.52  5824.6 1160.74  5860.9 1167.43  5957.2 1170.09
#Mann= 7 ,-1 , 0
    3955      .1       0  3958.4     .16       0  4166.9      .1       0
  4370.1     .05       0  5009.8     .04       0  5015.8     .05       0
  5860.9      .1       0
Bank Sta=4949,5079.5
XS Rating Curve= 0 ,0
Exp/Cntr=0.3,0.1

Type RM Length L Ch R = 1 ,49696   ,319,319,319
BEGIN DESCRIPTION:
FLAT CREEK 98.0
END DESCRIPTION:
XS GIS Cut Line= 4
       2953712.6     10056130.75      2954435.05     10056023.22
      2954878.59     10056120.67      2955394.76     10056120.67
#Sta/Elev= 30
  4031.9    1144  4047.8  1143.9  4149.1 1137.99  4161.2 1137.17    4183 1135.73
  4247.2 1121.69  4351.2 1114.55  4411.9 1101.98  4449.3 1098.77  4549.7 1091.36
  4583.8 1092.03  4806.8 1078.12  4909.1 1076.94  4931.3 1073.06  4960.3 1065.43
  4998.3 1065.12    5001 1064.62  5004.3 1065.12  5050.7 1067.41  5062.6 1073.92
  5093.4 1088.67  5124.2 1093.25  5160.4 1106.69  5172.4 1108.15  5266.3 1133.23
  5326.3 1139.56  5386.3 1150.95  5496.3 1176.45  5536.3  1189.3  5732.6 1222.58
#Mann= 10 ,-1 , 0
  4031.9     .05       0  4047.8     .16       0  4149.1      .1       0
  4161.2     .16       0  4449.3      .1       0  4549.7     .05       0
  4998.3    .035       0  5004.3     .05       0  5050.7     .16       0
  5172.4      .1       0
Bank Sta=4931.3,5062.6
XS Rating Curve= 0 ,0
Exp/Cntr=0.3,0.1

Type RM Length L Ch R = 1 ,49377   ,562,562,562
BEGIN DESCRIPTION:
FLAT CREEK 97.0
END DESCRIPTION:
XS GIS Cut Line= 3
      2953810.09     10056318.93      2954831.55     10056389.49
      2955338.96     10056369.33
#Sta/Elev= 30
  4239.7 1137.13  4308.2 1119.81  4348.3 1115.39  4412.6 1101.86  4428.5 1099.66
  4454.6 1103.05  4488.7 1103.81  4530.4 1093.24  4599.8 1089.46  4642.9 1087.12
  4759.3 1077.78  4922.1 1071.68  4963.6 1070.63  4996.9 1060.34  4999.6 1059.84
  5002.9 1060.34    5060 1066.03  5080.1 1073.11    5104 1079.75  5150.2 1087.35
  5255.2 1092.22  5270.5 1098.69  5284.1 1099.57  5333.4 1113.66  5390.6 1131.42
  5443.3 1140.91  5535.1 1162.67  5610.8 1187.43  5710.9 1204.61  5771.4 1210.58
#Mann= 12 ,-1 , 0
  4239.7     .16       0  4412.6      .1       0  4454.6     .05       0
  4599.8      .1       0  4642.9     .05       0  4922.1     .16       0
  4996.9     .07       0  5002.9     .16       0    5104     .05       0
  5255.2      .1       0  5333.4     .05       0  5443.3      .1       0
Bank Sta=4963.6,5080.1
XS Rating Curve= 0 ,0
Exp/Cntr=0.3,0.1

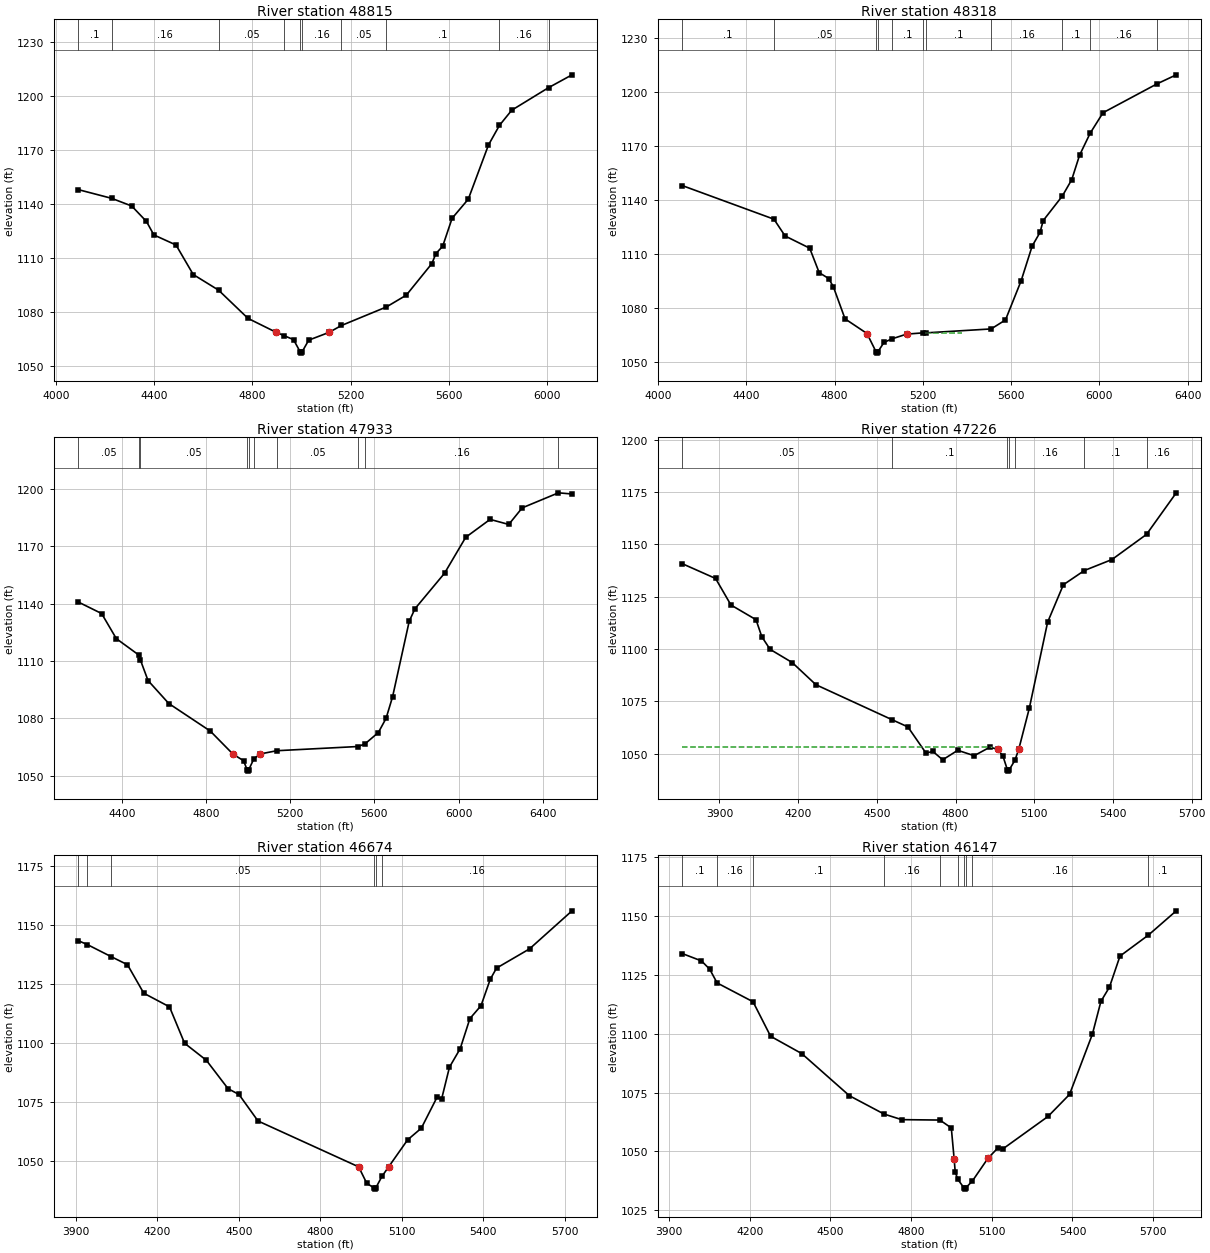
Type RM Length L Ch R = 1 ,48815   ,497,497,497
BEGIN DESCRIPTION:
FLAT CREEK 96.0
END DESCRIPTION:
XS GIS Cut Line= 4
      2953561.35     10056880.08      2954166.23     10056846.48
      2954831.55     10057007.77      2955464.71     10056669.41
#Sta/Elev= 30
  4091.6 1148.06  4227.1 1143.22  4309.1 1138.94  4369.1 1130.33  4399.2 1122.84
  4489.3 1117.24  4559.4  1100.8  4662.2 1092.13    4782 1076.41  4895.2 1068.75
  4928.9 1066.78  4967.2 1064.59  4995.1 1057.57  4997.9 1057.07  5001.1 1057.57
    5029 1064.29  5111.3 1068.59  5162.2 1072.45  5345.1 1082.77    5426 1089.34
    5530 1106.92  5546.3 1112.46  5573.9 1116.57  5612.1 1132.09    5678 1142.74
  5760.1 1172.89  5804.8 1183.82  5854.7 1192.24  6004.6  1204.8  6099.9 1211.93
#Mann= 10 ,-1 , 0
  4091.6      .1       0  4227.1     .16       0  4662.2     .05       0
  4928.9     .16       0  4995.1     .07       0  5001.1     .16       0
  5162.2     .05       0  5345.1      .1       0  5804.8     .16       0
  6004.6      .1       0
Bank Sta=4895.2,5111.3
XS Rating Curve= 0 ,0
Exp/Cntr=0.3,0.1

Type RM Length L Ch R = 1 ,48318   ,385,385,385
BEGIN DESCRIPTION:
FLAT CREEK 95.0
END DESCRIPTION:
XS GIS Cut Line= 4
      2953621.89     10057814.21      2954260.31     10057437.88
      2954697.14     10057347.15       2955537.2     10056718.79
#Sta/Elev= 30
  4111.4 1148.03  4525.7 1129.39  4576.3 1120.05  4687.6 1113.28  4730.6 1099.68
  4773.5 1096.42  4794.9 1091.81  4847.7    1074  4947.1 1065.85  4989.1 1055.45
  4991.9 1054.95  4995.1 1055.45  5024.2 1060.92  5060.3 1062.89  5126.4 1065.51
  5201.7 1066.22  5216.6 1066.22  5509.3  1068.4  5574.3 1073.39  5645.2 1095.16
  5695.2 1114.47  5730.6 1122.02  5745.2 1128.63  5831.8 1142.27  5874.4 1151.36
  5909.8 1164.94  5957.8 1177.16  6016.1 1188.56  6260.9 1204.62  6347.7 1209.62
#Mann= 11 ,-1 , 0
  4111.4      .1       0  4525.7     .05       0  4989.1    .035       0
  4995.1     .05       0  5060.3      .1       0  5201.7     .05       0
  5216.6      .1       0  5509.3     .16       0  5831.8      .1       0
  5957.8     .16       0  6260.9      .1       0
#XS Ineff= 2 ,-1
    5208 5378.54 1066.35    5480 5510.33 1068.09
Permanent Ineff=
       T       T
Bank Sta=4947.1,5126.4
XS Rating Curve= 0 ,0
Exp/Cntr=0.3,0.1

Type RM Length L Ch R = 1 ,47933   ,707,707,707
BEGIN DESCRIPTION:
FLAT CREEK 94.0
END DESCRIPTION:
XS GIS Cut Line= 4
      2953910.87     10058113.27      2954502.25     10057851.18
      2954791.23      10057461.4      2955822.77     10056822.98
#Sta/Elev= 30
  4193.5  1140.9  4304.6 1134.86  4374.4 1121.75  4481.4 1113.16    4489 1110.53
    4525 1099.84  4623.6 1087.83  4820.8 1073.41  4928.5 1061.36  4978.5 1057.94
  4996.4 1052.98  4999.1 1052.48  5002.4 1052.98  5027.5 1058.88  5057.9 1061.46
  5136.4 1063.15  5522.5 1065.35  5555.3 1066.71  5618.9 1072.66  5655.6 1080.09
  5686.4 1091.33  5765.5 1130.84  5792.7 1137.36  5933.3 1155.94  6033.8 1174.72
  6149.6 1184.08  6238.2 1181.44    6302  1190.1  6474.1 1197.97  6538.7 1197.36
#Mann= 10 ,-1 , 0
  4193.5     .05       0  4481.4      .1       0    4489     .05       0
  4996.4    .035       0  5002.4     .05       0  5027.5     .16       0
  5136.4     .05       0  5522.5      .1       0  5555.3     .16       0
  6474.1      .1       0
Bank Sta=4928.5,5057.9
XS Rating Curve= 0 ,0
Exp/Cntr=0.3,0.1

Type RM Length L Ch R = 1 ,47226   ,552,552,552
BEGIN DESCRIPTION:
FLAT CREEK 93.0
END DESCRIPTION:
XS GIS Cut Line= 4
      2953920.98     10058187.19      2954969.32     10057844.46
      2955365.82     10057847.82       2955734.5     10057951.72
#Sta/Elev= 30
  3758.8 1140.72  3885.1 1133.69  3943.6 1121.02  4039.2 1113.99  4061.3 1105.85
  4092.8 1099.83  4177.2 1093.51  4267.6 1082.91    4558 1066.18  4618.2 1062.74
  4687.2 1050.23  4713.6 1051.02  4750.9 1047.02  4808.2 1051.56  4870.9 1048.99
  4930.9 1053.05  4960.9 1052.05  4980.9 1048.67  4997.9 1042.11  5000.6 1041.61
  5003.9 1042.11  5026.2 1046.79  5040.9 1052.07  5080.9 1071.56  5150.9 1112.79
  5210.9 1130.69  5291.1  1137.5  5396.1 1142.74  5527.9 1154.76  5641.3 1174.63
#Mann= 7 ,-1 , 0
  3758.8     .05       0    4558      .1       0  4997.9     .07       0
  5003.9      .1       0  5026.2     .16       0  5291.1      .1       0
  5527.9     .16       0
#XS Ineff= 2 , 0
         4938.92 1053.14
Permanent Ineff=
       T       T
Bank Sta=4960.9,5040.9
XS Rating Curve= 0 ,0
Exp/Cntr=0.3,0.1

Type RM Length L Ch R = 1 ,46674   ,527,527,527
BEGIN DESCRIPTION:
FLAT CREEK 91.0
END DESCRIPTION:
XS GIS Cut Line= 3
      2953897.45     10058321.61      2955147.41     10058385.46
      2955664.22      10058153.9
#Sta/Elev= 30
  3908.7 1143.31  3942.3 1141.66  4030.9  1136.5    4090 1133.14    4150 1121.08
  4244.7 1115.31  4300.2 1099.92  4380.3 1092.71  4460.4 1080.67  4500.5 1078.23
  4570.6 1067.01  4941.1 1047.61  4971.1 1040.61  4998.1 1038.68  5000.9 1038.18
  5004.1 1038.68  5026.7 1043.54  5051.2 1047.57  5121.3 1059.03  5171.8 1063.97
  5229.2 1076.96  5246.9 1076.51  5275.5 1089.82  5314.9 1097.61  5350.6 1110.34
  5391.5  1115.8  5425.6 1126.99  5448.8 1131.71  5570.2 1139.84  5726.6 1155.94
#Mann= 6 ,-1 , 0
  3908.7     .16       0  3942.3      .1       0  4030.9     .05       0
  4998.1    .035       0  5004.1     .05       0  5026.7     .16       0
Bank Sta=4941.1,5051.2
XS Rating Curve= 0 ,0
Exp/Cntr=0.3,0.1

Type RM Length L Ch R = 1 ,46147   ,447,447,447
BEGIN DESCRIPTION:
FLAT CREEK 90.0
END DESCRIPTION:
XS GIS Cut Line= 4
       2954236.8     10059363.27      2954895.39     10059117.98
      2955231.42     10058684.52      2955782.52     10058489.61
#Sta/Elev= 30
    3950 1134.12  4020.7 1131.02  4051.1 1127.53  4078.8 1121.66  4212.4 1113.65
  4277.7 1098.98  4393.7  1091.6  4570.7  1073.7  4699.1 1065.92  4764.8 1063.53
  4907.1 1063.35  4949.5    1060 4960.23 1046.63    4964 1041.27  4973.6 1038.15
  4996.8 1034.48  4999.5 1033.98  5002.8 1034.48  5027.6 1037.39  5086.2 1047.16
  5121.5 1051.35  5142.3 1051.17    5309 1064.88    5389 1074.24  5473.9 1099.82
  5505.7 1113.81  5537.5 1119.89  5576.6 1133.07  5682.3 1142.01  5785.8 1152.32
#Mann= 10 ,-1 , 0
    3950      .1       0  4078.8     .16       0  4212.4      .1       0
  4699.1     .16       0  4907.1      .1       0  4973.6     .05       0
  4996.8    .035       0  5002.8     .05       0  5027.6     .16       0
  5682.3      .1       0
Bank Sta=4960.23,5086.2
XS Rating Curve= 0 ,0
Exp/Cntr=0.3,0.1

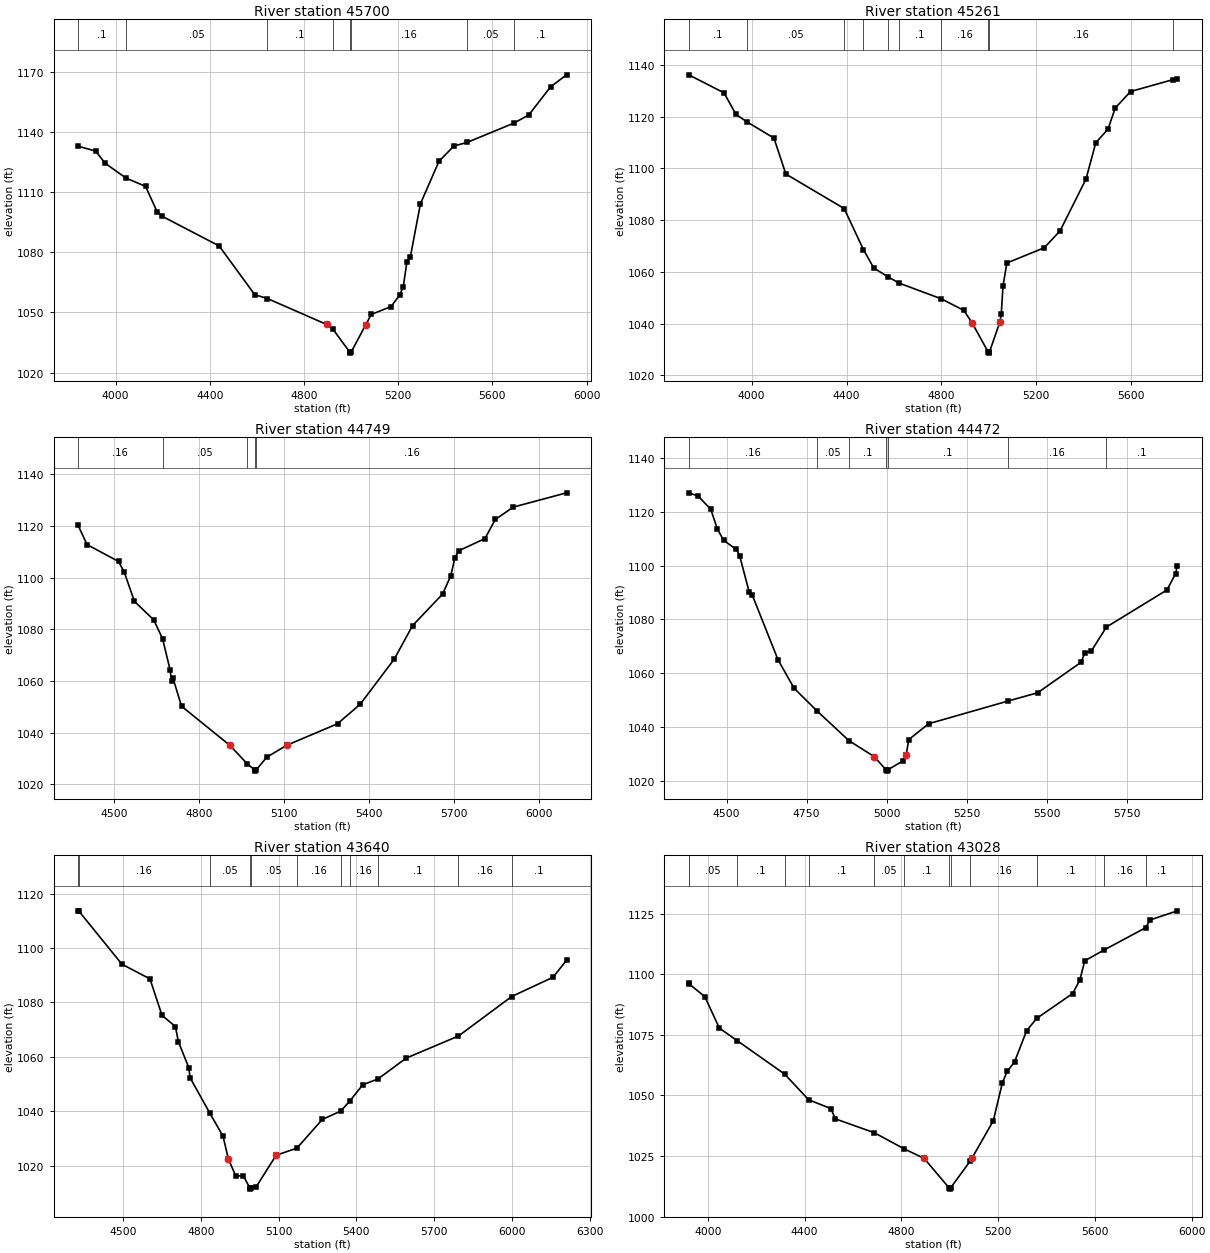
Type RM Length L Ch R = 1 ,45700   ,439,439,439
BEGIN DESCRIPTION:
FLAT CREEK 89.0
END DESCRIPTION:
XS GIS Cut Line= 4
       2954273.8     10059440.56      2955167.57     10059326.32
      2955674.96     10059003.74      2956081.53     10058600.53
#Sta/Elev= 30
  3840.1 1133.07  3915.4 1130.58  3955.7 1124.51  4044.5 1117.09  4127.1 1112.99
  4177.5 1099.96  4197.7 1098.04  4439.6 1083.24  4590.8 1058.89  4644.6 1056.96
  4896.3    1044  4922.1 1041.78  4994.3 1030.19    4997 1029.69  5000.3 1030.19
  5062.2 1043.84  5085.4 1048.99    5170 1052.97  5206.4 1058.72  5221.7 1062.94
  5236.9 1075.13  5251.7 1077.79  5294.5 1104.29  5373.2 1125.49  5436.8 1133.15
    5492  1134.9  5692.5 1144.62    5755 1148.69  5846.9 1162.65    5915 1168.69
#Mann= 8 ,-1 , 0
  3840.1      .1       0  4044.5     .05       0  4644.6      .1       0
  4922.1     .16       0  4994.3     .07       0  5000.3     .16       0
    5492     .05       0  5692.5      .1       0
Bank Sta=4896.3,5062.2
XS Rating Curve= 0 ,0
Exp/Cntr=0.3,0.1

Type RM Length L Ch R = 1 ,45261   ,512,512,512
BEGIN DESCRIPTION:
FLAT CREEK 88.0
END DESCRIPTION:
XS GIS Cut Line= 4
      2954230.09     10059494.33      2955123.89     10059433.84
      2955698.49     10059679.14      2956222.65     10059551.46
#Sta/Elev= 30
  3734.9 1136.23  3883.6 1129.25  3933.7 1120.93  3979.3 1118.08  4094.1 1111.74
  4144.2 1097.84  4390.1 1084.49  4471.5 1068.57  4515.1 1061.45  4574.3 1058.12
  4621.2 1055.65  4800.5 1049.52  4894.6 1045.08  4929.3  1040.3  4996.9 1029.04
  4999.6 1028.54  5002.9 1029.04  5047.1 1040.66  5052.5 1043.63  5059.8 1054.45
  5076.1 1063.41  5234.1 1069.33  5300.6 1075.88  5409.9 1095.91    5451 1109.93
  5502.5 1115.22  5533.4 1123.43  5597.8 1129.77  5776.2 1134.36    5795 1134.65
#Mann= 10 ,-1 , 0
  3734.9      .1       0  3979.3     .05       0  4390.1      .1       0
  4471.5     .05       0  4574.3     .16       0  4621.2      .1       0
  4800.5     .16       0  4996.9     .07       0  5002.9     .16       0
  5776.2      .1       0
Bank Sta=4929.3,5047.1
XS Rating Curve= 0 ,0
Exp/Cntr=0.3,0.1

Type RM Length L Ch R = 1 ,44749   ,277,277,277
BEGIN DESCRIPTION:
FLAT CREEK 87.0
END DESCRIPTION:
XS GIS Cut Line= 4
      2954646.72     10060109.25      2955103.73     10060038.68
      2955681.69     10060025.24       2956229.4     10059611.93
#Sta/Elev= 30
    4371 1120.28  4403.1 1112.74  4514.4 1106.21  4534.7 1102.05  4570.5 1090.79
  4638.7 1083.63  4670.1 1076.31  4696.6 1064.28  4701.8 1059.97  4706.9 1061.05
    4737 1050.23  4908.2 1035.05  4969.3 1027.95  4995.2 1025.62    4998 1025.12
  5001.2 1025.62  5038.2  1030.5  5108.2 1035.09  5288.3 1043.44  5368.3 1050.98
  5488.8 1068.43  5553.4  1081.4  5659.5 1093.58  5688.7  1100.7  5703.2 1107.71
  5717.8 1110.41  5809.4 1115.07    5846 1122.45  5909.3 1127.23  6097.7 1132.76
#Mann= 5 ,-1 , 0
    4371     .16       0  4670.1     .05       0  4969.3     .16       0
  4995.2     .07       0  5001.2     .16       0
Bank Sta=4908.2,5108.2
XS Rating Curve= 0 ,0
Exp/Cntr=0.3,0.1

Type RM Length L Ch R = 1 ,44472   ,832,832,832
BEGIN DESCRIPTION:
FLAT CREEK 86.0
END DESCRIPTION:
XS GIS Cut Line= 3
      2954629.92     10060300.78      2955503.59     10060310.86
      2956123.78     10060508.65
#Sta/Elev= 30
  4382.2  1127.1  4410.7 1125.94  4450.8    1121  4470.8 1113.81  4490.8  1109.4
  4530.8 1106.06  4540.8 1103.76  4570.8  1090.1  4580.8  1088.9  4660.8 1064.94
  4710.8 1054.37    4783 1045.85  4881.7  1034.9  4960.8 1028.92  4997.8 1024.02
  5000.5 1023.52  5003.8 1024.02  5050.8 1027.36  5060.8 1029.69  5068.7 1035.25
  5130.8 1041.16  5379.1 1049.63    5471 1052.69  5606.6 1064.05  5617.9 1067.52
  5638.8 1068.29  5685.6 1077.15  5874.7 1090.96  5901.3    1097  5906.9 1100.03
#Mann= 7 ,-1 , 0
  4382.2     .16       0    4783     .05       0  4881.7      .1       0
  4997.8     .07       0  5003.8      .1       0  5379.1     .16       0
  5685.6      .1       0
Bank Sta=4960.8,5060.8
XS Rating Curve= 0 ,0
Exp/Cntr=0.3,0.1

Type RM Length L Ch R = 1 ,43640   ,612,612,612
BEGIN DESCRIPTION:
FLAT CREEK 85.0
END DESCRIPTION:
XS GIS Cut Line= 4
      2954398.12     10061201.31      2954898.76     10061103.87
      2955127.25     10060841.77      2956108.46     10060535.98
#Sta/Elev= 30
  4325.7 1113.67  4328.3 1113.67  4495.2 1094.05  4603.6 1088.62  4650.1 1075.19
  4701.7 1071.12  4713.2 1065.53  4753.4 1055.99  4758.5 1052.26  4835.1 1039.17
  4885.4  1030.8  4906.3 1022.36  4934.8 1016.11  4963.3 1016.25  4988.8 1011.81
  4991.5 1011.31  4994.8 1011.81  5012.7 1012.05  5090.5 1023.76  5170.8  1026.4
  5268.5 1036.92  5339.9 1040.03  5374.5 1043.66  5424.7 1049.69    5483  1051.8
  5592.5  1059.5  5794.2 1067.63  5999.4 1082.15  6158.8 1089.23  6211.2 1095.47
#Mann= 11 ,-1 , 0
  4325.7      .1       0  4328.3     .16       0  4835.1     .05       0
  4988.8     .07       0  4994.8     .05       0  5170.8     .16       0
  5339.9      .1       0  5374.5     .16       0    5483      .1       0
  5794.2     .16       0  5999.4      .1       0
Bank Sta=4906.3,5090.5
XS Rating Curve= 0 ,0
Exp/Cntr=0.3,0.1

Type RM Length L Ch R = 1 ,43028   ,439,439,439
BEGIN DESCRIPTION:
FLAT CREEK 83.0
END DESCRIPTION:
XS GIS Cut Line= 4
      2954492.18      10061312.2      2955436.39     10061342.45
      2955648.08     10061113.95      2956410.84     10061073.63
#Sta/Elev= 30
  3920.9  1096.3  3923.3 1095.96  3987.2 1090.79  4047.3  1077.8  4120.5 1072.65
  4317.7 1058.78  4416.2 1048.22  4507.5 1044.61  4527.5 1040.31  4687.5 1034.63
  4810.7    1028  4894.3 1023.99  4997.3 1011.83  5000.1 1011.33  5003.3 1011.83
    5085 1022.99  5092.7 1024.29  5179.8 1039.51  5217.5 1055.24  5237.5 1059.99
  5267.6  1063.8  5317.7 1076.73  5359.7 1081.83  5507.9 1092.06    5538 1097.72
    5558 1105.57  5637.2    1110  5809.7 1119.23  5828.4 1122.45  5940.9 1126.21
#Mann= 13 ,-1 , 0
  3920.9      .1       0  3923.3     .05       0  4120.5      .1       0
  4317.7     .05       0  4416.2      .1       0  4687.5     .05       0
  4810.7      .1       0  4997.3     .07       0  5003.3      .1       0
    5085     .16       0  5359.7      .1       0  5637.2     .16       0
  5809.7      .1       0
Bank Sta=4894.3,5092.7
XS Rating Curve= 0 ,0
Exp/Cntr=0.3,0.1

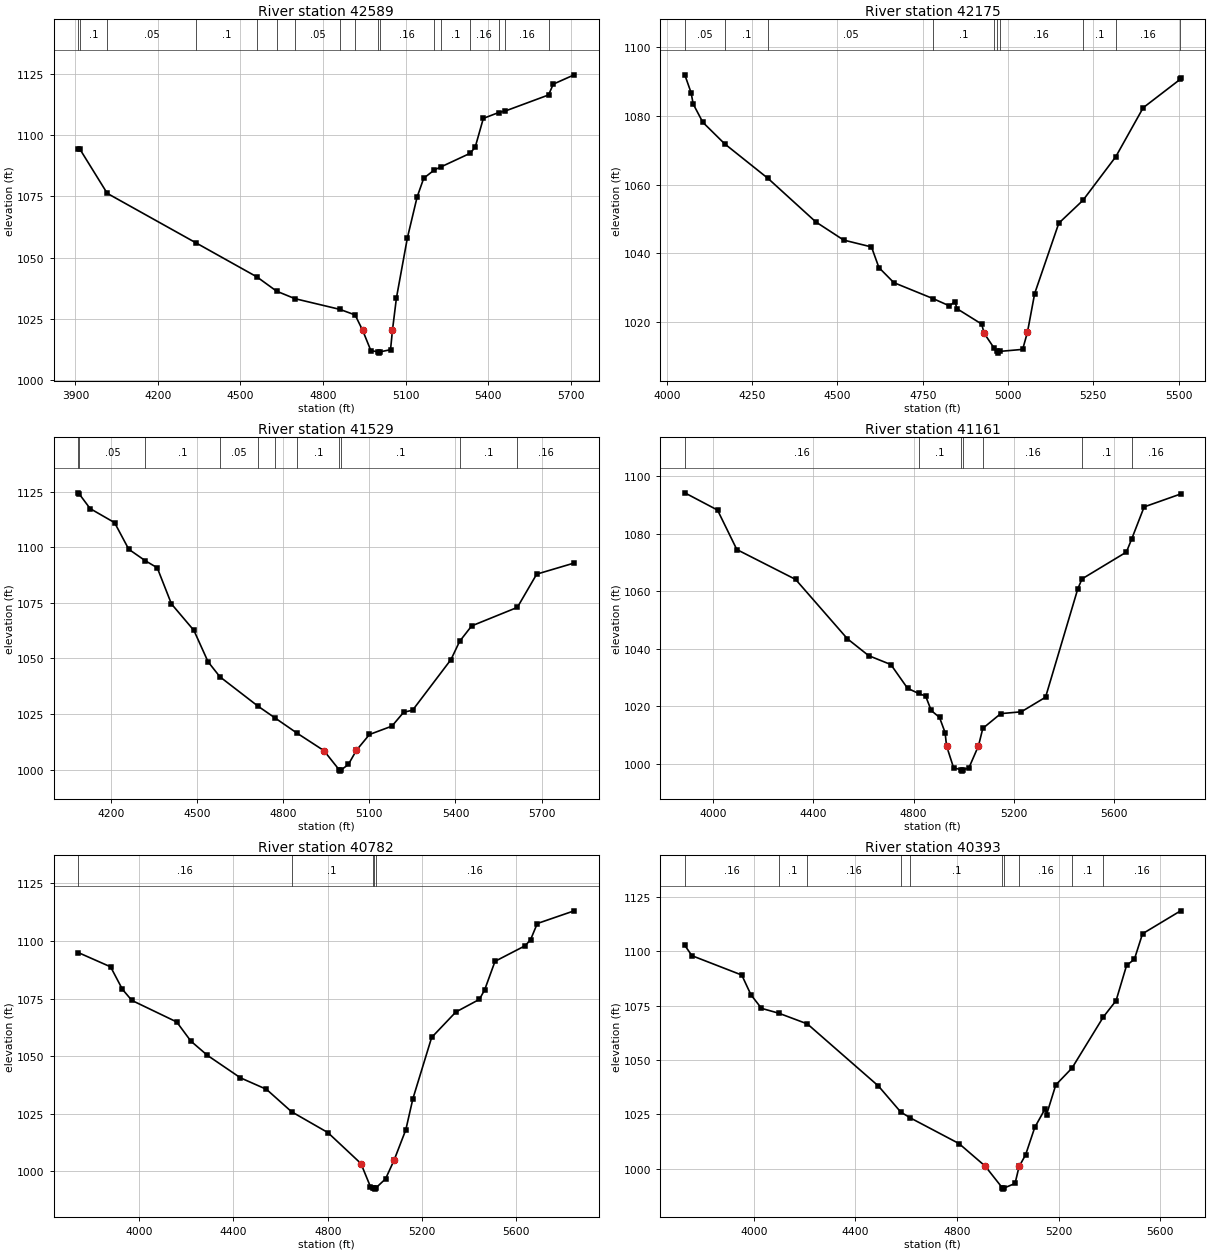
Type RM Length L Ch R = 1 ,42589   ,414,414,414
BEGIN DESCRIPTION:
FLAT CREEK 82.0
END DESCRIPTION:
XS GIS Cut Line= 3
      2954485.44     10061402.93      2955399.43     10061581.02
      2956209.21     10061900.23
#Sta/Elev= 30
  3910.8 1094.32  3916.2 1094.25  4015.9  1076.2  4337.2 1056.11  4559.9 1042.16
  4631.3 1036.36  4698.2  1033.3  4861.1 1028.95  4916.4 1026.69  4943.9 1020.41
  4973.7 1012.16  5000.4 1011.63  5003.2 1011.13  5006.4 1011.63  5045.2 1012.53
  5052.2  1020.5  5066.7 1033.66  5106.4 1058.05  5141.9 1074.76  5165.9 1082.39
  5204.9 1085.77  5229.4 1087.03  5333.7 1092.48  5352.7 1094.96  5382.4 1106.75
    5438 1109.11    5462 1109.74  5619.4 1116.28  5636.4 1120.68  5712.4 1124.48
#Mann= 17 ,-1 , 0
  3910.8     .05       0  3916.2      .1       0  4015.9     .05       0
  4337.2      .1       0  4559.9     .05       0  4631.3      .1       0
  4698.2     .05       0  4861.1      .1       0  4916.4     .16       0
  5000.4     .07       0  5006.4     .16       0  5204.9     .05       0
  5229.4      .1       0  5333.7     .16       0    5438      .1       0
    5462     .16       0  5619.4      .1       0
Bank Sta=4943.9,5052.2
XS Rating Curve= 0 ,0
Exp/Cntr=0.3,0.1

Type RM Length L Ch R = 1 ,42175   ,646,646,646
BEGIN DESCRIPTION:
FLAT CREEK 81.0
END DESCRIPTION:
XS GIS Cut Line= 3
      2954492.14     10061486.92       2955224.7      10061886.8
      2955654.15     10062333.03
#Sta/Elev= 30
  4052.3 1091.94  4070.9  1086.7  4076.8 1083.47  4105.1 1078.13    4169 1071.87
  4296.4 1061.78  4436.5 1049.12  4518.1 1043.84  4599.7 1041.84  4621.5 1035.83
  4665.2 1031.45  4781.2 1026.76  4828.4 1024.68  4844.5 1025.95  4850.2 1023.88
  4922.9 1019.38  4929.8 1016.76  4959.7 1012.32  4969.2 1011.43    4972 1010.93
  4975.2 1011.43    5043 1012.02  5057.1 1017.04  5078.2 1028.27    5149 1048.76
  5219.6 1055.39  5316.1 1068.11  5396.5 1082.37  5504.4 1090.59  5506.2 1090.88
#Mann= 10 ,-1 , 0
  4052.3     .05       0    4169      .1       0  4296.4     .05       0
  4781.2      .1       0  4959.7     .16       0  4969.2     .07       0
  4975.2     .16       0  5219.6      .1       0  5316.1     .16       0
  5504.4      .1       0
Bank Sta=4929.8,5057.1
XS Rating Curve= 0 ,0
Exp/Cntr=0.3,0.1

Type RM Length L Ch R = 1 ,41529   ,368,368,368
BEGIN DESCRIPTION:
FLAT CREEK 80.0
END DESCRIPTION:
XS GIS Cut Line= 3
      2954135.99     10061628.07      2954811.39     10062353.87
      2955525.28      10062524.8
#Sta/Elev= 30
  4087.5 1124.45  4091.3 1123.82  4128.6 1117.36  4213.6 1111.05    4263 1099.08
  4321.2 1093.87  4362.1 1090.77  4411.5 1074.52  4489.7 1062.61    4539  1048.5
  4580.2 1041.76  4712.3  1028.6  4770.2 1023.43  4849.1 1016.39  4942.1 1008.58
  4995.8  999.86  4998.5  999.36  5001.8  999.86  5027.1 1002.34  5055.4 1008.75
  5100.7 1015.83  5178.8 1019.59  5219.9 1025.85  5250.7 1026.73  5384.4 1049.52
  5414.5 1057.71  5456.4 1064.64  5615.3 1072.96  5682.6  1087.9    5813 1092.89
#Mann= 11 ,-1 , 0
  4087.5      .1       0  4091.3     .05       0  4321.2      .1       0
  4580.2     .05       0  4712.3      .1       0  4770.2     .05       0
  4849.1      .1       0  4995.8     .07       0  5001.8      .1       0
  5414.5      .1       0  5615.3     .16       0
Bank Sta=4942.1,5055.4
XS Rating Curve= 0 ,0
Exp/Cntr=0.3,0.1

Type RM Length L Ch R = 1 ,41161   ,379,379,379
BEGIN DESCRIPTION:
FLAT CREEK 79.0
END DESCRIPTION:
XS GIS Cut Line= 4
      2953618.47     10062837.75      2954428.32     10062763.82
      2954939.08     10062501.72       2955522.4     10062588.88
#Sta/Elev= 30
  3887.9 1094.26  4018.4 1088.26  4095.4 1074.52  4329.7 1064.13  4536.3 1043.47
  4620.9 1037.61  4709.6  1034.5  4776.2 1026.24  4819.8 1024.47  4848.3 1023.52
  4870.5 1018.52  4903.6  1016.1  4925.9 1010.81  4931.5 1006.22  4959.8  998.56
  4989.4  997.92  4992.2  997.42  4995.4  997.92  5020.3  998.46    5059 1006.23
  5076.2  1012.3  5147.8 1017.43  5229.6 1018.06  5326.4 1023.14  5454.8  1060.8
  5471.8 1064.31  5648.7 1073.64    5670 1078.22  5719.5 1089.36    5865 1093.85
#Mann= 7 ,-1 , 0
  3887.9     .16       0  4819.8      .1       0  4989.4     .07       0
  4995.4      .1       0  5076.2     .16       0  5471.8      .1       0
    5670     .16       0
Bank Sta=4931.5,5059
XS Rating Curve= 0 ,0
Exp/Cntr=0.3,0.1

Type RM Length L Ch R = 1 ,40782   ,389,389,389
BEGIN DESCRIPTION:
FLAT CREEK 78.0
END DESCRIPTION:
XS GIS Cut Line= 3
      2953621.92     10062874.71      2955097.01     10062958.71
      2955661.49     10063227.51
#Sta/Elev= 30
  3742.1 1094.91  3878.9 1088.74    3929 1078.99    3969 1074.18  4159.3 1064.83
  4219.4 1056.52  4289.5 1050.35  4429.8 1040.59  4539.9 1035.62  4646.3  1025.9
  4800.4 1016.85  4940.6 1003.43  4980.7  993.42  4990.5   992.9  4997.7  992.83
  5000.4  992.33  5003.7  992.83  5044.9  996.77  5080.8 1004.79  5130.9 1018.07
  5160.9 1031.54  5240.4 1058.11    5343 1069.14  5442.7 1074.62  5464.9 1078.66
  5509.2 1091.13  5637.4 1097.91  5660.1 1100.55  5688.4 1107.52  5844.8 1113.03
#Mann= 5 ,-1 , 0
  3742.1     .16       0  4646.3      .1       0  4990.5     .16       0
  4997.7     .07       0  5003.7     .16       0
Bank Sta=4940.6,5080.8
XS Rating Curve= 0 ,0
Exp/Cntr=0.3,0.1

Type RM Length L Ch R = 1 ,40393   ,568,568,568
BEGIN DESCRIPTION:
FLAT CREEK 77.0
END DESCRIPTION:
XS GIS Cut Line= 2
      2953551.34     10063015.84      2955444.98     10063485.89
#Sta/Elev= 30
  3728.8 1102.65  3756.7 1097.91    3953 1089.01  3989.2 1079.92  4030.6 1073.72
  4099.1 1071.47    4211 1066.58  4490.7 1038.06  4578.8 1026.08  4616.7 1023.39
  4807.7 1011.64  4910.7 1001.29  4978.9  991.21  4981.6  990.71  4984.9  991.21
  5028.4  993.32    5044 1000.98  5044.7 1001.18  5069.8 1006.44    5106 1019.07
  5147.3 1027.72  5152.5 1024.97  5188.7 1038.57  5252.5  1046.3    5376  1069.8
  5425.9 1077.26  5467.1  1093.4    5498 1096.28  5529.9 1107.97  5679.9  1118.5
#Mann= 10 ,-1 , 0
  3728.8     .16       0  4099.1      .1       0    4211     .16       0
  4578.8     .05       0  4616.7      .1       0  4978.9     .07       0
  4984.9      .1       0    5044     .16       0  5252.5      .1       0
    5376     .16       0
Bank Sta=4910.7,5044.7
XS Rating Curve= 0 ,0
Exp/Cntr=0.3,0.1

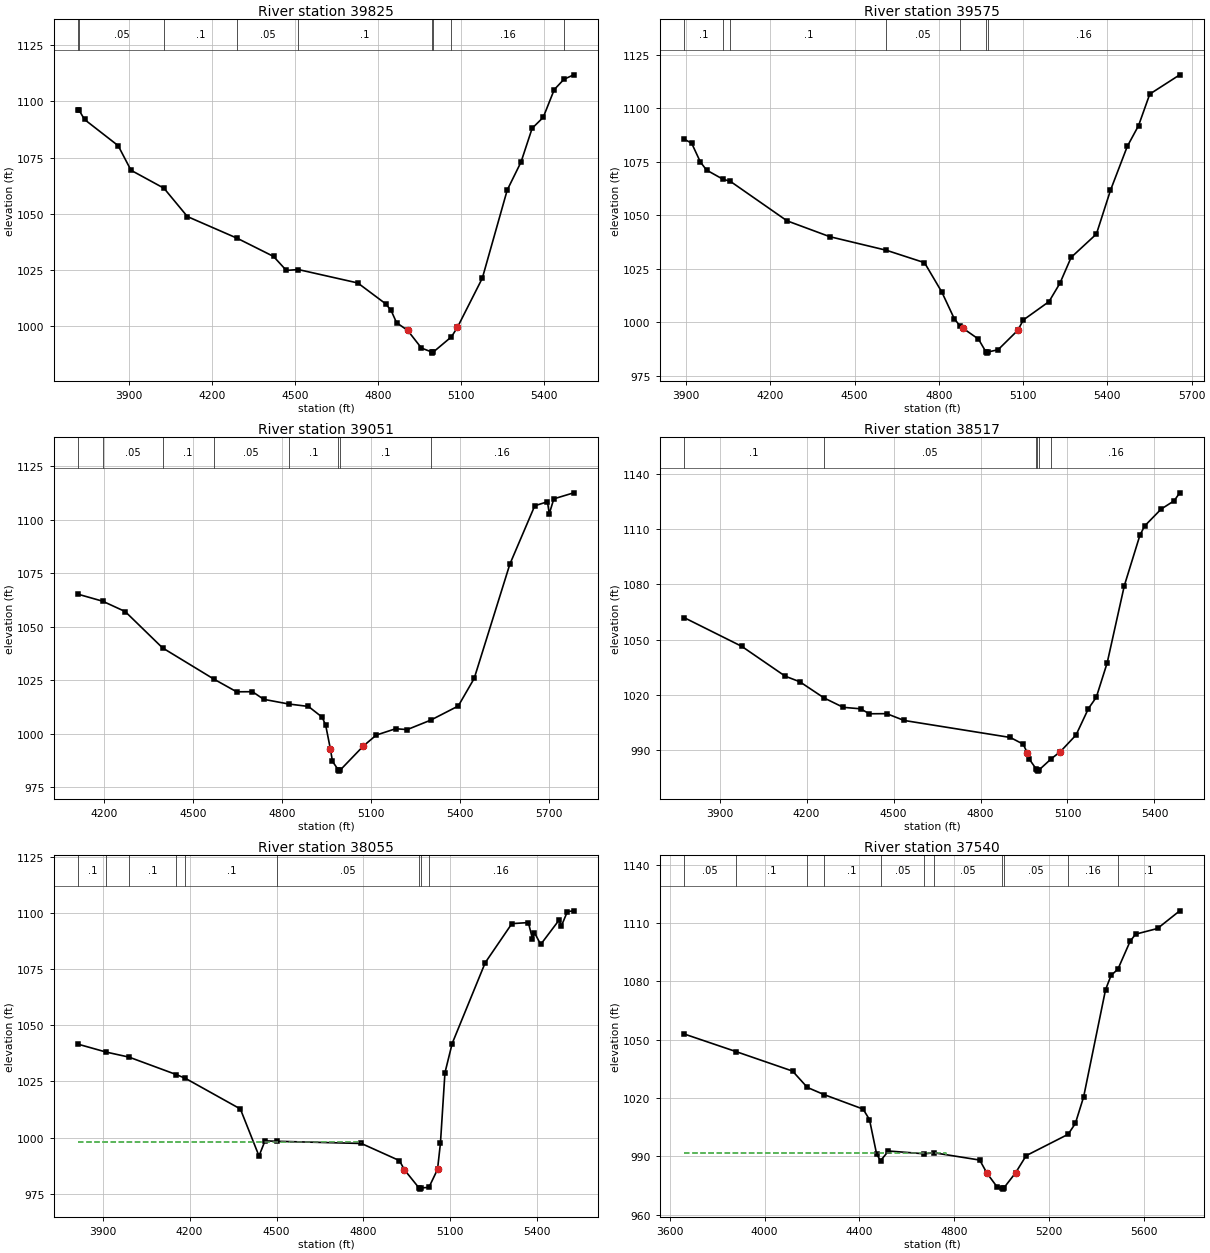
Type RM Length L Ch R = 1 ,39825   ,250,250,250
BEGIN DESCRIPTION:
FLAT CREEK 76.0
END DESCRIPTION:
XS GIS Cut Line= 3
      2953598.39     10064265.82      2954441.77     10063889.49
      2955308.73     10063876.05
#Sta/Elev= 30
  3715.5  1096.2  3717.7  1096.2  3737.9 1091.96  3859.5 1080.33  3905.9  1069.4
  4025.1 1061.41  4109.8 1048.82  4290.5 1039.14    4421 1031.11  4467.4 1024.89
  4510.7 1025.27  4725.7 1019.31  4825.8  1010.1  4845.8 1007.16  4865.8 1001.65
  4905.8  998.24  4955.8  990.37  4992.8  988.63  4995.5  988.13  4998.8  988.63
  5064.2  995.38  5085.8  999.59  5175.8 1021.45  5265.8 1060.62  5315.8  1073.1
  5355.8 1088.05  5395.8 1092.89  5435.8 1105.26    5471 1109.85  5506.1 1111.81
#Mann= 9 ,-1 , 0
  3715.5      .1       0  3717.7     .05       0  4025.1      .1       0
  4290.5     .05       0  4510.7      .1       0  4992.8     .07       0
  4998.8      .1       0  5064.2     .16       0    5471      .1       0
Bank Sta=4905.8,5085.8
XS Rating Curve= 0 ,0
Exp/Cntr=0.3,0.1

Type RM Length L Ch R = 1 ,39575   ,524,524,524
BEGIN DESCRIPTION:
FLAT CREEK 75.0
END DESCRIPTION:
XS GIS Cut Line= 3
      2953806.66     10064568.26      2954740.82     10064134.78
      2955475.09     10064118.02
#Sta/Elev= 30
  3893.3 1085.58  3919.4 1083.73  3950.4 1074.95  3972.5 1071.16  4031.1 1066.86
  4056.9 1065.92  4259.1 1047.43  4411.4 1040.02  4612.9 1033.67  4748.6 1027.87
  4810.3 1014.14  4854.4 1001.76  4875.5  998.18    4886  997.17  4940.8  992.15
  4967.8  986.08  4970.5  985.58  4973.8  986.08  5010.8  987.17  5080.8  996.24
  5100.8  1001.1  5192.1 1009.67  5230.9 1018.23  5270.9 1030.35  5360.9 1041.26
  5410.9 1061.68  5470.9 1082.25  5510.9 1091.93  5550.9 1106.69  5657.6 1115.69
#Mann= 7 ,-1 , 0
  3893.3      .1       0  4031.1     .05       0  4056.9      .1       0
  4612.9     .05       0  4875.5      .1       0  4967.8     .07       0
  4973.8     .16       0
Bank Sta=4886,5080.8
XS Rating Curve= 0 ,0
Exp/Cntr=0.3,0.1

Type RM Length L Ch R = 1 ,39051   ,534,534,534
BEGIN DESCRIPTION:
FLAT CREEK 74.0
END DESCRIPTION:
XS GIS Cut Line= 4
      2954162.89     10064910.99      2954824.83     10064793.39
      2955016.36     10064464.09      2955590.97     10064238.95
#Sta/Elev= 30
  4113.2  1065.1  4195.2 1061.87  4271.2 1057.03  4397.1 1040.05  4570.5 1025.42
    4647  1019.5  4700.3 1019.55  4738.4 1015.98  4822.4  1013.8  4889.2 1012.65
  4935.5 1007.62  4947.4  1003.8  4963.1  992.79  4970.2  986.96  4990.3  982.91
  4993.1  982.41  4996.3  982.91  5074.3  994.15  5117.9  999.27    5183 1002.22
  5222.4 1001.84  5301.9 1006.28  5394.3 1012.86    5448 1025.75  5568.2 1079.16
  5652.3  1106.5    5695 1108.35  5701.2 1102.74  5716.5 1109.73  5783.6 1112.54
#Mann= 8 ,-1 , 0
  4113.2      .1       0  4195.2     .05       0  4397.1      .1       0
  4570.5     .05       0  4822.4      .1       0  4990.3     .07       0
  4996.3      .1       0  5301.9     .16       0
Bank Sta=4963.1,5074.3
XS Rating Curve= 0 ,0
Exp/Cntr=0.3,0.1

Type RM Length L Ch R = 1 ,38517   ,462,462,462
BEGIN DESCRIPTION:
FLAT CREEK 73.0
END DESCRIPTION:
XS GIS Cut Line= 4
      2954270.36     10065008.44      2955281.82     10065025.24
      2955469.99     10064753.06      2955819.43     10064642.18
#Sta/Elev= 30
  3778.1 1061.83  3976.2 1046.31  4126.3 1030.12  4176.3 1027.13  4260.3 1018.33
  4326.3 1013.25  4386.3 1012.45  4416.3 1009.76  4476.3 1009.82  4536.3 1006.14
  4902.6  996.92  4947.2  993.29  4961.7  988.44  4968.1  985.19  4992.6  979.69
  4994.9  979.17  4997.6  978.67  5000.9  979.17    5044  985.37  5075.6  989.26
  5129.5  998.25  5172.3 1012.61  5199.4 1018.71  5236.9 1037.36  5296.2 1079.27
  5349.8 1106.51    5366 1111.53  5423.2 1120.73    5468 1125.22  5487.2 1129.53
#Mann= 6 ,-1 , 0
  3778.1      .1       0  4260.3     .05       0  4992.6      .1       0
  4994.9     .07       0  5000.9      .1       0    5044     .16       0
Bank Sta=4961.7,5075.6
XS Rating Curve= 0 ,0
Exp/Cntr=0.3,0.1

Type RM Length L Ch R = 1 ,38055   ,515,515,515
BEGIN DESCRIPTION:
FLAT CREEK 72.0
END DESCRIPTION:
XS GIS Cut Line= 4
      2954723.45     10065802.42       2955487.3     10065212.17
       2955843.2     10065160.08      2956129.69     10064903.98
#Sta/Elev= 30
  3816.1 1041.59  3912.3  1038.1  3991.3 1035.85  4153.6  1028.1  4185.2 1026.43
  4375.2 1012.75  4439.5   991.8  4460.3  998.54  4502.6  998.34  4792.7  997.37
  4924.1  989.73  4941.3  985.63  4991.8  977.52  4994.6  977.02  4997.8  977.52
  5025.9  977.82  5055.5  985.82  5065.6  997.56  5081.1 1028.88    5106 1041.92
  5220.1 1077.95    5312 1095.35  5368.9 1095.83  5383.1 1088.57  5389.8 1091.35
  5411.5 1086.08    5475 1096.95  5482.5 1094.19  5503.4 1100.69  5525.4 1101.06
#Mann= 9 ,-1 , 0
  3816.1      .1       0  3912.3     .05       0  3991.3      .1       0
  4153.6     .05       0  4185.2      .1       0  4502.6     .05       0
  4991.8    .035       0  4997.8     .05       0  5025.9     .16       0
#XS Ineff= 2 , 0
         4792.05  998.05
Permanent Ineff=
       T       T
Bank Sta=4941.3,5055.5
XS Rating Curve= 0 ,0
Exp/Cntr=0.3,0.1

Type RM Length L Ch R = 1 ,37540   ,468,468,468
BEGIN DESCRIPTION:
FLAT CREEK 71.0
END DESCRIPTION:
XS GIS Cut Line= 4
       2954753.8     10066158.34      2955361.43      10065711.3
      2955830.18     10065676.58      2956620.11     10065320.68
#Sta/Elev= 30
  3660.9 1052.94  3880.2 1043.86  4117.8 1033.86  4180.1 1025.45  4250.1 1021.78
  4415.3  1014.3  4442.4 1008.88  4472.5  991.12    4489  987.74  4522.6  992.71
  4674.5  991.27  4714.7   991.8  4907.6  988.05  4938.3  981.24  4982.5  973.97
  5002.7  973.58  5005.4  973.08  5008.7  973.58  5058.9  981.47  5103.7  990.32
  5280.7 1001.31  5311.2  1006.9  5346.1 1020.57  5438.6 1075.75  5461.8 1083.11
  5490.8 1086.35  5542.2 1100.66  5565.3 1104.36  5657.9 1107.29  5751.7 1116.39
#Mann= 11 ,-1 , 0
  3660.9     .05       0  3880.2      .1       0  4180.1     .05       0
  4250.1      .1       0    4489     .05       0  4674.5      .1       0
  4714.7     .05       0  5002.7    .035       0  5008.7     .05       0
  5280.7     .16       0  5490.8      .1       0
#XS Ineff= 2 , 0
         4765.62  991.44
Permanent Ineff=
       T       T
Bank Sta=4938.3,5058.9
XS Rating Curve= 0 ,0
Exp/Cntr=0.3,0.1