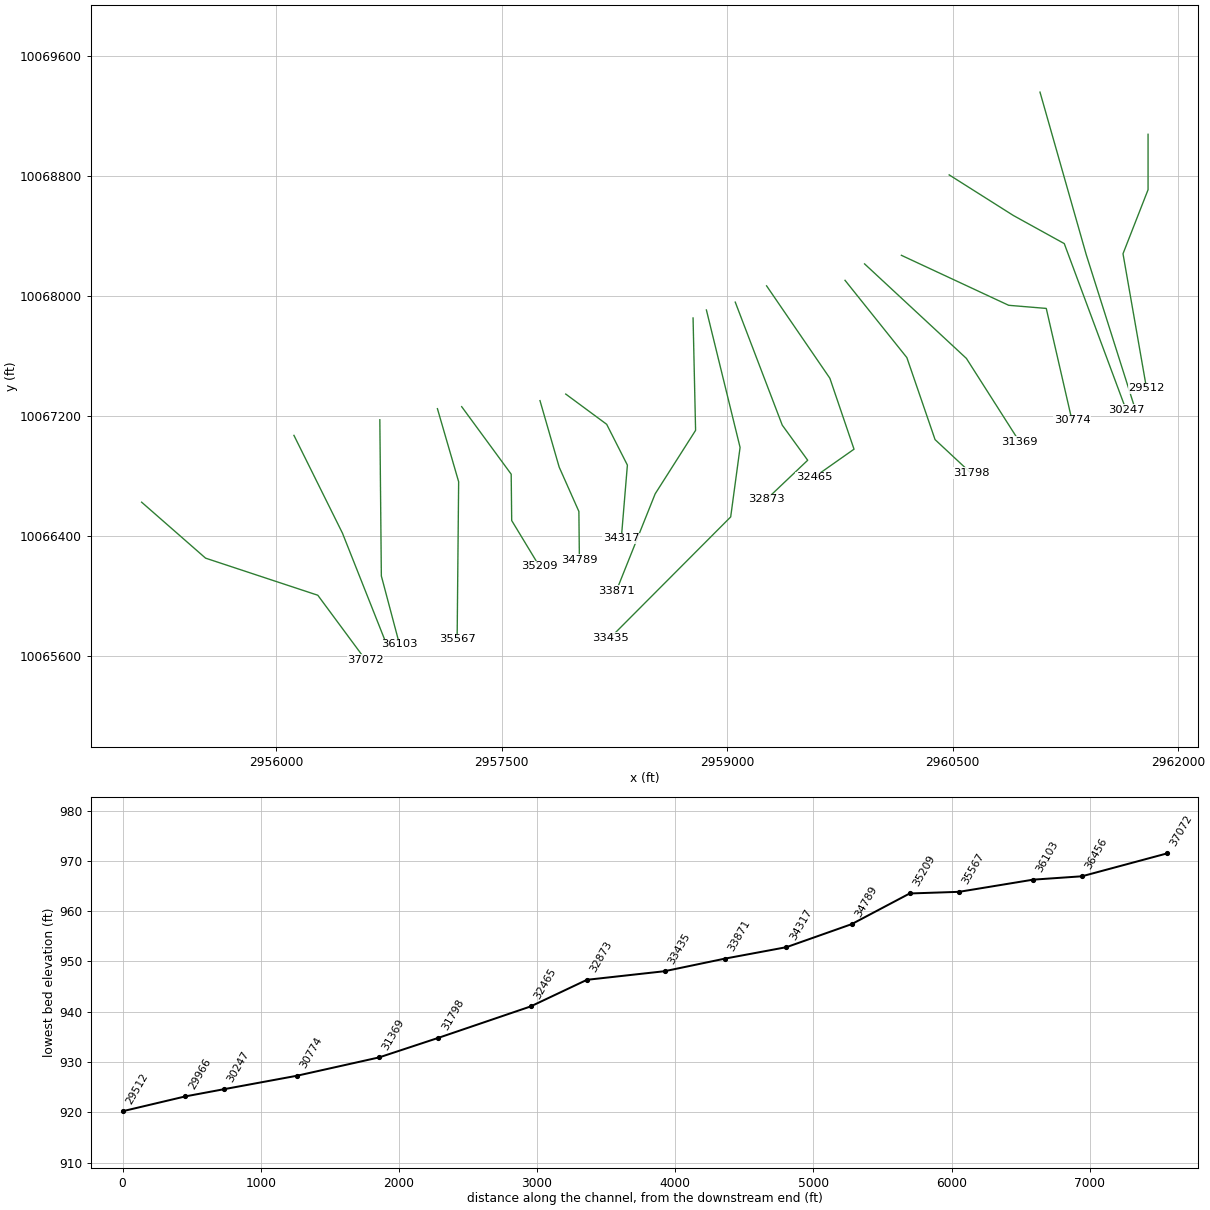
HEC-RAS study FLAT CREEK.prj: FLAT CREEK Base Level Engineering

--- FLAT CREEK.g01 (geometry) --- (continued)

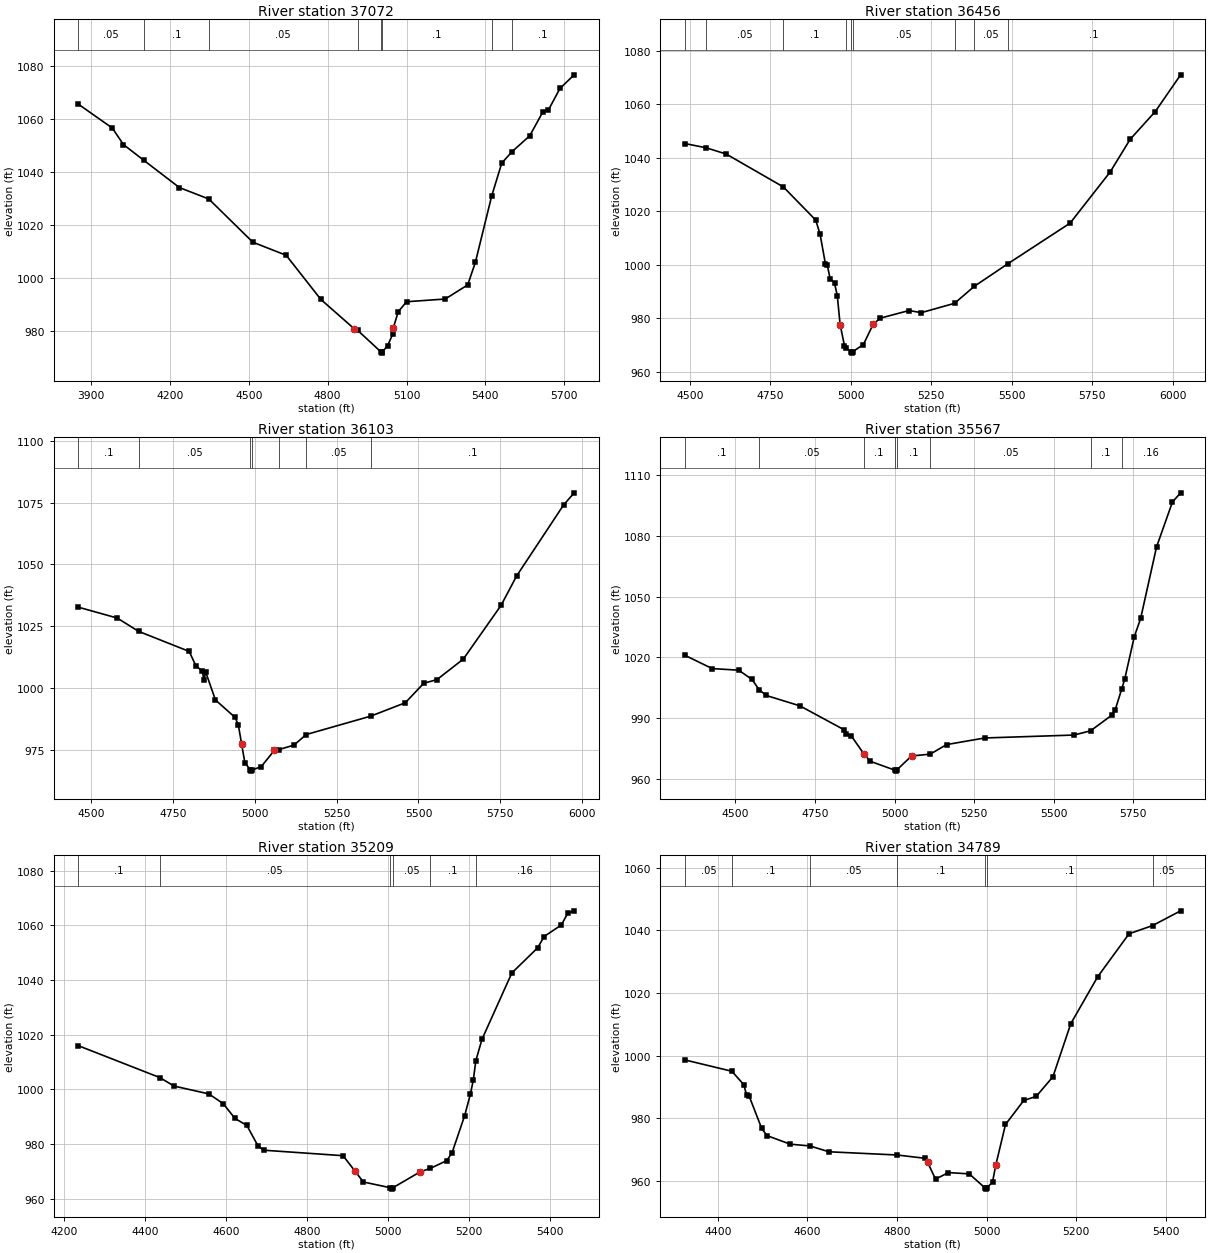
Type RM Length L Ch R = 1 ,37072   ,616,616,616
BEGIN DESCRIPTION:
FLAT CREEK 70.0
END DESCRIPTION:
XS GIS Cut Line= 4
      2955105.33     10066622.78       2955530.7     10066249.49
      2956277.23      10066002.1      2956593.74     10065572.86
#Sta/Elev= 30
  3851.8  1065.6  3980.8 1056.59  4023.5 1050.32  4101.2 1044.35    4236 1034.08
  4347.9 1029.76  4515.5 1013.42  4642.3 1008.47  4774.3  991.77  4901.1  980.69
  4914.4  980.08  5002.3  971.99  5005.1  971.49  5008.3  971.99  5027.9  974.28
  5047.5  978.66 5049.72  981.03  5068.5  987.16  5100.1  990.92    5247  991.94
  5332.6  997.28  5361.9 1005.84  5423.6  1030.8  5462.1 1043.33  5501.2 1047.63
  5568.6 1053.65  5618.7 1062.74  5639.6 1063.39  5683.5 1071.54  5737.5 1076.69
#Mann= 8 ,-1 , 0
  3851.8     .05       0  4101.2      .1       0  4347.9     .05       0
  4914.4      .1       0  5002.3     .07       0  5008.3      .1       0
  5423.6     .16       0  5501.2      .1       0
Bank Sta=4901.1,5049.72
XS Rating Curve= 0 ,0
Exp/Cntr=0.3,0.1

Type RM Length L Ch R = 1 ,36456   ,353,353,353
BEGIN DESCRIPTION:
FLAT CREEK 69.0
END DESCRIPTION:
XS GIS Cut Line= 3
      2956118.49     10067068.29      2956441.09     10066416.37
      2956740.14     10065660.34
#Sta/Elev= 30
    4484 1045.26  4550.8 1043.65  4612.7 1041.33  4790.2 1029.04  4890.8 1016.64
  4904.3 1011.36  4921.1 1000.13  4926.7  999.83  4935.4  994.82  4949.1  993.12
  4957.7  988.45 4966.59  977.57    4980  969.75    4986  968.96  4999.3  967.44
  5002.1  966.94  5005.3  967.44  5038.9  970.15  5069.3  977.77  5091.6  980.02
  5180.8  982.86  5218.7  982.06    5322  985.55  5383.2  991.88  5487.2  1000.3
    5681 1015.51  5805.7 1034.66  5867.6 1046.84  5945.5 1057.19  6024.4 1070.93
#Mann= 9 ,-1 , 0
    4484      .1       0  4550.8     .05       0  4790.2      .1       0
    4986     .05       0  4999.3    .035       0  5005.3     .05       0
    5322      .1       0  5383.2     .05       0  5487.2      .1       0
#XS Ineff= 2 , 0
                         5181.36          982.83
Permanent Ineff=
       T       T
Bank Sta=4966.59,5069.3
XS Rating Curve= 0 ,0
Exp/Cntr=0.3,0.1

Type RM Length L Ch R = 1 ,36103   ,536,536,536
BEGIN DESCRIPTION:
FLAT CREEK 68.0
END DESCRIPTION:
XS GIS Cut Line= 3
      2956689.75     10067172.39      2956699.83     10066130.75
      2956820.79     10065673.78
#Sta/Elev= 30
  4461.2 1032.66  4579.9 1028.27  4645.1 1022.88  4799.9 1014.74  4819.9 1008.99
  4839.9 1006.75    4845    1003    4850 1006.47  4879.9   995.1  4939.9  988.02
  4949.9     985  4959.9  977.25  4969.9  969.64  4986.9  966.77  4989.6  966.27
  4992.9  966.77  5019.9  968.11  5059.9  974.68  5074.5  975.01  5119.9  976.82
  5157.3  981.09  5354.1  988.53  5459.9  993.96  5516.2 1001.85  5556.4 1003.32
  5636.9 1011.62  5752.4 1033.41  5799.8 1045.29  5943.2 1074.03  5975.6 1078.97
#Mann= 7 ,-1 , 0
  4461.2      .1       0  4645.1     .05       0  4986.9    .035       0
  4992.9     .05       0  5074.5      .1       0  5157.3     .05       0
  5354.1      .1       0
Bank Sta=4959.9,5059.9
XS Rating Curve= 0 ,0
Exp/Cntr=0.3,0.1

Type RM Length L Ch R = 1 ,35567   ,358,358,358
BEGIN DESCRIPTION:
FLAT CREEK 67.0
END DESCRIPTION:
XS GIS Cut Line= 3
       2957072.8     10067246.39      2957213.94     10066759.11
      2957203.87     10065708.07
#Sta/Elev= 30
  4340.7 1021.07  4426.8 1014.47    4510 1013.69  4551.7 1009.15  4574.3 1004.07
  4596.6 1001.21  4702.6  996.07  4842.1  984.21  4847.1  982.05  4863.4  981.37
  4903.2  972.42  4923.4  968.72  5000.4  964.35  5003.1  963.85  5006.4  964.35
  5053.4  971.32  5112.3  972.24  5163.4  976.95  5283.4  980.22  5563.4  981.66
  5615.9  983.74  5683.4  991.54  5693.4  994.14  5714.3 1004.53  5723.4  1009.3
  5753.4 1030.19  5773.4 1039.23  5823.4 1074.51  5873.4 1096.73  5899.1 1101.25
#Mann= 8 ,-1 , 0
  4340.7      .1       0  4574.3     .05       0  4903.2      .1       0
  5000.4     .07       0  5006.4      .1       0  5112.3     .05       0
  5615.9      .1       0  5714.3     .16       0
Bank Sta=4903.2,5053.4
XS Rating Curve= 0 ,0
Exp/Cntr=0.3,0.1

Type RM Length L Ch R = 1 ,35209   ,420,420,420
BEGIN DESCRIPTION:
FLAT CREEK 66.0
END DESCRIPTION:
XS GIS Cut Line= 4
      2957234.13     10067259.75      2957563.41     10066809.52
      2957566.77     10066500.38      2957751.56     10066194.63
#Sta/Elev= 30
  4234.6 1016.01    4436 1004.33  4470.9 1001.23  4556.6  998.38  4592.2  994.83
  4621.5  989.37  4650.8  986.81  4677.9  979.42  4692.5  977.76  4888.2  975.76
  4918.2  970.02  4938.2  966.14  5005.2  964.02  5007.9  963.52  5011.2  964.02
  5078.2  969.82  5103.9  971.12  5144.4  973.97  5157.5  976.91  5188.5  990.43
  5202.8  998.38  5209.9 1003.56    5216 1010.49  5231.2 1018.34    5305 1042.64
    5369 1051.87  5384.5 1055.94  5427.2 1060.19  5442.7  1064.4  5458.8 1065.36
#Mann= 6 ,-1 , 0
  4234.6      .1       0    4436     .05       0  5005.2    .035       0
  5011.2     .05       0  5103.9      .1       0    5216     .16       0
Bank Sta=4918.2,5078.2
XS Rating Curve= 0 ,0
Exp/Cntr=0.3,0.1

Type RM Length L Ch R = 1 ,34789   ,472,472,472
BEGIN DESCRIPTION:
FLAT CREEK 65.0
END DESCRIPTION:
XS GIS Cut Line= 4
      2957754.94     10067300.08      2957882.63     10066856.56
      2958013.67     10066560.86      2958017.03     10066238.55
#Sta/Elev= 30
  4326.2  998.67  4431.3  995.05  4457.7  990.81  4464.2  987.52  4469.4   987.3
  4497.8  976.84  4509.7   974.5  4561.7  971.77  4605.5  971.21  4648.2  969.34
  4800.7  968.31  4862.9  967.26  4868.4  965.97  4886.2  960.61  4914.9   962.7
  4961.5  962.29  4995.7  957.92  4998.4  957.42  5001.7  957.92  5013.5  959.71
  5020.5  964.97  5042.4  978.06  5083.3  985.74  5110.9  987.01  5148.3  993.29
  5188.3 1010.27  5248.3 1025.22  5318.3 1038.93  5371.1 1041.57  5433.5 1046.26
#Mann= 7 ,-1 , 0
  4326.2     .05       0  4431.3      .1       0  4605.5     .05       0
  4800.7      .1       0  4995.7     .07       0  5001.7      .1       0
  5371.1     .05       0
Bank Sta=4868.4,5020.5
XS Rating Curve= 0 ,0
Exp/Cntr=0.3,0.1

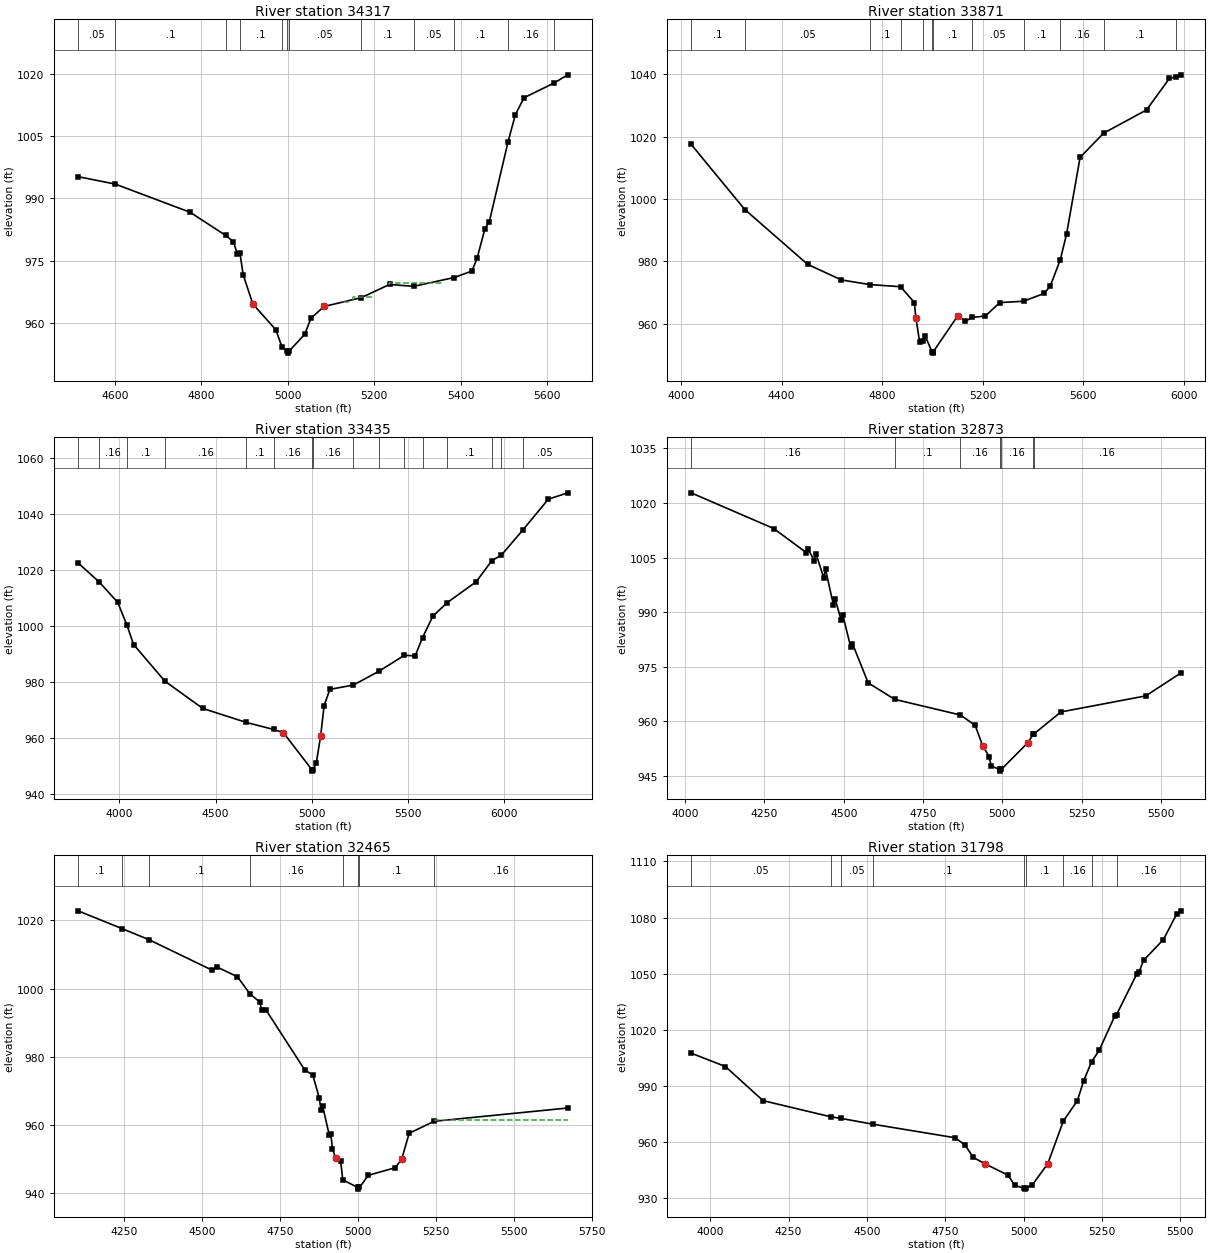
Type RM Length L Ch R = 1 ,34317   ,446,446,446
BEGIN DESCRIPTION:
FLAT CREEK 64.0
END DESCRIPTION:
XS GIS Cut Line= 4
      2957926.32     10067343.78      2958198.49     10067142.18
      2958336.26       10066870.      2958295.93     10066382.73
#Sta/Elev= 30
  4515.1  995.24  4600.8  993.47  4774.2  986.69  4856.6  981.12  4874.5  979.62
  4883.5  976.65  4889.5  976.95  4896.9  971.71  4919.3  964.65  4972.6  958.44
  4986.6  954.35  4997.5  953.34  5000.3  952.84  5003.5  953.34  5039.5  957.39
  5053.8  961.24    5084  964.05  5169.6  966.15  5235.4  969.33  5291.3  968.89
  5385.2  971.01    5426  972.56  5438.1  975.68  5456.1  982.75  5466.2  984.42
  5509.5 1003.59  5526.4 1010.12  5546.5 1014.21  5614.8 1017.68  5647.8 1019.71
#Mann= 12 ,-1 , 0
  4515.1     .05       0  4600.8      .1       0  4856.6     .05       0
  4889.5      .1       0  4986.6     .05       0  4997.5    .035       0
  5003.5     .05       0  5169.6      .1       0  5291.3     .05       0
  5385.2      .1       0  5509.5     .16       0  5614.8      .1       0
#XS Ineff= 3 ,-1
 5128.64 5146.81  965.18 5151.09 5195.77  966.42 5235.23 5358.52  969.71
Permanent Ineff=
       T       T       T
Bank Sta=4919.3,5084
XS Rating Curve= 0 ,0
Exp/Cntr=0.3,0.1

Type RM Length L Ch R = 1 ,33871   ,436,436,436
BEGIN DESCRIPTION:
FLAT CREEK 63.0
END DESCRIPTION:
XS GIS Cut Line= 4
      2958773.08     10067851.18      2958789.88     10067101.85
      2958521.07     10066678.47      2958262.91      10066031.4
#Sta/Elev= 30
  4040.6 1017.48    4254   996.6  4503.5  979.04  4638.2  974.02  4751.8  972.53
  4873.5  971.85  4928.4  966.78  4934.3  961.85  4949.6     954  4963.7  954.29
  4970.7  956.17  4998.1  951.06  5000.9  950.56  5004.1  951.06  5101.2  962.58
  5131.4  960.78  5158.3  961.99  5210.5  962.47  5268.1  966.75  5362.5   967.2
  5444.6   969.7  5468.8  972.06  5508.7  980.52  5533.6  988.75  5587.4 1013.32
  5681.2 1021.09  5851.5 1028.51  5942.7 1038.64  5969.6 1039.12  5988.3 1039.77
#Mann= 12 ,-1 , 0
  4040.6      .1       0    4254     .05       0  4751.8      .1       0
  4873.5     .05       0  4963.7      .1       0  4998.1     .07       0
  5004.1      .1       0  5158.3     .05       0  5362.5      .1       0
  5508.7     .16       0  5681.2      .1       0  5969.6     .05       0
Bank Sta=4934.3,5101.2
XS Rating Curve= 0 ,0
Exp/Cntr=0.3,0.1

Type RM Length L Ch R = 1 ,33435   ,562,562,562
BEGIN DESCRIPTION:
FLAT CREEK 62.0
END DESCRIPTION:
XS GIS Cut Line= 4
      2958861.82     10067904.58      2959085.77     10066987.95
      2959023.27     10066524.41      2958221.21     10065717.14
#Sta/Elev= 30
  3784.4 1022.44  3895.4 1015.56  3991.2 1008.31  4039.2 1000.16  4073.5  993.28
  4237.1  980.15  4433.8  970.45  4660.4  965.44  4802.8  962.94  4853.3  961.79
  5001.7  948.56  5004.4  948.06  5007.7  948.56  5024.9   951.1  5047.4  960.77
  5065.2  971.49  5095.5  977.28  5216.9  978.79  5349.1  983.67  5483.4  989.45
    5539  989.19  5577.6  995.77    5631 1003.39  5704.5 1008.17  5857.2 1015.73
  5938.4 1023.28  5986.9 1025.14  6098.1 1034.06    6232 1045.19  6333.7 1047.46
#Mann= 16 ,-1 , 0
  3784.4      .1       0  3895.4     .16       0  4039.2      .1       0
  4237.1     .16       0  4660.4      .1       0  4802.8     .16       0
  5001.7     .07       0  5007.7     .16       0  5216.9      .1       0
  5349.1     .16       0  5483.4      .1       0  5577.6     .05       0
  5704.5      .1       0  5938.4     .05       0  5986.9      .1       0
  6098.1     .05       0
Bank Sta=4853.3,5047.4
XS Rating Curve= 0 ,0
Exp/Cntr=0.3,0.1

Type RM Length L Ch R = 1 ,32873   ,408,408,408
BEGIN DESCRIPTION:
FLAT CREEK 61.0
END DESCRIPTION:
XS GIS Cut Line= 4
       2959053.7     10067957.06      2959366.18     10067136.79
      2959535.45     10066902.42      2959262.73     10066642.68
#Sta/Elev= 30
    4019 1022.82  4279.4 1013.01  4382.3 1006.37  4387.6 1007.35    4407 1004.22
  4412.4 1006.05  4437.1  999.46  4442.5 1001.79  4467.2  992.11  4472.6  993.73
    4492  987.74  4497.3  989.16  4522.1  980.34  4527.4  981.39  4576.9  970.61
  4660.4  966.07  4867.5  961.78  4914.1  958.92  4937.4  953.39  4958.3  950.31
  4964.4  947.75  4990.8  946.85  4993.6  946.35  4996.8  946.85  5079.7  954.13
    5097  956.45  5098.8  956.53  5184.2  962.61  5451.6  967.02  5562.5  973.33
#Mann= 7 ,-1 , 0
    4019     .16       0  4660.4      .1       0  4867.5     .16       0
  4990.8     .07       0  4996.8     .16       0    5097      .1       0
  5098.8     .16       0
Bank Sta=4937.4,5079.7
XS Rating Curve= 0 ,0
Exp/Cntr=0.3,0.1

Type RM Length L Ch R = 1 ,32465   ,667,667,667
BEGIN DESCRIPTION:
FLAT CREEK 60.0
END DESCRIPTION:
XS GIS Cut Line= 4
      2959262.02     10068065.61      2959683.02     10067449.29
      2959843.61      10066976.2      2959578.87     10066789.58
#Sta/Elev= 30
  4103.2 1022.84  4244.3 1017.61  4330.2 1014.38  4533.3 1005.38  4548.2 1006.34
    4614 1003.48  4654.1  998.44  4685.8  996.04  4691.8  993.73  4706.7  993.55
  4829.3  976.17  4855.9  974.51  4876.6   967.8    4882  964.22  4887.3  965.42
  4908.1  957.06  4913.4  957.38  4918.8  952.79  4929.4  950.12  4944.8  949.38
  4951.8  943.79  4999.3  941.55    5002  941.05  5005.3  941.55  5033.7  945.12
  5119.5  947.33  5140.6  949.86  5164.5  957.46  5244.7  960.99  5673.1  964.89
#Mann= 8 ,-1 , 0
  4103.2      .1       0  4244.3     .05       0  4330.2      .1       0
  4654.1     .16       0  4951.8      .1       0  4999.3     .07       0
  5005.3      .1       0  5244.7     .16       0
#XS Ineff= 2 , 0
                          5246.7          961.28
Permanent Ineff=
       T       T
Bank Sta=4929.4,5140.6
XS Rating Curve= 0 ,0
Exp/Cntr=0.3,0.1

Type RM Length L Ch R = 1 ,31798   ,429,429,429
BEGIN DESCRIPTION:
FLAT CREEK 59.0
END DESCRIPTION:
XS GIS Cut Line= 4
      2959783.72      10068102.5      2960195.15     10067586.91
      2960382.65     10067040.03      2960620.84     10066817.38
#Sta/Elev= 30
  3938.8 1007.51  4048.3 1000.36  4168.4  982.12  4385.9  973.43  4418.9  972.58
  4518.8  969.53  4782.5  962.25  4813.8  958.26  4839.8  951.74  4876.6  948.38
  4950.6  942.28  4971.8  936.89  5000.5  935.31  5003.2  934.81  5006.5  935.31
  5027.4  936.88  5077.5  948.42  5127.4  971.27    5172  982.08  5192.2   992.8
  5217.4 1002.92  5241.6 1008.98  5291.4 1027.38  5297.3 1028.15  5362.2 1050.03
  5369.1 1051.02  5383.2 1057.11  5446.7 1068.25  5489.2 1081.94  5502.6 1083.61
#Mann= 9 ,-1 , 0
  3938.8     .05       0  4385.9      .1       0  4418.9     .05       0
  4518.8      .1       0  5000.5     .07       0  5006.5      .1       0
  5127.4     .16       0  5217.4     .05       0  5297.3     .16       0
Bank Sta=4876.6,5077.5
XS Rating Curve= 0 ,0
Exp/Cntr=0.3,0.1

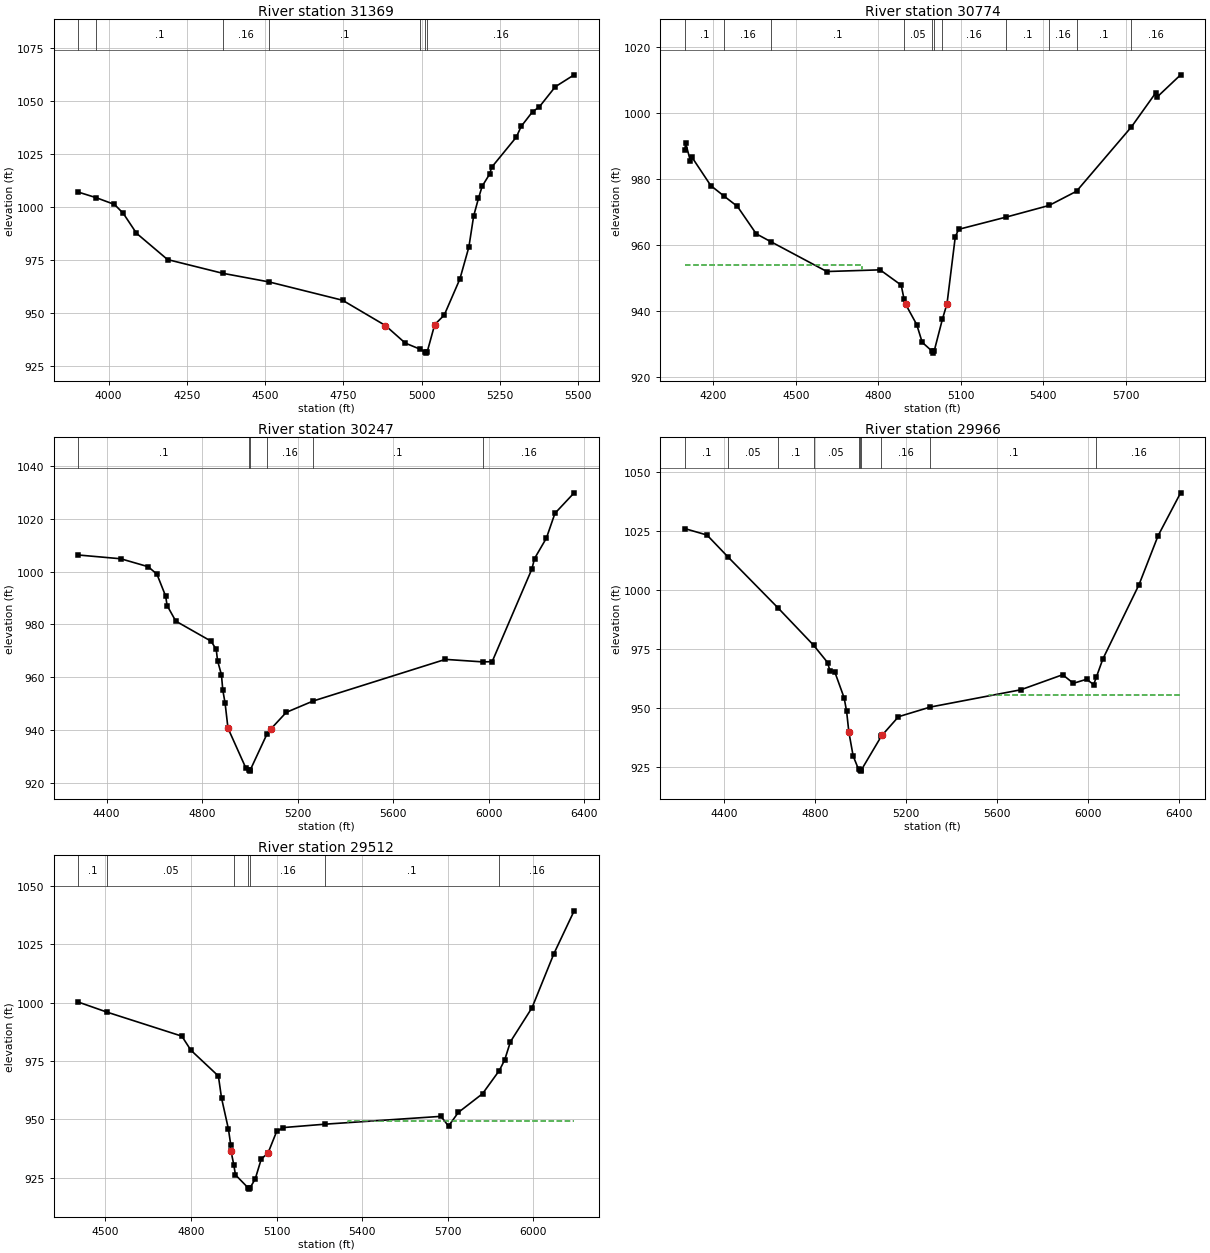
Type RM Length L Ch R = 1 ,31369   ,595,595,595
BEGIN DESCRIPTION:
FLAT CREEK 58.0
END DESCRIPTION:
XS GIS Cut Line= 3
      2959913.86     10068211.94      2960590.98      10067581.7
      2960944.32     10067025.71
#Sta/Elev= 30
  3903.4 1007.04  3960.6 1004.39  4018.8 1001.21  4046.7  997.04  4089.2  987.58
  4188.4  975.15    4364  968.68  4512.9  964.57  4747.3  955.92  4884.2  943.98
  4947.7  935.66  4996.1  932.72  5011.6  931.42  5014.3  930.92  5017.6  931.42
  5041.7  944.39  5072.2  948.91  5122.2  965.97  5150.9  981.07  5166.2  995.76
  5181.4 1004.02  5193.3  1009.8    5217 1015.52  5223.8  1018.8  5302.5 1033.04
  5317.8 1038.07  5354.2 1045.03  5375.4 1047.23    5427 1056.85  5487.2 1062.48
#Mann= 7 ,-1 , 0
  3903.4     .16       0  3960.6      .1       0    4364     .16       0
  4512.9      .1       0  4996.1     .16       0  5011.6     .07       0
  5017.6     .16       0
Bank Sta=4884.2,5041.7
XS Rating Curve= 0 ,0
Exp/Cntr=0.3,0.1

Type RM Length L Ch R = 1 ,30774   ,527,527,527
BEGIN DESCRIPTION:
FLAT CREEK 57.0
END DESCRIPTION:
XS GIS Cut Line= 4
      2960158.73     10068269.18      2960872.23     10067935.87
      2961122.23     10067915.03      2961293.36     10067168.28
#Sta/Elev= 30
  4096.1  988.76  4099.2  990.85  4116.6  985.35  4122.1  986.55  4190.7  977.96
  4239.6  974.74  4287.6  971.66  4356.1  963.37  4408.8  961.01    4613  951.96
  4806.8  952.47  4883.6  947.85  4893.7  943.76  4899.9  942.03  4940.1  935.92
  4960.1  930.54  4997.3  927.77    5000  927.27  5003.3  927.77  5033.8  937.59
  5050.4  942.21  5080.5  962.48  5092.8  964.73    5266  968.44  5421.8  971.95
  5521.7  976.25  5721.6  995.73  5809.7 1005.99  5814.8 1004.74  5900.6 1011.48
#Mann= 11 ,-1 , 0
  4096.1      .1       0  4239.6     .16       0  4408.8      .1       0
  4893.7     .05       0  4997.3    .035       0  5003.3     .05       0
  5033.8     .16       0    5266      .1       0  5421.8     .16       0
  5521.7      .1       0  5721.6     .16       0
#XS Ineff= 2 , 0
         4740.91  953.92
Permanent Ineff=
       T       T
Bank Sta=4899.9,5050.4
XS Rating Curve= 0 ,0
Exp/Cntr=0.3,0.1

Type RM Length L Ch R = 1 ,30247   ,281,281,281
BEGIN DESCRIPTION:
FLAT CREEK 56.0
END DESCRIPTION:
XS GIS Cut Line= 4
      2960476.43     10068805.64      2960903.48     10068534.82
      2961242.02     10068347.32      2961653.34     10067238.32
#Sta/Elev= 30
    4282 1006.25  4459.5 1004.83  4574.7 1001.82  4611.2  998.97  4647.6  990.69
  4653.5  987.17    4690  981.27  4837.5   973.7  4859.2  970.59  4864.9  966.27
    4881  961.04  4886.7  955.21  4896.3   950.3  4908.4  940.83    4984  925.62
  4996.1   925.1  4998.9   924.6  5002.1   925.1  5072.4  938.76    5087  940.44
  5152.3   946.8  5264.7  951.08  5818.4  966.82  5976.5  965.86  6014.3  965.97
  6180.5 1000.95  6191.7 1004.92  6241.3 1012.64  6277.1    1022  6357.5 1029.74
#Mann= 6 ,-1 , 0
    4282      .1       0  4996.1     .07       0  5002.1      .1       0
  5072.4     .16       0  5264.7      .1       0  5976.5     .16       0
Bank Sta=4908.4,5087
XS Rating Curve= 0 ,0
Exp/Cntr=0.3,0.1

Type RM Length L Ch R = 1 ,29966   ,454,454,454
BEGIN DESCRIPTION:
FLAT CREEK 55.0
END DESCRIPTION:
XS GIS Cut Line= 3
      2961080.57     10069357.71      2961387.86     10068274.41
      2961705.57     10067269.17
#Sta/Elev= 30
  4225.9 1026.16  4323.6 1023.42  4417.6 1013.94  4636.3  992.43  4792.3  976.62
  4853.7  969.29  4864.4  965.66  4884.9  965.43  4926.5  954.29  4937.4  948.59
  4947.3  939.77  4966.1  929.63  4989.8  923.96  4996.2  923.66    4999  923.16
  5002.2  923.66  5090.8   938.1  5092.8  938.33  5165.5  946.27  5305.4  950.37
  5703.2   957.7  5887.5   964.1  5934.7  960.46  5992.4  962.16  6023.9  959.93
    6036  963.17    6064  970.74  6223.1 1002.32    6307 1023.11  6406.2 1041.35
#Mann= 10 ,-1 , 0
  4225.9      .1       0  4417.6     .05       0  4636.3      .1       0
  4792.3     .05       0  4989.8      .1       0  4996.2     .07       0
  5002.2      .1       0  5090.8     .16       0  5305.4      .1       0
    6036     .16       0
#XS Ineff= 2 , 0
                         5565.34          955.39
Permanent Ineff=
       T       T
Bank Sta=4947.3,5092.8
XS Rating Curve= 0 ,0
Exp/Cntr=0.3,0.1

Type RM Length L Ch R = 1 ,29512   ,678,678,678
BEGIN DESCRIPTION:
FLAT CREEK 54.0
END DESCRIPTION:
XS GIS Cut Line= 4
      2961799.31     10069076.46      2961799.31      10068706.7
      2961632.65     10068279.62       2961788.9     10067383.76
#Sta/Elev= 30
  4405.1  1000.2    4506  995.88  4767.8  985.63  4799.5  979.62  4895.9  968.58
  4906.9   959.2  4931.1   945.9  4939.1  939.23    4940  936.52  4950.2  930.45
  4955.6  926.33  5000.5  920.71  5003.2  920.21  5006.5  920.71  5024.9  924.51
  5046.4  933.17  5069.6  935.55  5100.1  944.87    5124  946.54  5269.2  947.98
  5675.8  951.33  5702.4  947.17  5736.7     953  5821.5     961  5880.2  970.89
  5899.1  975.41  5919.4  983.25  5995.1   997.8  6071.7  1020.9  6142.7 1039.22
#Mann= 7 ,-1 , 0
  4405.1      .1       0    4506     .05       0  4950.2     .16       0
  5000.5     .07       0  5006.5     .16       0  5269.2      .1       0
  5880.2     .16       0
#XS Ineff= 2 , 0
                         5350.11          949.14
Permanent Ineff=
       T       T
Bank Sta=4940,5069.6
XS Rating Curve= 0 ,0
Exp/Cntr=0.3,0.1