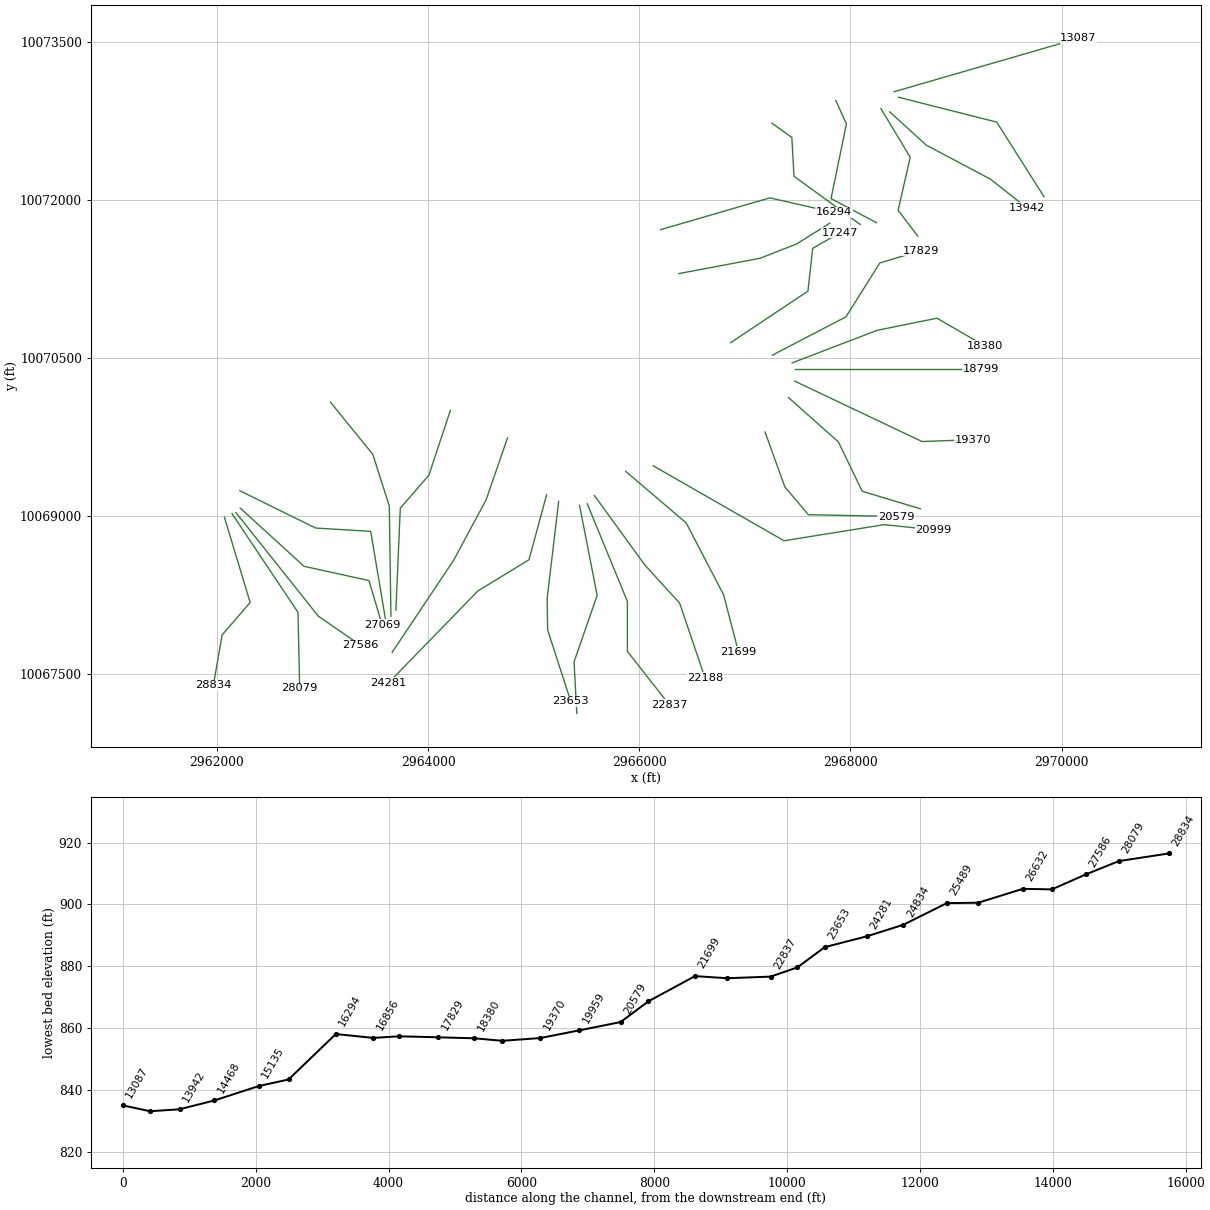
HEC-RAS study FLAT CREEK.prj: FLAT CREEK Base Level Engineering

--- FLAT CREEK.g01 (geometry) --- (continued)

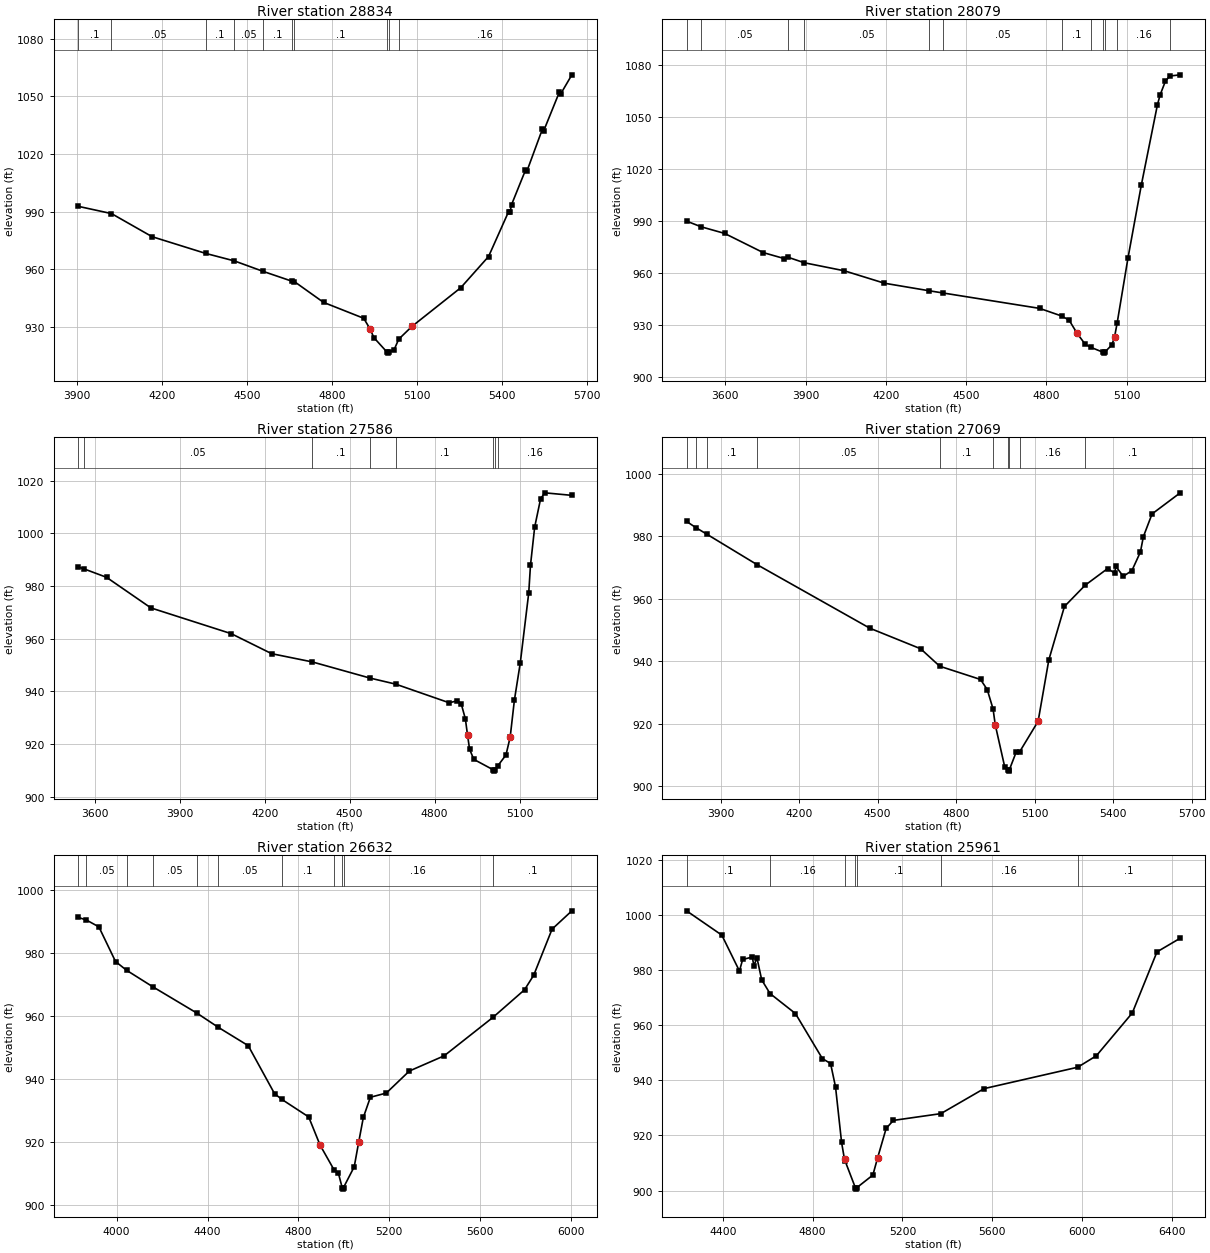
Type RM Length L Ch R = 1 ,28834   ,755,755,755
BEGIN DESCRIPTION:
FLAT CREEK 53.0
END DESCRIPTION:
XS GIS Cut Line= 4
      2962070.14     10068993.18      2962314.94     10068180.66
      2962049.31     10067873.37      2961965.99     10067394.24
#Sta/Elev= 30
  3905.4   992.8  4022.7  989.03  4165.9  977.02  4354.7  968.34  4456.1  964.43
  4557.5  958.99  4658.9   953.9  4668.1  953.64  4770.7  942.87  4912.2  934.62
  4934.1  929.25  4948.2  924.56  4994.7     917  4997.4   916.5  5000.7     917
  5018.6  917.95  5035.9  923.76  5082.2  930.35  5254.5  950.48  5352.7  966.72
  5423.2  989.99  5428.3  989.77  5433.9  993.72  5482.8 1011.56  5487.9 1011.06
  5542.5  1032.9  5547.5 1032.16  5602.1 1052.05  5607.2 1051.26  5646.5 1061.15
#Mann= 10 ,-1 , 0
  3905.4      .1       0  4022.7     .05       0  4354.7      .1       0
  4456.1     .05       0  4557.5      .1       0  4658.9     .05       0
  4668.1      .1       0  4994.7     .07       0  5000.7      .1       0
  5035.9     .16       0
Bank Sta=4934.1,5082.2
XS Rating Curve= 0 ,0
Exp/Cntr=0.3,0.1

Type RM Length L Ch R = 1 ,28079   ,493,493,493
BEGIN DESCRIPTION:
FLAT CREEK 52.0
END DESCRIPTION:
XS GIS Cut Line= 3
      2962143.06     10069024.41      2962768.06     10068086.91
      2962783.68     10067368.41
#Sta/Elev= 30
    3455  990.01  3509.3  986.74    3597  982.94  3741.2   971.9  3819.3  968.48
  3835.4  969.15  3894.9  966.04  4044.7  961.41  4194.9  954.25  4361.3  949.93
  4414.7  948.61    4775  939.77  4857.2  935.38    4885  933.02    4915   925.4
    4945  919.16  4966.5  917.35    5012  914.52  5014.8  914.02    5018  914.52
    5045  918.75    5055  923.36  5064.7  931.36    5105  968.63    5155 1010.71
  5215.1 1056.84  5225.1 1062.56  5245.1 1070.52  5261.3 1073.51  5300.4  1074.2
#Mann= 12 ,-1 , 0
    3455      .1       0  3509.3     .05       0  3835.4      .1       0
  3894.9     .05       0  4361.3      .1       0  4414.7     .05       0
  4857.2      .1       0  4966.5     .05       0    5012    .035       0
    5018     .05       0  5064.7     .16       0  5261.3     .05       0
Bank Sta=4915,5055
XS Rating Curve= 0 ,0
Exp/Cntr=0.3,0.1

Type RM Length L Ch R = 1 ,27586   ,517,517,517
BEGIN DESCRIPTION:
FLAT CREEK 51.0
END DESCRIPTION:
XS GIS Cut Line= 3
      2962179.53     10069034.82      2962960.77     10068050.45
      2963361.84     10067774.39
#Sta/Elev= 30
  3541.3   987.2  3560.7  986.54  3641.3   983.3    3798  971.69  4081.9  961.91
  4224.5  954.32  4368.1  951.19    4572  945.06  4662.4  942.77  4851.9  935.68
  4880.2  936.46  4893.8   935.4  4908.7   929.6  4916.6  923.28  4923.6  918.08
  4938.5  914.22  5007.2  910.25  5009.9  909.75  5013.2  910.25  5023.9  911.86
  5052.1  915.86    5067  922.63  5081.9  936.68  5102.8  950.91  5132.6  977.41
  5138.7  987.84  5153.6 1002.39  5174.5 1013.11  5189.4 1015.36  5284.9  1014.4
#Mann= 8 ,-1 , 0
  3541.3      .1       0  3560.7     .05       0  4368.1      .1       0
    4572     .05       0  4662.4      .1       0  5007.2     .07       0
  5013.2      .1       0  5023.9     .16       0
Bank Sta=4916.6,5067
XS Rating Curve= 0 ,0
Exp/Cntr=0.3,0.1

Type RM Length L Ch R = 1 ,27069   ,437,437,437
BEGIN DESCRIPTION:
FLAT CREEK 50.0
END DESCRIPTION:
XS GIS Cut Line= 4
      2962221.22     10069076.46      2962825.36     10068524.41
      2963439.94     10068388.99      2963564.71     10067967.89
#Sta/Elev= 30
  3769.5  984.73  3805.3  982.74  3848.3  980.58  4039.5  970.88  4470.2  950.57
  4664.3     944  4737.1  938.42  4893.1  934.18  4918.7  930.97  4941.1  924.74
  4949.5  919.65  4985.7  906.19  4997.7  905.36  5000.4  904.86  5003.7  905.36
  5029.4  910.94  5043.1   911.1  5113.3   920.8  5154.3  940.47  5213.9  957.52
  5293.2  964.33  5379.1  969.66  5405.4  968.22  5410.6  970.32  5438.7  967.16
  5471.9  969.02  5504.3  974.95  5515.6  979.85  5548.8  987.13  5656.4  993.88
#Mann= 10 ,-1 , 0
  3769.5      .1       0  3805.3     .05       0  3848.3      .1       0
  4039.5     .05       0  4737.1      .1       0  4941.1     .05       0
  4997.7    .035       0  5003.7     .05       0  5043.1     .16       0
  5293.2      .1       0
Bank Sta=4949.5,5113.3
XS Rating Curve= 0 ,0
Exp/Cntr=0.3,0.1

Type RM Length L Ch R = 1 ,26632   ,671,671,671
BEGIN DESCRIPTION:
FLAT CREEK 49.0
END DESCRIPTION:
XS GIS Cut Line= 4
      2962216.95     10069241.69      2962935.72     10068887.51
      2963456.55     10068856.26      2963597.09     10068018.23
#Sta/Elev= 30
  3830.8   991.3  3866.8  990.46  3921.7  988.29    3995  977.29  4043.5  974.51
  4158.1  969.31  4352.5  960.94  4447.5  956.39    4579  950.58    4695  935.33
  4727.2  933.51  4845.2  927.95  4895.3  919.01  4957.1  911.12  4975.5  910.22
  4992.5  905.53  4995.2  905.03  4998.5  905.53  5045.6  912.12  5065.6  920.05
  5085.7  927.78  5116.7  934.19  5186.8  935.53  5288.2  942.52  5441.5  947.35
  5657.2  959.61  5795.2  968.31  5835.8  972.96  5916.5  987.57  6003.6  993.38
#Mann= 11 ,-1 , 0
  3830.8      .1       0  3866.8     .05       0  4043.5      .1       0
  4158.1     .05       0  4352.5     .16       0  4447.5     .05       0
  4727.2      .1       0  4957.1     .16       0  4992.5     .07       0
  4998.5     .16       0  5657.2      .1       0
Bank Sta=4895.3,5065.6
XS Rating Curve= 0 ,0
Exp/Cntr=0.3,0.1

Type RM Length L Ch R = 1 ,25961   ,472,472,472
BEGIN DESCRIPTION:
FLAT CREEK 48.0
END DESCRIPTION:
XS GIS Cut Line= 4
      2963075.37     10070081.69       2963476.4     10069586.91
      2963632.65     10069097.32      2963648.27     10068050.45
#Sta/Elev= 30
    4239 1001.52    4396   992.7  4474.4  979.69  4488.7  983.86  4531.9  984.76
  4538.3  981.64  4552.7  984.35  4573.5  976.47  4610.6  971.51  4723.7  964.25
  4843.6  947.91  4880.2  946.11  4902.3  937.59  4929.2  917.49  4942.2   911.3
    4945  910.72  4990.6  901.04  4993.4  900.54  4996.6  901.04  5068.5  905.65
  5089.2  911.78  5127.6  922.57  5159.8  925.48  5371.1  927.93  5563.4     937
  5980.5  944.77  6063.5  948.93  6223.5  964.46  6333.5  986.63  6436.8  991.58
#Mann= 7 ,-1 , 0
    4239      .1       0  4610.6     .16       0    4945      .1       0
  4990.6     .07       0  4996.6      .1       0  5371.1     .16       0
  5980.5      .1       0
Bank Sta=4942.2,5089.2
XS Rating Curve= 0 ,0
Exp/Cntr=0.3,0.1

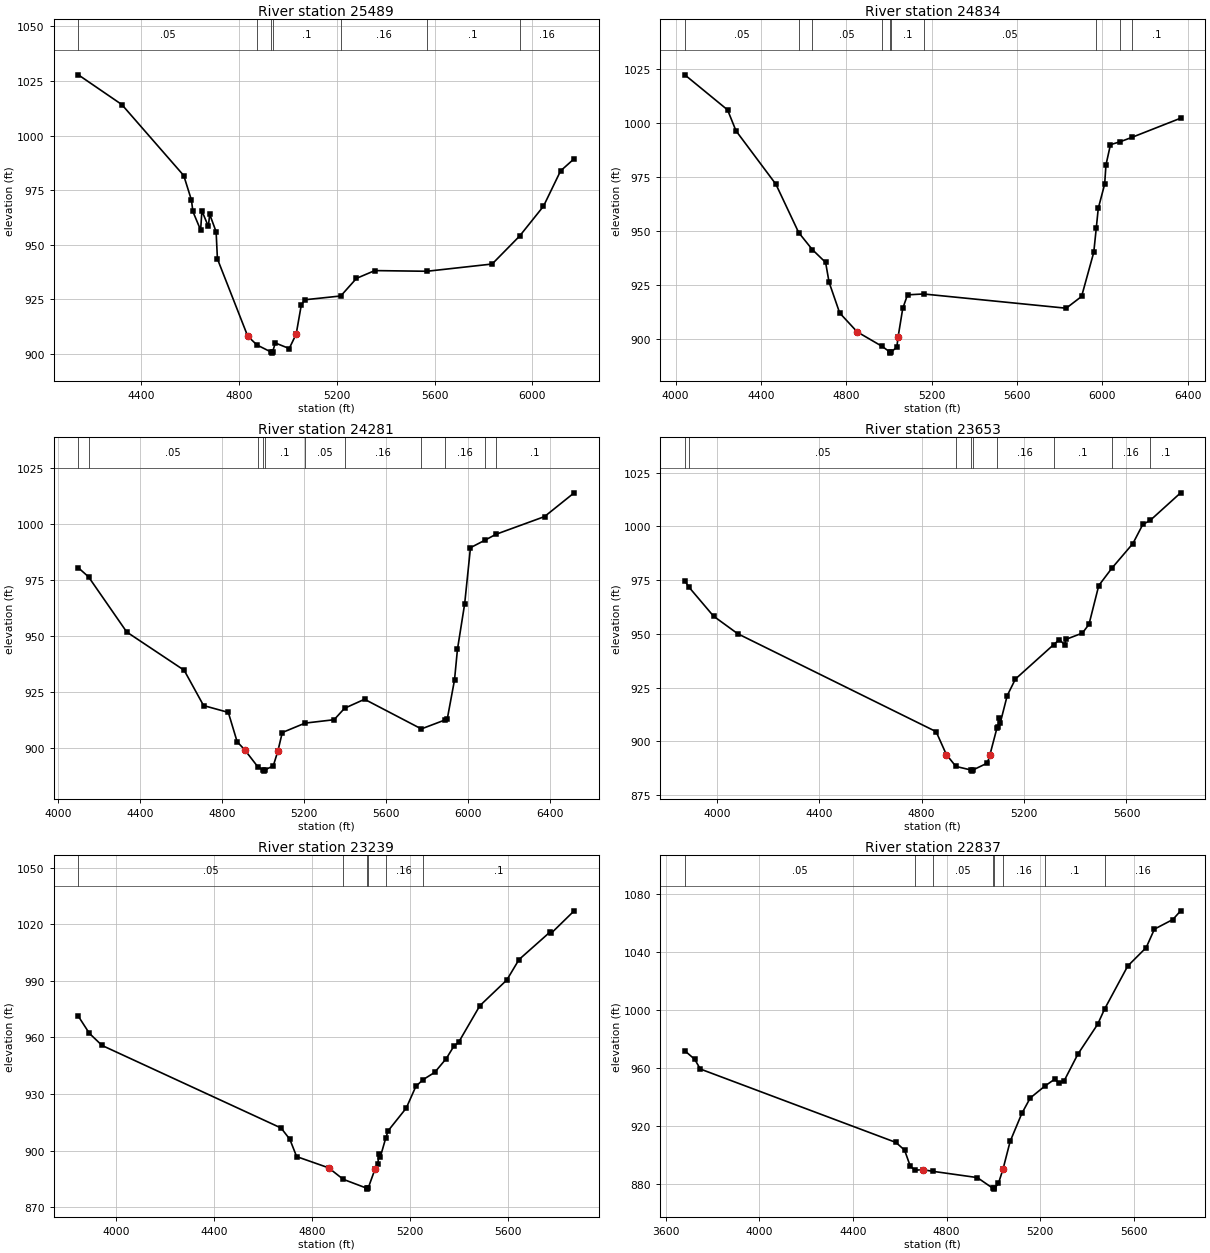
Type RM Length L Ch R = 1 ,25489   ,655,655,655
BEGIN DESCRIPTION:
FLAT CREEK 47.0
END DESCRIPTION:
XS GIS Cut Line= 4
      2964210.77     10070003.56      2964007.65     10069388.99
      2963736.81     10069076.49      2963695.17     10068108.28
#Sta/Elev= 30
  4141.6  1027.8  4319.7 1014.18  4573.2  981.68  4604.8  970.41  4610.5  965.27
  4642.3  956.73  4647.5  965.53    4674  958.39  4679.3  963.99  4705.7  955.96
    4711  943.55    4835  908.19  4872.7  904.16  4930.7  900.91  4933.5  900.41
  4936.7  900.91    4948  905.06    5005  902.51  5033.5  909.14  5054.3  922.38
  5068.6  924.83  5215.9  926.57  5280.3  934.63  5355.3  938.19  5568.7  937.88
  5835.7   941.2  5947.9  953.96  6045.9  967.65    6116  983.84  6171.5  989.38
#Mann= 7 ,-1 , 0
  4141.6     .05       0  4872.7      .1       0  4930.7     .07       0
  4936.7      .1       0  5215.9     .16       0  5568.7      .1       0
  5947.9     .16       0
Bank Sta=4835,5033.5
XS Rating Curve= 0 ,0
Exp/Cntr=0.3,0.1

Type RM Length L Ch R = 1 ,24834   ,553,553,553
BEGIN DESCRIPTION:
FLAT CREEK 46.0
END DESCRIPTION:
XS GIS Cut Line= 4
      2964752.45     10069743.19      2964549.31     10069154.62
      2964242.02      10068581.7      2963659.34     10067707.68
#Sta/Elev= 30
  4043.5 1022.23  4243.9    1006  4283.3  996.32  4470.4  971.57  4577.1  949.21
  4640.8  941.36  4703.3  935.38  4719.5  926.22  4769.3  911.98  4851.1  903.25
  4968.4  896.51  5004.6   893.9  5007.3   893.4  5010.6   893.9  5037.1  896.21
  5042.7  900.77  5064.7  914.08    5087  920.38  5162.2  920.78  5830.5  914.19
  5902.6  919.63  5959.7  940.06  5971.6  951.39  5980.8   960.4  6010.8  971.63
  6016.8  980.48  6037.9   989.9  6083.9  991.27  6138.9   993.3  6366.7 1002.15
#Mann= 10 ,-1 , 0
  4043.5     .05       0  4577.1      .1       0  4640.8     .05       0
  4968.4      .1       0  5004.6     .07       0  5010.6      .1       0
  5162.2     .05       0  5971.6     .16       0  6083.9     .05       0
  6138.9      .1       0
Bank Sta=4851.1,5042.7
XS Rating Curve= 0 ,0
Exp/Cntr=0.3,0.1

Type RM Length L Ch R = 1 ,24281   ,628,628,628
BEGIN DESCRIPTION:
FLAT CREEK 45.0
END DESCRIPTION:
XS GIS Cut Line= 4
      2965122.24     10069201.51      2964955.56     10068586.91
      2964471.19     10068290.03      2963627.45     10067420.25
#Sta/Elev= 30
  4100.4  980.41    4150  976.36  4336.4  951.73  4616.2  934.67  4710.8  918.91
  4831.4  915.86  4874.5  902.75  4910.8  899.22  4974.9  891.62  5002.5  890.15
  5005.3  889.65  5008.5  890.15  5050.5  891.98  5073.1  898.64  5094.4  906.87
  5205.6  911.08    5347  912.59  5398.1  917.71  5495.5  921.72  5772.3  908.49
  5886.1  912.43  5898.8  913.01    5934  930.37  5948.2  943.96  5983.4   964.3
  6011.7  989.37  6082.9  992.74  6135.7  995.33  6372.6 1003.24  6517.1 1013.85
#Mann= 11 ,-1 , 0
  4100.4      .1       0    4150     .05       0  4974.9      .1       0
  5002.5     .07       0  5008.5      .1       0  5205.6     .05       0
  5398.1     .16       0  5772.3     .05       0  5886.1     .16       0
  6082.9     .05       0  6135.7      .1       0
Bank Sta=4910.8,5073.1
XS Rating Curve= 0 ,0
Exp/Cntr=0.3,0.1

Type RM Length L Ch R = 1 ,23653   ,414,414,414
BEGIN DESCRIPTION:
FLAT CREEK 44.0
END DESCRIPTION:
XS GIS Cut Line= 4
      2965236.81     10069138.99      2965127.44     10068217.12
      2965132.65     10067920.24       2965351.4     10067243.16
#Sta/Elev= 30
  3874.7  974.67  3890.6  971.79  3986.9  958.26  4081.4  950.08  4856.4  904.54
  4896.4   893.9  4933.6  888.37  4993.5  886.68  4996.2  886.18  4999.5  886.68
  5056.5  889.92  5066.5  893.74  5093.7  906.07    5100  906.82  5102.1  911.06
  5107.3  908.75  5134.1  921.28  5166.1     929  5315.9  945.05    5338  947.33
  5358.3     945  5363.6  947.46  5427.6  950.37  5453.6  954.47  5491.7  972.49
  5543.6  980.66    5625  992.01  5663.8 1000.91  5692.4 1002.77  5811.5 1015.61
#Mann= 9 ,-1 , 0
  3874.7      .1       0  3890.6     .05       0  4933.6      .1       0
  4993.5     .07       0  4999.5      .1       0  5093.7     .16       0
  5315.9      .1       0  5543.6     .16       0  5692.4      .1       0
Bank Sta=4896.4,5066.5
XS Rating Curve= 0 ,0
Exp/Cntr=0.3,0.1

Type RM Length L Ch R = 1 ,23239   ,402,402,402
BEGIN DESCRIPTION:
FLAT CREEK 43.0
END DESCRIPTION:
XS GIS Cut Line= 4
      2965434.74      10069102.5       2965601.4     10068248.37
      2965382.65     10067618.16      2965408.68     10067128.68
#Sta/Elev= 30
    3844  971.23  3889.1  962.18  3940.7  955.77    4673     912  4708.8  906.04
  4736.7  896.85  4867.3  890.91    4927  884.83  5023.1  880.11  5025.9  879.61
  5029.1  880.11  5057.9  890.49  5068.5  893.08  5073.8  898.26  5079.1  896.76
  5100.8  906.58  5110.8  910.53  5184.9  922.56  5224.1  934.03  5252.8  937.56
  5301.3  941.49  5348.7  948.82  5379.8   955.4  5398.8  957.37  5485.9  976.82
  5596.1  990.44  5646.1 1001.29  5772.3 1015.79  5777.3 1015.17  5871.5  1027.1
#Mann= 6 ,-1 , 0
    3844     .05       0    4927      .1       0  5023.1     .07       0
  5029.1      .1       0  5100.8     .16       0  5252.8      .1       0
Bank Sta=4867.3,5057.9
XS Rating Curve= 0 ,0
Exp/Cntr=0.3,0.1

Type RM Length L Ch R = 1 ,22837   ,649,649,649
BEGIN DESCRIPTION:
FLAT CREEK 42.0
END DESCRIPTION:
XS GIS Cut Line= 4
      2965507.64     10069118.18      2965887.86     10068191.07
      2965887.86     10067717.12      2966283.56     10067212.08
#Sta/Elev= 30
  3681.6  972.09  3723.8  966.23  3747.8   959.5  4583.5  908.83  4620.3  903.53
  4644.3  892.53  4663.9  889.76    4701  889.96  4742.5  888.88    4931  884.59
    4998  877.13  5000.7  876.63    5004  877.13    5021  880.54  5040.8  890.52
    5071  909.51    5121  928.86  5156.8   939.5  5219.5  947.75  5260.6  952.39
  5281.4  949.82  5302.2  951.51    5360  969.66    5445  990.42  5474.1 1000.76
  5573.4 1030.58  5652.1 1043.28  5687.3 1056.02    5766 1062.65  5799.2 1068.65
#Mann= 8 ,-1 , 0
  3681.6     .05       0  4663.9      .1       0  4742.5     .05       0
    4998    .035       0    5004     .05       0  5040.8     .16       0
  5219.5      .1       0  5474.1     .16       0
Bank Sta=4701,5040.8
XS Rating Curve= 0 ,0
Exp/Cntr=0.3,0.1

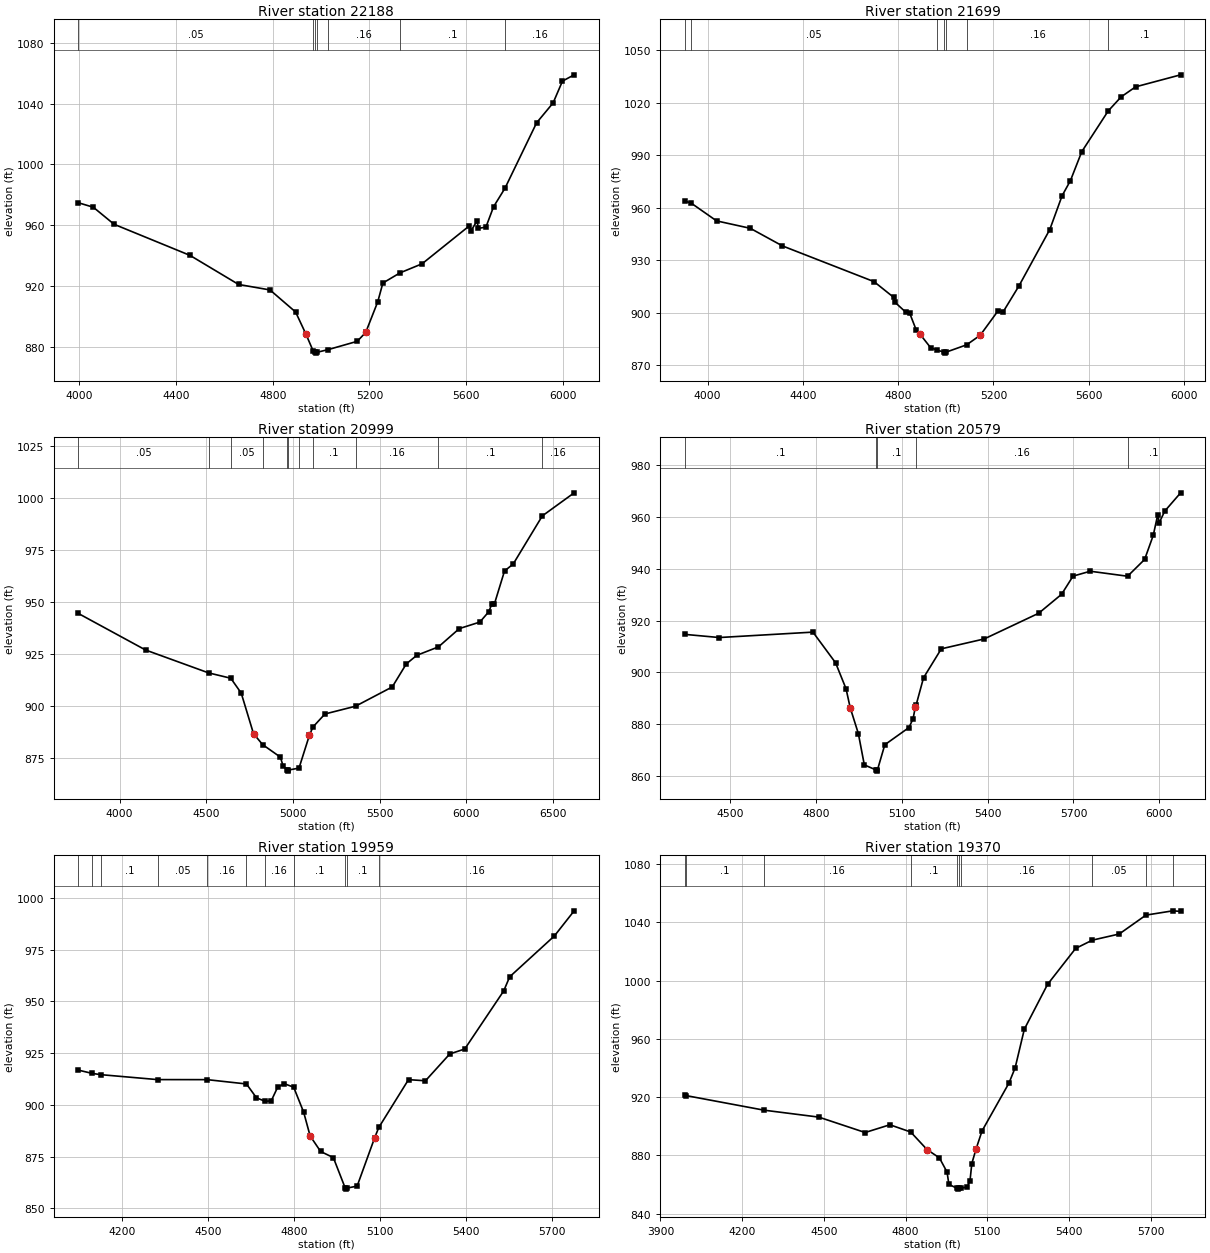
Type RM Length L Ch R = 1 ,22188   ,489,489,489
BEGIN DESCRIPTION:
FLAT CREEK 41.0
END DESCRIPTION:
XS GIS Cut Line= 4
      2965575.34      10069196.3      2966054.52     10068534.82
      2966382.65     10068175.45      2966621.94     10067467.96
#Sta/Elev= 30
  3996.1  974.86    4058  971.92  4143.8  960.73  4457.7  940.31  4658.8   921.2
  4788.7   917.6  4894.6   903.1  4936.5  888.85    4967  877.59  4976.1  876.61
  4978.8  876.11  4982.1  876.61    5030  878.46  5149.3  883.86  5184.4   889.7
  5234.2   909.8  5255.4  922.15  5326.2  928.81  5417.5  934.77  5613.5  959.75
  5618.8  956.15  5644.9  962.97  5650.2     958  5681.6  958.89  5713.1  972.21
  5760.4  984.42  5891.2 1027.38  5959.3  1040.4  5998.1 1054.75  6046.4 1058.86
#Mann= 7 ,-1 , 0
  3996.1     .05       0    4967      .1       0  4976.1     .07       0
  4982.1      .1       0    5030     .16       0  5326.2      .1       0
  5760.4     .16       0
Bank Sta=4936.5,5184.4
XS Rating Curve= 0 ,0
Exp/Cntr=0.3,0.1

Type RM Length L Ch R = 1 ,21699   ,700,700,700
BEGIN DESCRIPTION:
FLAT CREEK 40.0
END DESCRIPTION:
XS GIS Cut Line= 4
       2965872.2     10069425.48      2966445.15     10068935.87
      2966799.31     10068253.57      2966939.94     10067711.92
#Sta/Elev= 30
  3904.1  963.79  3930.6  962.64  4037.5  952.45  4179.1   948.2  4314.1  938.13
  4698.6  917.69  4781.4  908.68    4787  905.85  4831.3  900.28  4847.8  899.86
  4875.5  890.13    4892  887.59  4936.2  879.93  4963.5  878.53    4994  877.29
  4996.7  876.79    5000  877.29  5087.7  881.55  5144.6  887.02  5218.2  900.76
  5240.3  900.28  5306.6  915.09  5436.7   947.5  5488.3  966.81  5523.5  975.52
    5571  992.05  5681.9 1015.32  5736.3  1023.4  5797.1 1029.14  5986.1 1036.01
#Mann= 7 ,-1 , 0
  3904.1     .16       0  3930.6     .05       0  4963.5      .1       0
    4994     .07       0    5000      .1       0  5087.7     .16       0
  5681.9      .1       0
Bank Sta=4892,5144.6
XS Rating Curve= 0 ,0
Exp/Cntr=0.3,0.1

Type RM Length L Ch R = 1 ,20999   ,420,420,420
BEGIN DESCRIPTION:
FLAT CREEK 39.0
END DESCRIPTION:
XS GIS Cut Line= 4
      2966131.91     10069478.71      2967371.53     10068766.88
      2968319.45     10068919.66      2968788.22     10068871.05
#Sta/Elev= 30
  3761.8  944.52  4149.9  926.93    4513  915.93  4641.3  913.35  4701.6  906.21
  4772.6  886.67  4825.4  881.39  4927.4   875.4  4943.2  871.19  4967.5  869.15
  4970.3  868.65  4973.5  869.15  5035.1  870.11  5095.5  886.01  5115.3  889.86
  5184.8  896.15  5361.1  899.88  5573.1  909.16  5654.1  920.24  5714.9  924.38
  5839.7  928.44    5960  937.23  6078.6  940.37  6130.2  945.37  6148.5  949.25
    6163  949.22  6220.8  964.94  6271.1  968.32  6439.1  991.47  6622.7 1002.56
#Mann= 11 ,-1 , 0
  3761.8     .05       0    4513      .1       0  4641.3     .05       0
  4825.4      .1       0  4967.5     .07       0  4973.5      .1       0
  5035.1     .16       0  5115.3      .1       0  5361.1     .16       0
  5839.7      .1       0  6439.1     .16       0
Bank Sta=4772.6,5095.5
XS Rating Curve= 0 ,0
Exp/Cntr=0.3,0.1

Type RM Length L Ch R = 1 ,20579   ,620,620,620
BEGIN DESCRIPTION:
FLAT CREEK 38.0
END DESCRIPTION:
XS GIS Cut Line= 4
      2967191.68     10069799.12      2967379.17     10069278.31
       2967601.4     10069014.43       2968434.1     10068997.08
#Sta/Elev= 30
  4342.7   914.7    4463  913.48  4790.2  915.57  4869.2  903.73  4905.8   893.7
  4920.1  886.46  4948.7  876.43  4969.6  864.33  5009.5  862.42  5012.2  861.92
  5015.5  862.42  5041.1   872.1  5125.6  878.75  5139.9  882.19  5147.7  886.63
  5150.2  887.32  5176.3  897.94  5238.4  909.12  5388.3  912.94  5578.4  922.85
  5658.4  930.17  5698.4  937.18  5758.4  939.07  5888.9  937.14  5948.4  943.62
  5978.5  952.92  5994.1  960.83  5999.1  957.72  6018.5  962.25  6074.1  969.33
#Mann= 5 ,-1 , 0
  4342.7      .1       0  5009.5     .07       0  5015.5      .1       0
  5150.2     .16       0  5888.9      .1       0
Bank Sta=4920.1,5147.7
XS Rating Curve= 0 ,0
Exp/Cntr=0.3,0.1

Type RM Length L Ch R = 1 ,19959   ,589,589,589
BEGIN DESCRIPTION:
FLAT CREEK 37.0
END DESCRIPTION:
XS GIS Cut Line= 4
      2967413.88     10070125.55      2967886.12      10069705.4
      2968111.81     10069236.65      2968663.67     10069070.05
#Sta/Elev= 30
  4048.3   916.8  4097.1  915.19  4127.3  914.59  4324.4  912.21  4497.3  912.19
  4634.5   910.1  4669.4  903.41  4698.6  901.76  4720.7  901.89  4743.4  908.57
    4766  910.24  4799.1  908.55  4833.9  896.48  4856.5  884.97  4893.1  877.46
  4937.5  874.48  4978.9  859.75  4981.7  859.25  4984.9  859.75  5020.4  860.71
  5081.8  884.21  5095.9  889.06  5199.5  912.19  5258.6  911.64  5343.4  924.61
  5395.6  927.01  5531.4  955.08  5552.3  961.92  5708.1  981.66  5777.1  993.82
#Mann= 11 ,-1 , 0
  4048.3      .1       0  4097.1     .05       0  4127.3      .1       0
  4324.4     .05       0  4497.3     .16       0  4634.5      .1       0
  4698.6     .16       0  4799.1      .1       0  4978.9     .07       0
  4984.9      .1       0  5095.9     .16       0
Bank Sta=4856.5,5081.8
XS Rating Curve= 0 ,0
Exp/Cntr=0.3,0.1

Type RM Length L Ch R = 1 ,19370   ,571,571,571
BEGIN DESCRIPTION:
FLAT CREEK 36.0
END DESCRIPTION:
XS GIS Cut Line= 3
      2967472.89      10070281.8      2968677.79     10069708.87
       2969163.7     10069726.22
#Sta/Elev= 30
  3989.6  921.53  3994.8  920.95  4280.2  910.97  4481.6   906.2  4651.7  895.62
  4742.6  900.94    4819  895.97  4878.9  883.92  4924.3  878.23  4952.5  868.45
  4959.1  860.08  4989.3  857.25  4992.1  856.75  4995.3  857.25  5004.2  857.36
  5026.2  858.28  5036.6  862.34  5043.4  874.33  5058.8  884.22  5080.9  896.72
  5179.7  929.57  5202.4  940.03  5236.2  966.57  5321.4  997.33  5424.5 1022.02
  5485.6 1027.69  5584.6 1031.93  5682.7  1044.9  5781.3 1047.84    5810 1047.44
#Mann= 10 ,-1 , 0
  3989.6     .16       0  3994.8      .1       0  4280.2     .16       0
    4819      .1       0  4989.3     .07       0  4995.3      .1       0
  5004.2     .16       0  5485.6     .05       0  5682.7      .1       0
  5781.3     .05       0
Bank Sta=4878.9,5058.8
XS Rating Curve= 0 ,0
Exp/Cntr=0.3,0.1

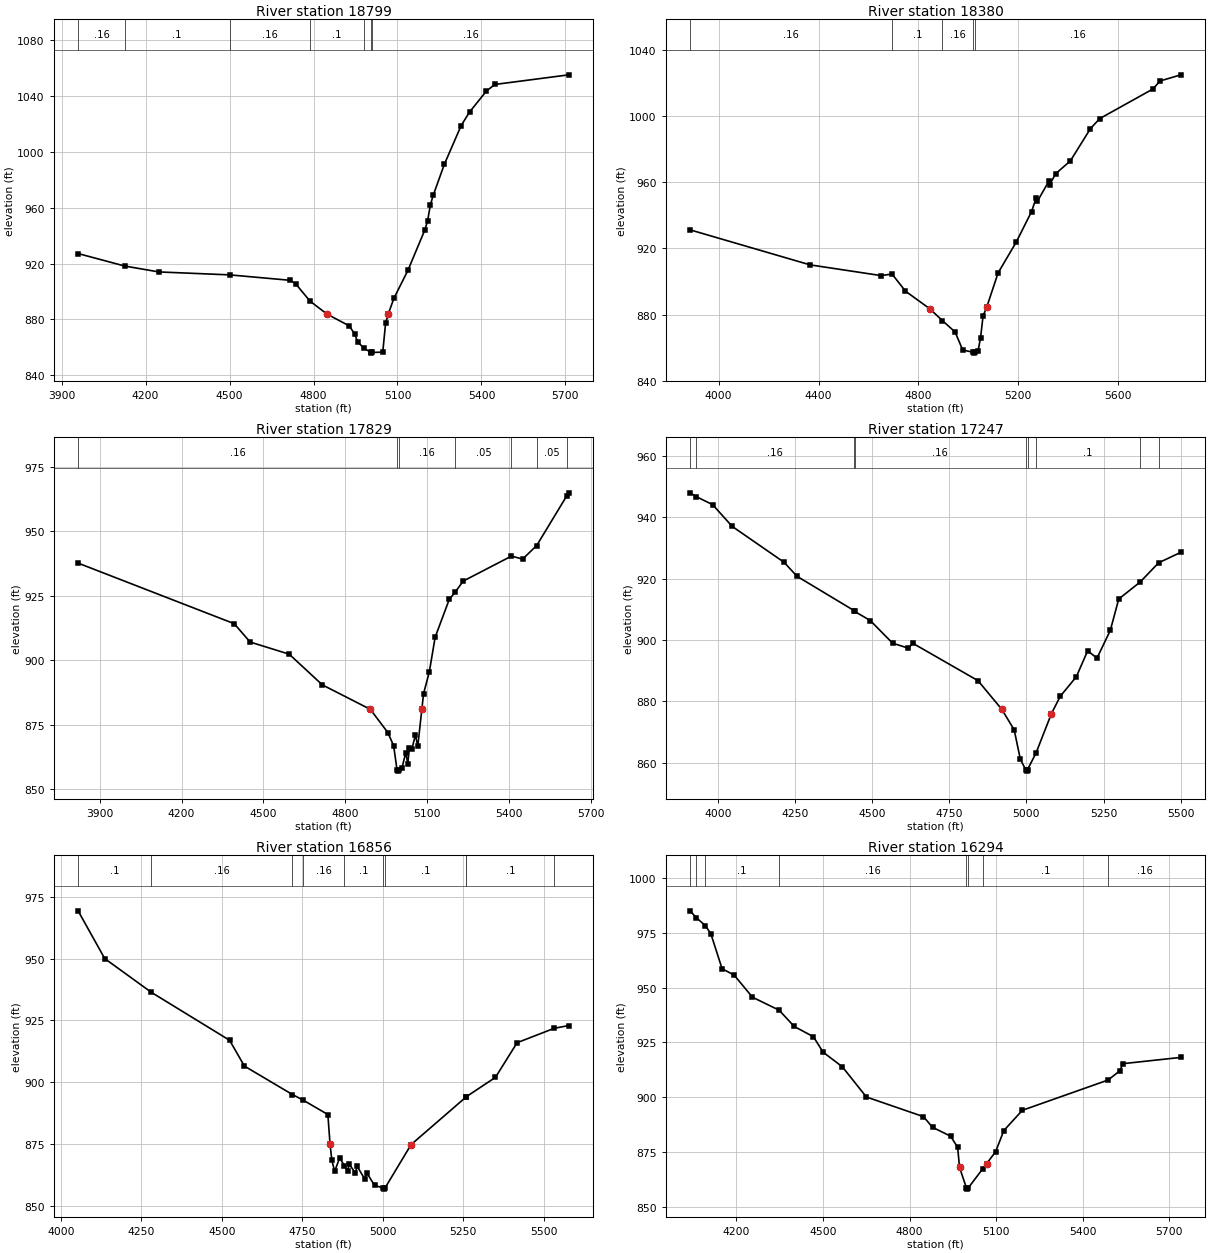
Type RM Length L Ch R = 1 ,18799   ,419,419,419
BEGIN DESCRIPTION:
FLAT CREEK 35.0
END DESCRIPTION:
XS GIS Cut Line= 2
      2967479.87     10070396.37      2969233.37     10070396.37
#Sta/Elev= 30
  3958.8  927.21  4125.7  918.24  4247.4  914.03  4500.1  911.93  4717.4  908.02
  4737.4  905.25  4787.5   893.1  4847.4  883.94  4927.4   875.4  4947.4  869.53
  4957.4  863.89  4979.7  859.57  5004.4  856.36  5007.1  855.86  5010.4  856.36
  5047.4  856.59  5057.4  877.14  5067.4  884.12  5087.4  895.23  5137.4  915.22
  5197.4  943.98  5207.4  950.39  5217.4  961.94  5227.4  968.83  5267.4  991.13
  5327.4 1018.87  5357.4 1028.56  5417.4 1043.54  5447.4 1048.33  5712.3 1055.25
#Mann= 7 ,-1 , 0
  3958.8     .16       0  4125.7      .1       0  4500.1     .16       0
  4787.5      .1       0  4979.7     .16       0  5004.4     .07       0
  5010.4     .16       0
Bank Sta=4847.4,5067.4
XS Rating Curve= 0 ,0
Exp/Cntr=0.3,0.1

Type RM Length L Ch R = 1 ,18380   ,551,551,551
BEGIN DESCRIPTION:
FLAT CREEK 34.0
END DESCRIPTION:
XS GIS Cut Line= 4
      2967448.65     10070455.41      2968254.17     10070764.43
      2968820.15     10070879.01      2969274.24     10070615.57
#Sta/Elev= 30
  3885.6  931.13  4365.8  909.99    4650  903.51  4694.3  904.44    4748   894.1
  4844.6  883.55  4896.1   876.3  4946.6  869.45  4977.2  858.57  5019.6  857.17
  5022.3  856.67  5025.6  857.17  5038.4  857.78  5048.6  865.87  5058.8  879.17
  5073.3  884.41  5118.9  905.13  5191.5  923.72  5252.7  942.11    5271  950.19
  5276.1  948.36  5321.7  960.35  5325.1  958.37  5349.5  965.06  5408.3  972.77
  5488.7  992.27  5525.9  998.33  5739.6 1016.27  5766.9 1021.03  5850.8 1024.77
#Mann= 5 ,-1 , 0
  3885.6     .16       0  4694.3      .1       0  4896.1     .16       0
  5019.6     .07       0  5025.6     .16       0
Bank Sta=4844.6,5073.3
XS Rating Curve= 0 ,0
Exp/Cntr=0.3,0.1

Type RM Length L Ch R = 1 ,17829   ,582,582,582
BEGIN DESCRIPTION:
FLAT CREEK 33.0
END DESCRIPTION:
XS GIS Cut Line= 4
      2967261.13     10070528.32      2967959.04      10070892.9
      2968278.48     10071403.31      2968670.87     10071521.38
#Sta/Elev= 30
  3820.5  937.69  4392.9  914.19  4451.3  907.07  4594.6  902.36  4715.7  890.48
    4892  880.96  4956.2  871.96  4977.4  866.85  4989.8   857.5  4992.5     857
  4995.8   857.5  5008.1  858.24  5021.8  864.18  5029.3  859.88  5035.2  866.13
  5044.6   865.6  5057.2   871.1  5065.9  866.58  5080.8  881.06  5087.1  887.06
  5108.3  895.55  5129.5  908.92  5181.4  923.65  5202.9  926.42  5232.5  930.72
  5409.4  940.41  5450.2  939.25  5501.7  944.49  5612.8  963.89  5619.8  964.95
#Mann= 7 ,-1 , 0
  3820.5     .16       0  4989.8     .07       0  4995.8     .16       0
  5202.9     .05       0  5409.4      .1       0  5501.7     .05       0
  5612.8      .1       0
Bank Sta=4892,5080.8
XS Rating Curve= 0 ,0
Exp/Cntr=0.3,0.1

Type RM Length L Ch R = 1 ,17247   ,391,391,391
BEGIN DESCRIPTION:
FLAT CREEK 32.0
END DESCRIPTION:
XS GIS Cut Line= 4
      2966865.25     10070646.35      2967597.92     10071135.95
      2967643.06      10071542.2      2967903.45     10071691.49
#Sta/Elev= 30
  3910.3  947.89  3929.9  946.67  3983.5  944.03  4046.5  936.98  4214.7  925.29
  4256.8  920.72  4442.3  909.52  4443.9  909.27    4494  906.34  4566.1  898.98
  4617.1  897.34  4632.2  898.91  4843.1  886.76  4920.1  877.44  4960.3  870.77
  4980.4  861.13  4997.6  857.82  5000.3  857.32  5003.6  857.82  5031.3  863.26
  5081.1  876.06  5109.8   881.7  5161.5     888  5198.5  896.49  5228.6  894.08
  5271.8  903.14  5299.1  913.33  5368.8  918.89  5428.2  925.11  5500.4  928.54
#Mann= 9 ,-1 , 0
  3910.3      .1       0  3929.9     .16       0  4442.3      .1       0
  4443.9     .16       0  4997.6     .07       0  5003.6     .16       0
  5031.3      .1       0  5368.8     .16       0  5428.2      .1       0
Bank Sta=4920.1,5081.1
XS Rating Curve= 0 ,0
Exp/Cntr=0.3,0.1

Type RM Length L Ch R = 1 ,16856   ,562,562,562
BEGIN DESCRIPTION:
FLAT CREEK 31.0
END DESCRIPTION:
XS GIS Cut Line= 4
      2966375.75     10071302.63      2967146.54     10071448.45
      2967490.29     10071583.87      2967804.85      10071780.9
#Sta/Elev= 30
  4053.5  969.31  4136.4  949.99  4281.2  936.36  4524.4  916.97  4570.4  906.54
  4719.6  895.04  4753.8  892.71  4829.7  886.96  4836.4  875.05  4842.1  868.45
  4850.8  864.02  4866.5  869.45  4880.9  866.26  4890.8  864.14  4896.2  866.86
  4915.2  863.32  4920.6  866.04    4945  860.73  4950.4  863.45  4974.8  858.28
  5001.5   857.3  5004.3   856.8  5007.5   857.3  5088.4  874.82  5259.8  894.11
  5260.2  894.18  5350.6     902  5417.7  915.99  5532.9  921.81  5578.6  922.95
#Mann= 10 ,-1 , 0
  4053.5      .1       0  4281.2     .16       0  4719.6      .1       0
  4753.8     .16       0  4880.9      .1       0  5001.5     .07       0
  5007.5      .1       0  5259.8     .16       0  5260.2      .1       0
  5532.9     .16       0
Bank Sta=4836.4,5088.4
XS Rating Curve= 0 ,0
Exp/Cntr=0.3,0.1

Type RM Length L Ch R = 1 ,16294   ,711,711,711
BEGIN DESCRIPTION:
FLAT CREEK 30.0
END DESCRIPTION:
XS GIS Cut Line= 3
      2966202.04     10071719.27      2967236.81     10072021.37
      2967843.99     10071882.59
#Sta/Elev= 30
  4039.6  985.04  4061.2  981.89  4092.6  978.27  4111.5  974.58  4150.5  958.61
  4192.1  955.74  4255.8  945.62  4348.1   939.7  4400.5  932.27    4467   927.6
  4500.5  920.54  4567.2  913.88  4650.5   900.1  4848.4  891.12  4879.7  886.27
  4942.2  882.22  4966.8  877.14  4973.4  867.95  4997.3  858.55    5000  858.05
  5003.3  858.55  5054.1   867.4  5067.2  869.67  5098.5  875.16  5126.9  884.79
  5191.1  894.02  5488.3  907.84  5528.9  912.05  5539.8   915.3  5740.4  918.16
#Mann= 8 ,-1 , 0
  4039.6      .1       0  4061.2     .16       0  4092.6      .1       0
  4348.1     .16       0  4997.3     .07       0  5003.3     .16       0
  5054.1      .1       0  5488.3     .16       0
Bank Sta=4973.4,5067.2
XS Rating Curve= 0 ,0
Exp/Cntr=0.3,0.1

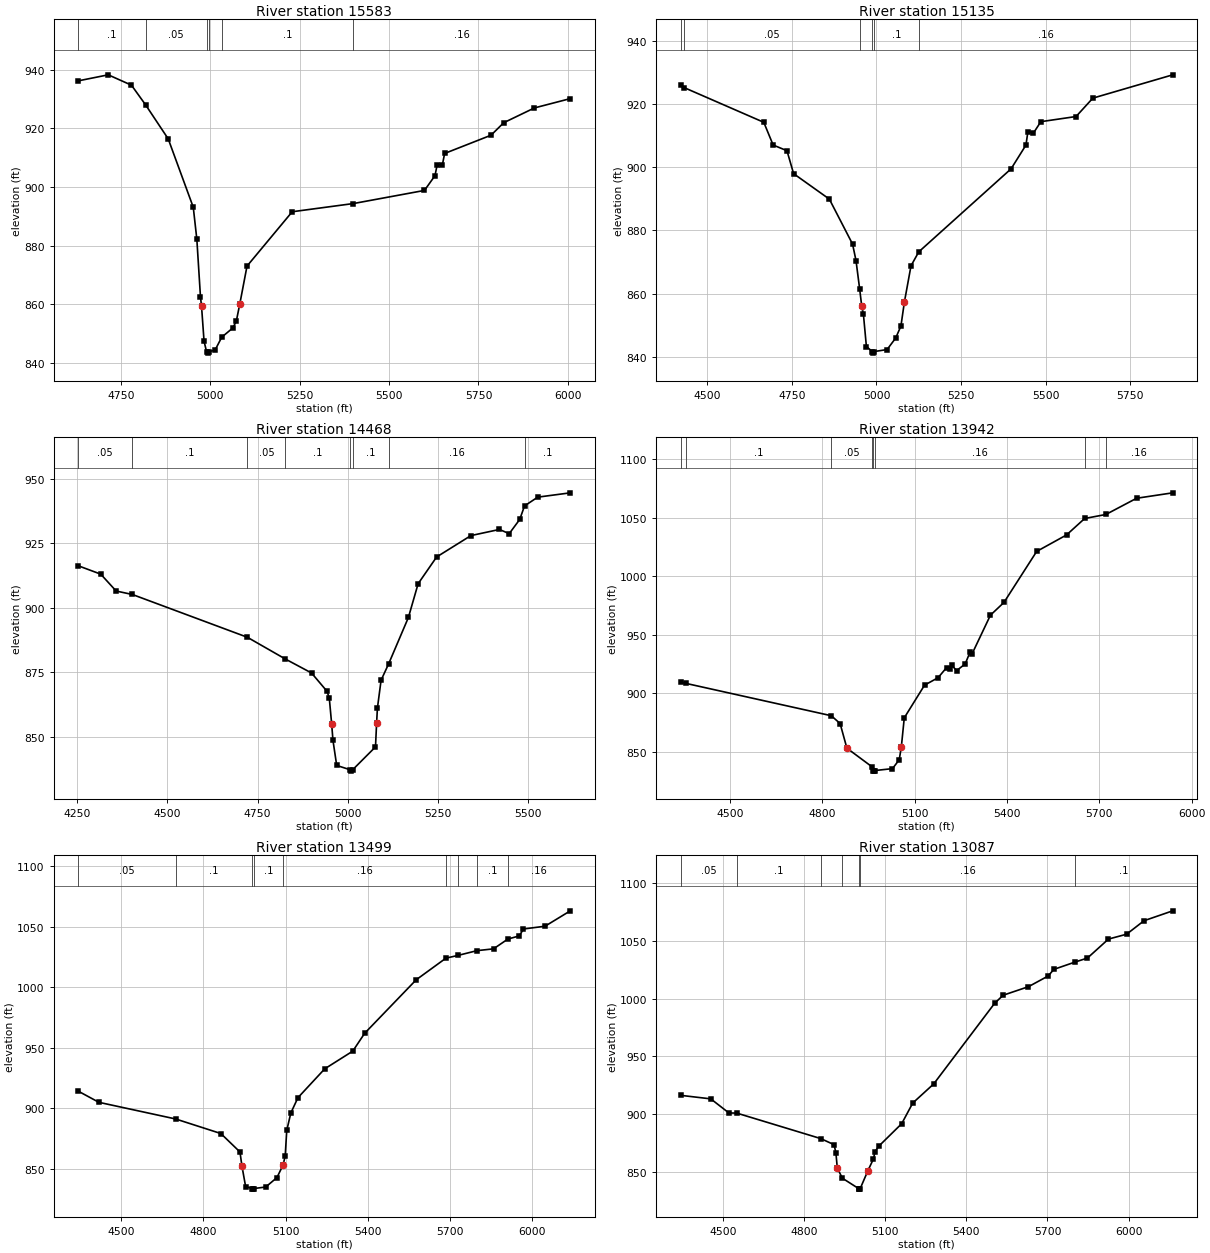
Type RM Length L Ch R = 1 ,15583   ,448,448,448
BEGIN DESCRIPTION:
FLAT CREEK 29.0
END DESCRIPTION:
XS GIS Cut Line= 4
      2967257.62     10072729.72      2967445.15     10072594.29
      2967465.98     10072226.23      2968093.39     10071768.67
#Sta/Elev= 30
  4630.3  936.18  4714.5  938.24  4779.4  934.71  4819.4  927.92  4882.2   916.4
  4952.3  893.07  4962.3  882.11  4972.4  862.59 4975.45  859.27  4982.4  847.42
  4989.4  843.84  4992.1  843.34  4995.4  843.84  5013.1  844.35    5032  848.79
  5062.5  851.88  5072.5  854.15  5082.5  860.16  5102.6  873.02    5229  891.55
  5400.3  894.35  5598.9  898.82  5628.3  903.85  5634.5  907.61  5649.1   907.6
  5655.3  911.43  5785.1  917.65  5820.6  921.91  5906.4  926.95  6006.8  930.13
#Mann= 6 ,-1 , 0
  4630.3      .1       0  4819.4     .05       0  4989.4    .035       0
  4995.4     .05       0    5032      .1       0  5400.3     .16       0
Bank Sta=4975.45,5082.5
XS Rating Curve= 0 ,0
Exp/Cntr=0.3,0.1

Type RM Length L Ch R = 1 ,15135   ,667,667,667
BEGIN DESCRIPTION:
FLAT CREEK 28.0
END DESCRIPTION:
XS GIS Cut Line= 4
      2967861.81     10072944.99      2967962.51     10072722.76
      2967816.67     10072014.43      2968247.22     10071785.26
#Sta/Elev= 30
  4420.9  925.85    4431  925.17  4666.9  914.18  4694.5     907  4735.4   905.2
    4755  897.95  4860.7   889.9  4929.3  875.69  4939.5  870.48  4950.3  861.49
  4956.3  856.16  4961.4   853.5  4970.2  843.31  4987.6  841.72  4990.3  841.22
  4993.6  841.72  5031.4  842.35  5056.9  846.01  5072.3  849.79  5082.5  857.35
  5102.1  868.83  5125.1  873.24    5398  899.49  5441.9  906.99  5447.6  911.22
  5463.9  910.76  5485.9  914.38    5590  916.01  5639.6  921.82  5875.8  929.19
#Mann= 6 ,-1 , 0
  4420.9      .1       0    4431     .05       0  4950.3      .1       0
  4987.6     .07       0  4993.6      .1       0  5125.1     .16       0
Bank Sta=4956.3,5082.5
XS Rating Curve= 0 ,0
Exp/Cntr=0.3,0.1

Type RM Length L Ch R = 1 ,14468   ,526,526,526
BEGIN DESCRIPTION:
FLAT CREEK 27.0
END DESCRIPTION:
XS GIS Cut Line= 4
      2968288.91     10072868.57      2968566.67     10072406.79
      2968452.09     10071903.31      2968638.83     10071657.79
#Sta/Elev= 30
    4253   916.3  4315.6  913.03  4358.3  906.48  4403.2  905.14  4721.9  888.53
    4827   880.1  4899.6  874.67  4942.6  867.56  4948.9  864.89 4955.45  854.87
  4959.1  848.47  4969.4  838.78  5007.4  837.07  5010.1  836.57  5013.4  837.07
  5076.9  845.98    5080  855.22  5082.2  861.01  5092.4  871.86  5113.7  878.33
  5168.1  896.22    5195  909.31  5246.3   919.7  5341.3     928  5420.3  930.38
  5447.4  928.75  5476.5  934.26  5489.9  939.52  5526.4  942.92  5616.7   944.6
#Mann= 8 ,-1 , 0
    4253     .05       0  4403.2      .1       0  4721.9     .05       0
    4827      .1       0  5007.4     .07       0  5013.4      .1       0
  5113.7     .16       0  5489.9      .1       0
Bank Sta=4955.45,5080
XS Rating Curve= 0 ,0
Exp/Cntr=0.3,0.1

Type RM Length L Ch R = 1 ,13942   ,443,443,443
BEGIN DESCRIPTION:
FLAT CREEK 26.0
END DESCRIPTION:
XS GIS Cut Line= 4
      2968372.25     10072837.33      2968719.45     10072521.37
      2969327.09     10072198.45      2969673.87     10071924.49
#Sta/Elev= 30
    4339  909.73  4357.9  908.45  4828.8  880.96  4857.5  874.28  4879.5  853.29
  4961.4  837.34  4964.4   834.2  4967.1   833.7  4970.4   834.2  5027.7  835.83
  5049.6  843.41  5056.5  854.47    5066  879.15  5131.9  907.04  5175.8  913.38
  5203.7  922.06  5214.1  920.42  5219.8   924.1  5236.1  919.46  5263.8  925.08
  5280.1  935.36  5285.7  933.36    5346  966.72    5390  977.61  5496.3 1021.11
  5593.4 1035.17  5652.3  1049.2  5721.1 1052.61    5821 1066.45  5938.5 1071.09
#Mann= 8 ,-1 , 0
    4339     .05       0  4357.9      .1       0  4828.8     .05       0
  4961.4     .16       0  4964.4     .07       0  4970.4     .16       0
  5652.3      .1       0  5721.1     .16       0
Bank Sta=4879.5,5056.5
XS Rating Curve= 0 ,0
Exp/Cntr=0.3,0.1

Type RM Length L Ch R = 1 ,13499   ,412,412,412
BEGIN DESCRIPTION:
FLAT CREEK 25.0
END DESCRIPTION:
XS GIS Cut Line= 3
      2968455.53     10072976.24      2969386.12     10072740.12
      2969833.74     10072032.25
#Sta/Elev= 30
  4342.2   914.1    4418  904.83  4698.2  891.07  4863.4  879.03  4933.3  863.77
  4940.2  852.46  4953.9  835.16  4978.2  833.57  4980.9  833.07  4984.2  833.57
  5027.3  834.81  5068.3  842.62  5090.5  852.96  5098.4   860.3  5104.1  881.57
    5119  896.02    5145  908.67  5242.8   932.5  5345.3  947.16  5388.8  961.93
    5577 1006.14  5685.6 1024.01  5729.5 1026.27  5798.9 1030.21  5859.3  1031.7
  5912.2 1039.86  5953.4 1042.37  5968.7 1048.12  6047.5  1050.4  6139.8 1063.13
#Mann= 9 ,-1 , 0
  4342.2     .05       0  4698.2      .1       0  4978.2     .07       0
  4984.2      .1       0  5090.5     .16       0  5685.6      .1       0
  5729.5     .16       0  5798.9      .1       0  5912.2     .16       0
Bank Sta=4940.2,5090.5
XS Rating Curve= 0 ,0
Exp/Cntr=0.3,0.1

Type RM Length L Ch R = 1 ,13087   ,611,611,611
BEGIN DESCRIPTION:
FLAT CREEK 24.0
END DESCRIPTION:
XS GIS Cut Line= 2
      2968413.89     10073028.31       2970160.4     10073535.25
#Sta/Elev= 30
  4344.4  916.25    4456  913.19  4523.1  900.96  4551.7  900.87  4862.1  878.79
  4911.5  873.49  4918.3  866.54  4923.5   853.3    4942  844.48  5002.2  835.47
  5004.9  834.97  5008.2  835.47  5036.4  850.85  5057.2  861.25  5062.9  867.54
  5078.1   872.5  5161.4  891.66  5202.3  909.58  5279.9  926.17    5505  996.03
  5536.2 1002.98  5629.9  1010.4  5702.8 1019.68  5723.6 1025.39  5801.8 1031.71
    5848 1035.24  5925.5 1051.65  5992.6 1055.87  6056.9 1067.55    6163 1076.13
#Mann= 7 ,-1 , 0
  4344.4     .05       0  4551.7      .1       0  4862.1     .05       0
    4942     .16       0  5002.2     .07       0  5008.2     .16       0
  5801.8      .1       0
Bank Sta=4923.5,5036.4
XS Rating Curve= 0 ,0
Exp/Cntr=0.3,0.1