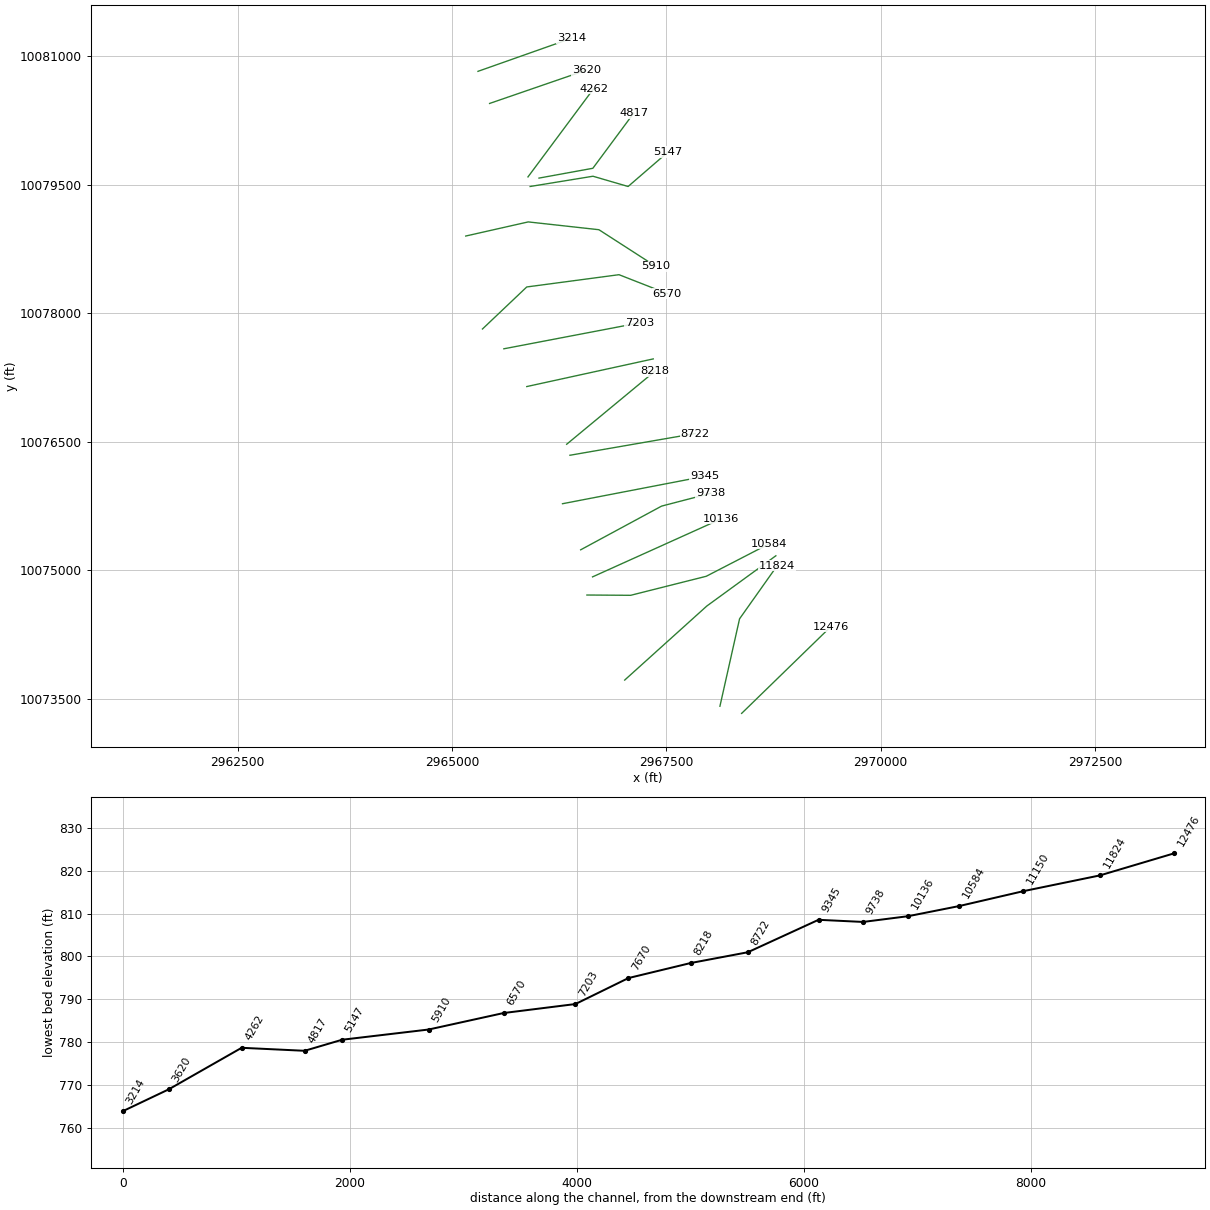
HEC-RAS study FLAT CREEK.prj: FLAT CREEK Base Level Engineering

--- FLAT CREEK.g01 (geometry) --- (continued)

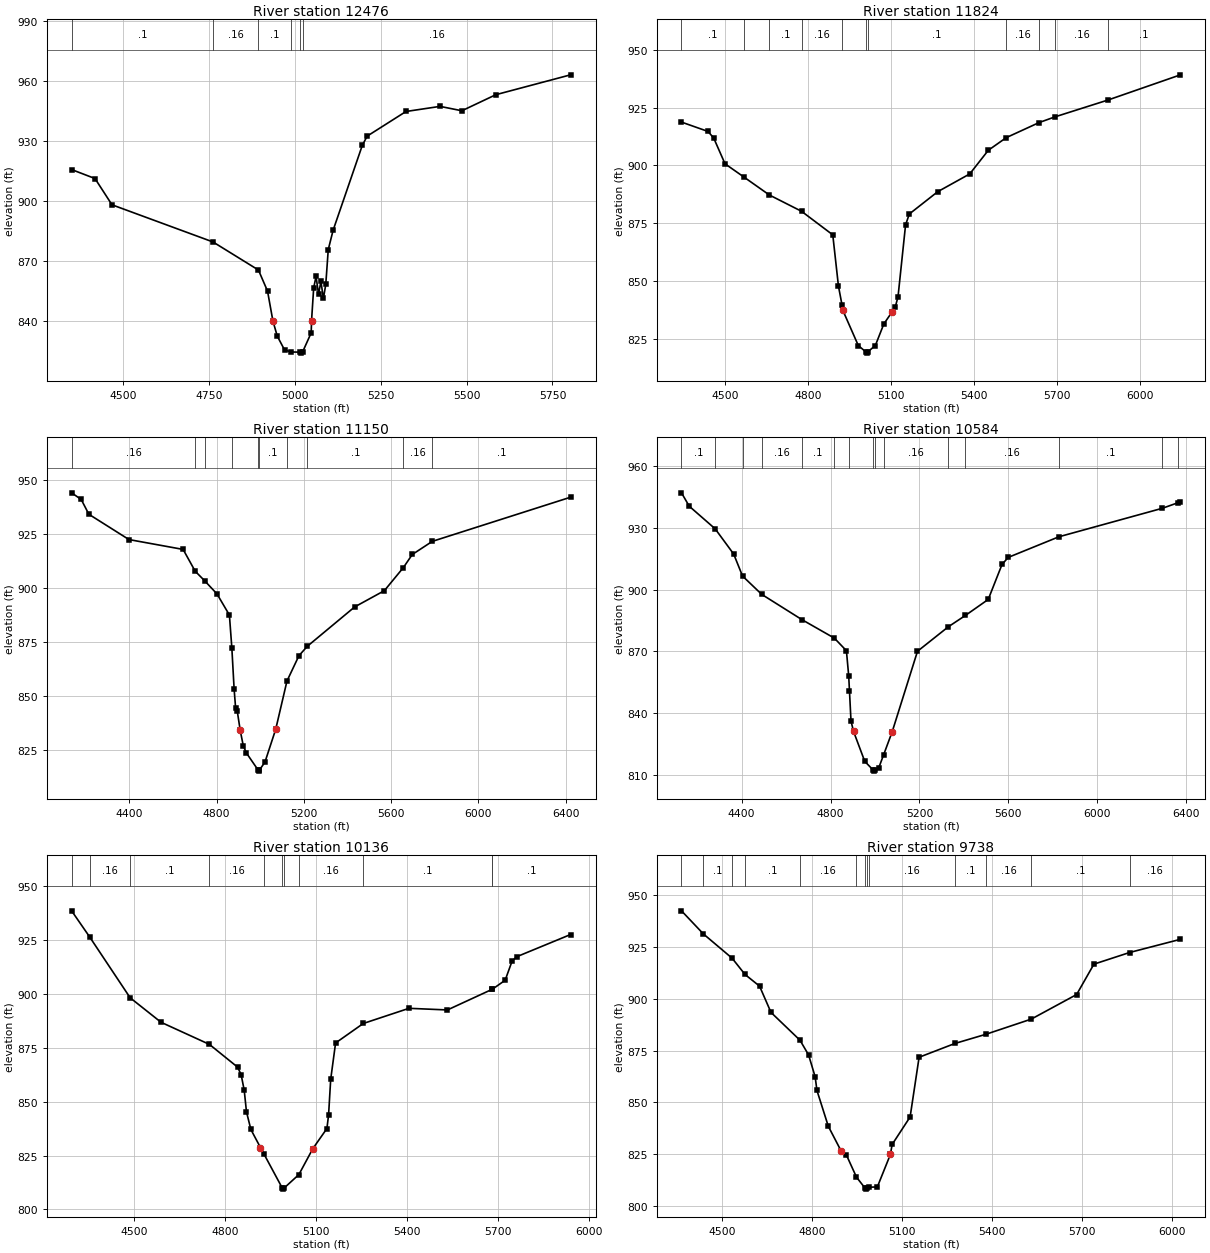
Type RM Length L Ch R = 1 ,12476   ,652,652,652
BEGIN DESCRIPTION:
FLAT CREEK 23.0
END DESCRIPTION:
XS GIS Cut Line= 2
      2968379.14      10073326.9      2969419.79     10074339.79
#Sta/Elev= 30
  4350.6  915.81  4418.7  911.32  4468.1   898.2  4762.1  879.63  4894.3  865.61
  4920.8  855.07 4936.36  840.23  4949.1  832.58  4970.2  825.72  4989.6  824.64
  5016.6  824.58  5019.4  824.08  5022.6  824.58  5047.9  834.23 5048.86  840.23
  5055.1  856.67    5062  862.44  5069.2  853.57  5076.2  859.89  5083.4   851.4
  5090.3  858.43  5097.5   875.8  5111.6  885.45  5196.5  927.85  5210.7  932.51
  5323.8  944.83  5422.9  947.38  5486.4  945.19  5585.4  953.23  5802.8  963.15
#Mann= 6 ,-1 , 0
  4350.6      .1       0  4762.1     .16       0  4894.3      .1       0
  4989.6     .16       0  5016.6     .07       0  5022.6     .16       0
Bank Sta=4936.36,5048.86
XS Rating Curve= 0 ,0
Exp/Cntr=0.3,0.1

Type RM Length L Ch R = 1 ,11824   ,674,674,674
BEGIN DESCRIPTION:
FLAT CREEK 22.0
END DESCRIPTION:
XS GIS Cut Line= 3
      2968125.71     10073410.28      2968354.87     10074431.09
      2968792.23     10075048.94
#Sta/Elev= 30
  4342.5  918.74  4438.3   914.7  4458.8  911.89  4499.8  900.73  4568.4  894.98
  4659.9  887.26  4776.2  880.22  4889.2  870.04  4909.7   847.9  4922.7  839.69
  4925.4  837.47  4981.5  822.21  5009.1  819.44  5011.8  818.94  5015.1  819.44
    5043  822.21  5073.7  831.54  5103.9  836.81  5114.7  838.69    5125  843.32
  5152.3  874.36  5165.9  879.05  5268.4  888.67  5384.3  896.36  5451.3  906.57
  5516.2  912.03  5634.7  918.53  5692.1     921  5883.1  928.25  6145.7  939.16
#Mann= 11 ,-1 , 0
  4342.5      .1       0  4568.4     .16       0  4659.9      .1       0
  4776.2     .16       0  4922.7      .1       0  5009.1     .07       0
  5015.1      .1       0  5516.2     .16       0  5634.7      .1       0
  5692.1     .16       0  5883.1      .1       0
Bank Sta=4925.4,5103.9
XS Rating Curve= 0 ,0
Exp/Cntr=0.3,0.1

Type RM Length L Ch R = 1 ,11150   ,566,566,566
BEGIN DESCRIPTION:
FLAT CREEK 21.0
END DESCRIPTION:
XS GIS Cut Line= 3
       2967014.6     10073715.82      2967972.92      10074580.4
      2968778.47      10075167.2
#Sta/Elev= 30
  4135.6  944.16  4179.6  941.08  4214.7  934.23  4398.6  922.51  4646.7  917.95
    4702  907.86  4746.5  903.32  4802.1  897.32  4858.9  887.56  4870.1  872.29
  4880.6  853.13  4887.3  844.59  4894.8  843.14  4908.5  834.12  4922.5     827
  4936.7  823.69  4990.5  815.76  4993.2  815.26  4996.5  815.76  5021.8  819.42
  5071.2  834.66  5122.8     857  5177.9  868.77  5216.4  873.11  5433.1  891.31
  5569.2  898.84  5656.4  909.54  5697.2   915.6    5789  921.68  6422.9  942.13
#Mann= 10 ,-1 , 0
  4135.6     .16       0    4702      .1       0  4746.5     .16       0
  4870.1      .1       0  4990.5     .07       0  4996.5      .1       0
  5122.8     .16       0  5216.4      .1       0  5656.4     .16       0
    5789      .1       0
Bank Sta=4908.5,5071.2
XS Rating Curve= 0 ,0
Exp/Cntr=0.3,0.1

Type RM Length L Ch R = 1 ,10584   ,448,448,448
BEGIN DESCRIPTION:
FLAT CREEK 20.0
END DESCRIPTION:
XS GIS Cut Line= 4
       2966573.6     10074708.87      2967084.04      10074705.4
      2967965.98     10074927.62      2968698.64      10075306.1
#Sta/Elev= 30
  4129.4  946.97  4164.3  940.46  4280.9  929.48  4364.3  917.21  4403.9  906.56
  4490.2  897.65  4671.6  885.34  4817.1  876.38  4871.3  870.27  4881.6  858.05
    4885  850.82  4891.9  836.15  4903.2  831.11  4953.8  816.52    4992  812.28
  4994.8  811.78    4998  812.28  5015.7  813.08    5039   819.8  5077.5     831
    5191     870  5329.6  881.89  5406.4  887.39  5509.2  895.18  5571.3  912.19
  5599.1   915.6  5827.2  925.62  6292.4  939.46    6365  942.24    6374  942.65
#Mann= 15 ,-1 , 0
  4129.4      .1       0  4280.9     .16       0  4403.9      .1       0
  4490.2     .16       0  4671.6      .1       0  4817.1     .16       0
    4885      .1       0    4992     .07       0    4998      .1       0
    5039     .16       0  5329.6      .1       0  5406.4     .16       0
  5827.2      .1       0  6292.4     .16       0    6365      .1       0
Bank Sta=4903.2,5077.5
XS Rating Curve= 0 ,0
Exp/Cntr=0.3,0.1

Type RM Length L Ch R = 1 ,10136   ,398,398,398
BEGIN DESCRIPTION:
FLAT CREEK 19.0
END DESCRIPTION:
XS GIS Cut Line= 2
      2966639.61     10074920.69      2968139.58     10075597.75
#Sta/Elev= 30
  4294.9  938.51    4354  926.48    4488  898.17  4589.9  886.81  4749.5  876.55
  4842.2  866.02  4853.9  862.57  4864.2  855.27  4871.6  845.29  4886.1  837.09
  4917.8  828.69  4929.7   825.6  4989.7  809.92  4992.4  809.42  4995.7  809.92
  5044.4  816.16  5090.7  828.25  5136.9  837.53  5142.4  843.81  5149.4  860.37
  5165.5  877.21  5256.8  886.25  5407.7  893.29  5534.3  892.53  5681.8   902.1
  5682.5  902.13  5724.8  906.31  5747.9   915.3  5763.8  917.27  5940.6  927.52
#Mann= 11 ,-1 , 0
  4294.9      .1       0    4354     .16       0    4488      .1       0
  4749.5     .16       0  4929.7      .1       0  4989.7     .07       0
  4995.7      .1       0  5044.4     .16       0  5256.8      .1       0
  5681.8     .16       0  5682.5      .1       0
Bank Sta=4917.8,5090.7
XS Rating Curve= 0 ,0
Exp/Cntr=0.3,0.1

Type RM Length L Ch R = 1 ,9738    ,393,393,393
BEGIN DESCRIPTION:
FLAT CREEK 18.0
END DESCRIPTION:
XS GIS Cut Line= 3
      2966500.74     10075236.67      2967445.15     10075747.06
      2968018.02     10075896.36
#Sta/Elev= 30
  4363.4  942.56  4436.5  931.39  4532.3  919.67  4575.5   911.8    4624  906.16
  4662.1  893.48    4759  880.02  4787.7   872.9  4809.6  862.31  4815.5  855.76
  4853.4  838.46  4897.1  826.26  4913.3  824.75  4947.5  813.85    4976  808.57
  4978.7  808.07    4982  808.57  4990.4  809.01  5017.1  809.12  5060.8  824.87
  5066.5  829.65  5126.5  842.95  5156.5   871.8  5276.4  878.48  5378.2  882.84
  5530.9  890.23  5682.3  902.11    5740  916.79  5859.1  922.42  6028.9   928.8
#Mann= 13 ,-1 , 0
  4363.4     .16       0  4436.5      .1       0  4532.3     .16       0
  4575.5      .1       0    4759     .16       0  4947.5      .1       0
    4976     .07       0    4982      .1       0  4990.4     .16       0
  5276.4      .1       0  5378.2     .16       0  5530.9      .1       0
  5859.1     .16       0
Bank Sta=4897.1,5060.8
XS Rating Curve= 0 ,0
Exp/Cntr=0.3,0.1

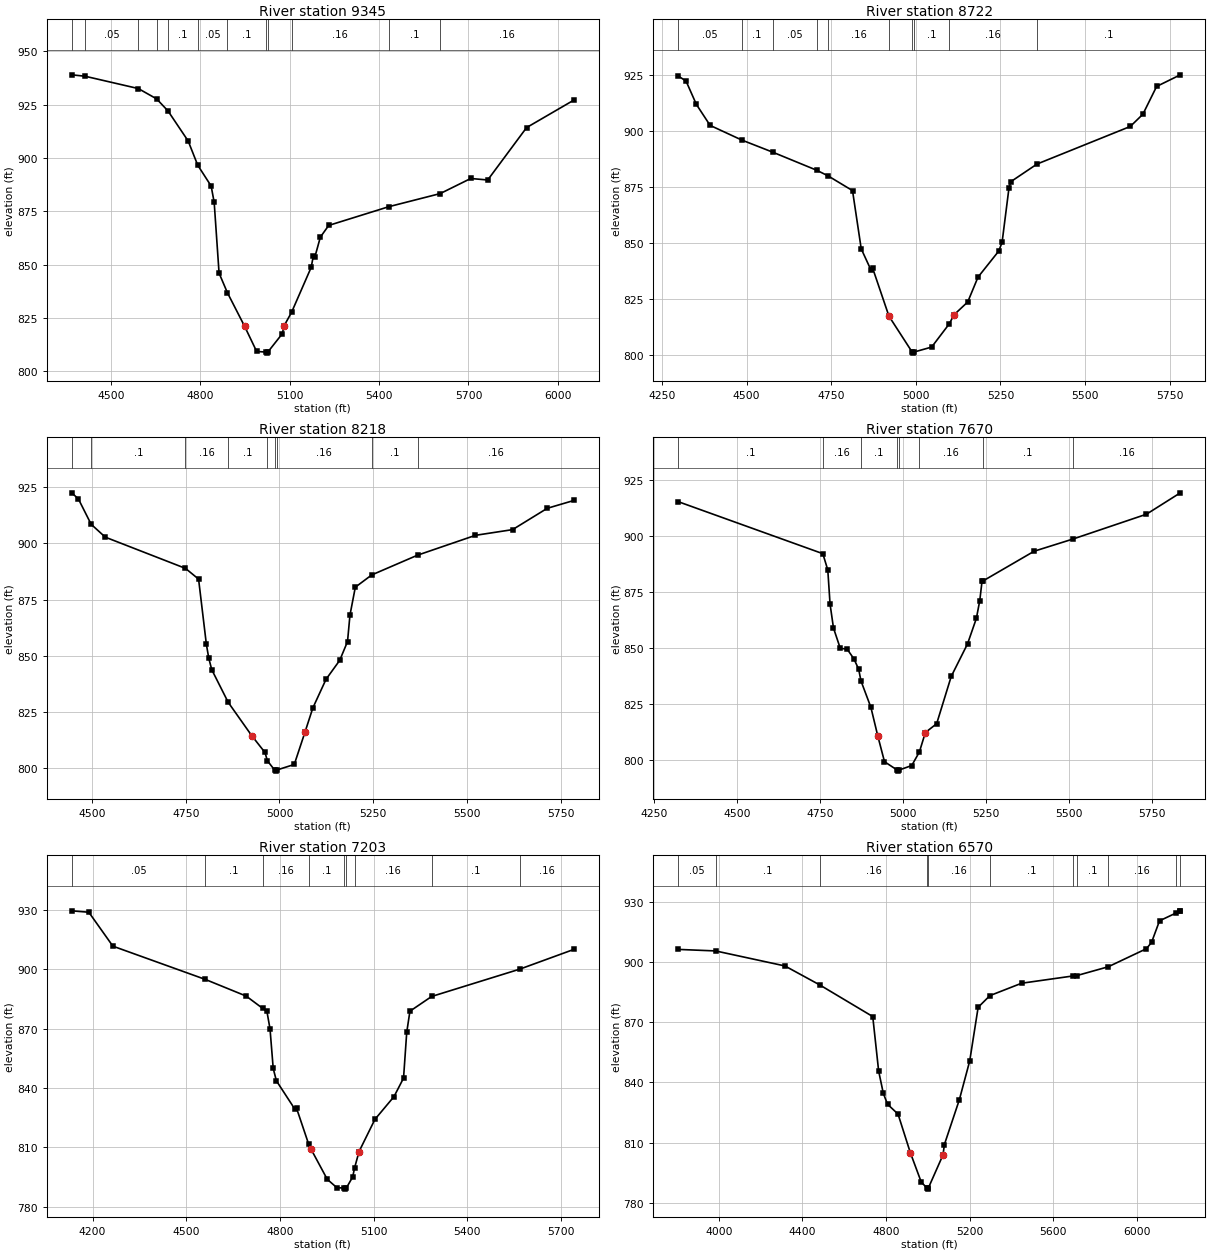
Type RM Length L Ch R = 1 ,9345    ,623,623,623
BEGIN DESCRIPTION:
FLAT CREEK 17.0
END DESCRIPTION:
XS GIS Cut Line= 2
      2966288.89     10075774.84      2967944.28     10076094.12
#Sta/Elev= 30
    4368  939.02  4412.7  938.36  4591.5  932.58  4652.9  927.75  4691.2  922.08
  4758.9  907.99  4790.9  896.67    4836   886.9  4846.2  879.24  4862.6  846.08
  4890.5  836.92  4948.1  821.22  4988.8  809.35  5020.3  809.07  5023.1  808.57
  5026.3  809.07  5075.2  817.71  5080.5  821.26  5106.1  827.71  5172.1  848.83
  5178.9   854.1    5184  853.47  5202.7  862.94  5230.8  868.43  5433.1  877.23
  5605.2  883.36  5707.7  890.43  5764.7  889.73  5895.2  914.29  6053.9  927.17
#Mann= 12 ,-1 , 0
    4368      .1       0  4412.7     .05       0  4591.5      .1       0
  4652.9     .05       0  4691.2      .1       0  4790.9     .05       0
  4890.5      .1       0  5020.3     .07       0  5026.3      .1       0
  5106.1     .16       0  5433.1      .1       0  5605.2     .16       0
Bank Sta=4948.1,5080.5
XS Rating Curve= 0 ,0
Exp/Cntr=0.3,0.1

Type RM Length L Ch R = 1 ,8722    ,504,504,504
BEGIN DESCRIPTION:
FLAT CREEK 16.0
END DESCRIPTION:
XS GIS Cut Line= 2
      2966375.68     10076340.81      2967837.47     10076594.28
#Sta/Elev= 30
  4298.1  924.46  4321.2  922.19  4351.7   911.8  4392.3  902.45  4485.6  895.94
  4577.2  890.53  4707.6  882.45  4740.6  879.98  4813.1  873.39  4838.8  847.47
  4867.7  837.99  4872.8  838.75  4920.7  817.47  4989.2  801.49    4992  800.99
  4995.2  801.49  5046.9  803.69  5099.2  814.08  5112.9  818.05  5153.5  823.78
  5183.9  834.85  5244.8  846.39    5255  850.29  5275.3  874.45  5280.7  877.36
  5358.3  885.23  5633.9  901.98  5671.1  907.42  5711.7   919.8  5781.7  924.98
#Mann= 10 ,-1 , 0
  4298.1     .05       0  4485.6      .1       0  4577.2     .05       0
  4707.6      .1       0  4740.6     .16       0  4920.7      .1       0
  4989.2     .07       0  4995.2      .1       0  5099.2     .16       0
  5358.3      .1       0
Bank Sta=4920.7,5112.9
XS Rating Curve= 0 ,0
Exp/Cntr=0.3,0.1

Type RM Length L Ch R = 1 ,8218    ,548,548,548
BEGIN DESCRIPTION:
FLAT CREEK 15.0
END DESCRIPTION:
XS GIS Cut Line= 2
      2966337.53      10076469.3      2967368.73     10077323.43
#Sta/Elev= 30
  4446.1  922.57  4463.8  919.83  4497.8  908.53  4535.5   902.8  4749.4  888.88
  4784.3  884.09  4805.1  854.97  4811.6  848.74  4819.4  843.72  4863.3  829.15
  4926.2  814.25  4961.4  806.78  4967.8  803.09    4987  798.97  4989.8  798.47
    4993  798.97  5039.5  801.44  5068.2  815.93    5089  826.64  5124.2  839.42
  5160.7  847.87  5181.5  856.24    5188  868.02  5202.3  880.49  5246.1  885.96
  5368.3  894.77  5522.7  903.62  5621.7  906.16  5714.2  915.67  5785.1  919.16
#Mann= 9 ,-1 , 0
  4446.1     .05       0  4497.8      .1       0  4749.4     .16       0
  4863.3      .1       0  4967.8     .16       0    4987     .07       0
    4993     .16       0  5246.1      .1       0  5368.3     .16       0
Bank Sta=4926.2,5068.2
XS Rating Curve= 0 ,0
Exp/Cntr=0.3,0.1

Type RM Length L Ch R = 1 ,7670    ,467,467,467
BEGIN DESCRIPTION:
FLAT CREEK 14.0
END DESCRIPTION:
XS GIS Cut Line= 2
      2965872.18     10077142.89      2967347.96     10077465.82
#Sta/Elev= 30
    4324  915.52  4759.1  892.25    4774  884.95  4780.8  869.73  4791.1     859
  4811.6  849.87    4832  849.59  4852.5  845.22  4866.9  840.57  4873.8  835.34
  4903.7  823.49  4924.2  810.83  4944.6  799.18  4982.6  795.46  4985.3  794.96
  4988.6  795.46  5026.5  797.45  5049.6  803.53  5067.5  812.21  5101.6  816.19
  5145.4  837.34  5194.4  851.88    5221  863.27  5231.3  871.28  5238.3  880.18
    5240  879.97    5395  893.36  5512.6  898.85  5732.8  909.91  5834.7  919.48
#Mann= 8 ,-1 , 0
    4324      .1       0  4759.1     .16       0  4873.8      .1       0
  4982.6     .07       0  4988.6      .1       0  5049.6     .16       0
    5240      .1       0  5512.6     .16       0
Bank Sta=4924.2,5067.5
XS Rating Curve= 0 ,0
Exp/Cntr=0.3,0.1

Type RM Length L Ch R = 1 ,7203    ,633,633,633
BEGIN DESCRIPTION:
FLAT CREEK 13.0
END DESCRIPTION:
XS GIS Cut Line= 2
      2965604.83     10077583.86      2967184.12     10077885.84
#Sta/Elev= 30
  4133.3  929.44  4187.9  928.73    4265  911.59  4560.8  894.81  4691.8  886.39
  4744.6  880.18  4758.1  878.79  4768.2  869.83  4778.4  849.86  4788.6   843.6
    4848  829.22  4853.1  829.78  4892.1  811.52  4900.1  808.92  4951.5  793.85
    4982  789.66  5006.3  789.39  5009.1  788.89  5012.3  789.39  5032.9  795.03
  5039.1  799.66  5053.3  807.86  5104.2  824.13  5165.3  835.63  5195.8  844.96
    5206  868.06  5216.2  878.74  5285.8  886.19    5568  899.99  5741.2  909.95
#Mann= 9 ,-1 , 0
  4133.3     .05       0  4560.8      .1       0  4744.6     .16       0
  4892.1      .1       0  5006.3     .07       0  5012.3      .1       0
  5039.1     .16       0  5285.8      .1       0    5568     .16       0
Bank Sta=4900.1,5053.3
XS Rating Curve= 0 ,0
Exp/Cntr=0.3,0.1

Type RM Length L Ch R = 1 ,6570    ,660,660,660
BEGIN DESCRIPTION:
FLAT CREEK 12.0
END DESCRIPTION:
XS GIS Cut Line= 4
      2965355.29     10077815.32       2965871.8     10078305.79
      2966948.19     10078449.02      2967511.07     10078228.19
#Sta/Elev= 30
  3805.6  906.27  3984.4  905.51  4316.1  898.03    4483  888.56  4736.5   872.8
  4764.7  845.65  4786.9  834.59  4807.1  829.11  4857.5  824.19  4916.1  805.03
  4968.5  790.32  4996.4  787.29  4999.2  786.79  5002.4  787.29  5072.7  803.85
  5079.4  809.03  5150.9  831.34  5200.5  850.66  5240.9  877.43  5297.2  883.24
  5448.8  889.41  5694.6  893.03  5712.3   893.2  5863.6  897.62  6046.2  906.62
  6070.7  909.76  6108.9  920.52  6186.9  924.36  6206.6  925.44  6208.4   925.5
#Mann= 11 ,-1 , 0
  3805.6     .05       0  3984.4      .1       0    4483     .16       0
  4996.4     .07       0  5002.4     .16       0  5297.2      .1       0
  5694.6     .16       0  5712.3      .1       0  5863.6     .16       0
  6186.9      .1       0  6206.6     .16       0
Bank Sta=4916.1,5072.7
XS Rating Curve= 0 ,0
Exp/Cntr=0.3,0.1

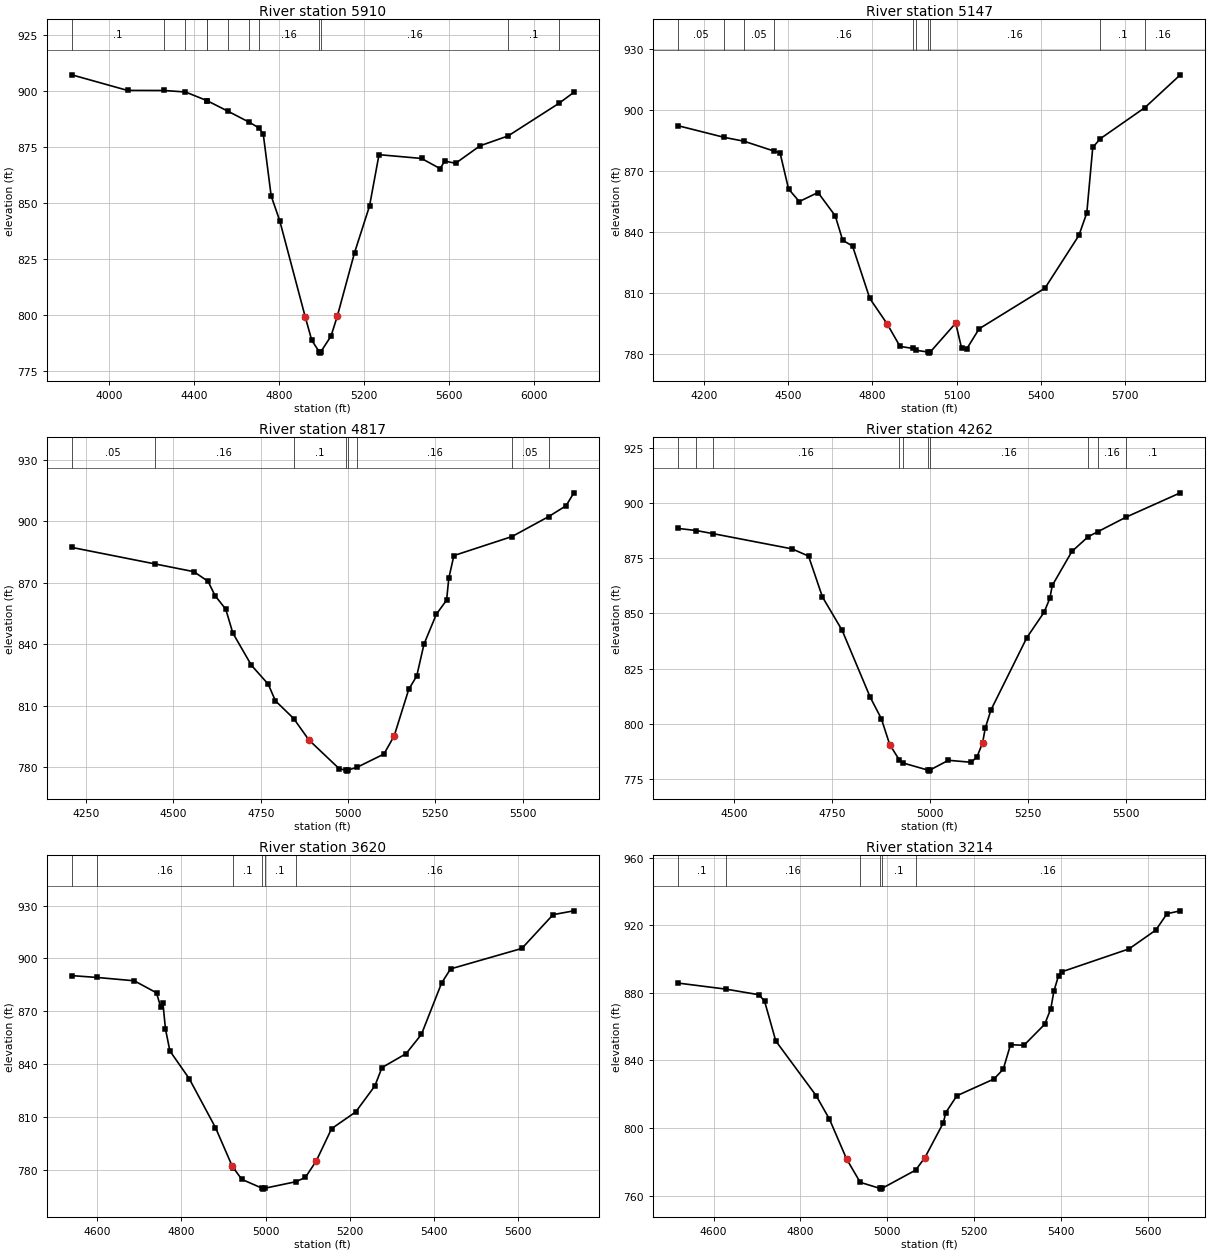
Type RM Length L Ch R = 1 ,5910    ,763,763,763
BEGIN DESCRIPTION:
FLAT CREEK 11.0
END DESCRIPTION:
XS GIS Cut Line= 4
      2965159.95      10078900.4      2965889.16     10079065.33
      2966713.81     10078974.19      2967373.48     10078548.87
#Sta/Elev= 30
  3823.5  907.26  4085.7   900.3  4258.3  900.26  4358.5  899.59  4458.7  895.77
    4460  895.72  4558.9  890.98  4658.7  886.07  4702.4  883.65  4724.3   880.9
  4761.6  853.16  4801.8  842.14  4922.6  798.87  4952.7  788.64  4988.6  783.44
  4991.4  782.94  4994.6  783.44  5043.3  790.57  5073.5  799.68    5154  827.85
  5224.4  848.65    5269  871.59    5469   869.9  5556.8  865.36  5577.9  868.74
  5629.4  867.75  5744.2  875.55  5876.5  879.97    6116  894.55  6185.7  899.44
#Mann= 12 ,-1 , 0
  3823.5      .1       0  4258.3     .05       0  4358.5     .16       0
  4458.7     .05       0    4460      .1       0  4558.9     .05       0
  4658.7      .1       0  4702.4     .16       0  4988.6     .07       0
  4994.6     .16       0  5876.5      .1       0    6116     .16       0
Bank Sta=4922.6,5073.5
XS Rating Curve= 0 ,0
Exp/Cntr=0.3,0.1

Type RM Length L Ch R = 1 ,5147    ,330,330,330
BEGIN DESCRIPTION:
FLAT CREEK 10.0
END DESCRIPTION:
XS GIS Cut Line= 4
      2965911.17     10079478.97      2966644.32     10079598.63
       2967054.6     10079478.96      2967519.94     10079881.63
#Sta/Elev= 30
  4109.7  892.42    4273  886.72  4343.6  884.81  4450.1  879.98  4471.7  879.11
  4502.1   861.3  4540.2  855.13  4606.7  859.58  4668.1   848.1  4694.6  836.06
  4729.6  833.25    4791  807.45  4852.1  795.07  4898.5  783.85  4944.8  782.85
  4956.1  781.94  4999.7  781.05  5002.5  780.55  5005.7  781.05  5096.5  795.31
  5117.3   783.1  5135.4  782.56  5179.8  792.53  5413.9  812.51  5534.5  838.43
  5562.7  849.52  5583.9  881.76  5610.6  886.04  5769.4  901.36  5895.3  917.48
#Mann= 10 ,-1 , 0
  4109.7     .05       0    4273      .1       0  4343.6     .05       0
  4450.1     .16       0  4944.8      .1       0  4956.1     .16       0
  4999.7     .07       0  5005.7     .16       0  5610.6      .1       0
  5769.4     .16       0
#XS Ineff= 2 , 0
                         5096.66          795.18
Permanent Ineff=
       T       T
Bank Sta=4852.1,5096.5
XS Rating Curve= 0 ,0
Exp/Cntr=0.3,0.1

Type RM Length L Ch R = 1 ,4817    ,555,555,555
BEGIN DESCRIPTION:
FLAT CREEK 9.0
END DESCRIPTION:
XS GIS Cut Line= 3
       2966014.6     10079576.93      2966643.06     10079691.51
      2967118.73     10080333.84
#Sta/Elev= 30
  4208.8   887.3  4446.3  879.26  4558.4  875.45    4599  870.75  4619.3   863.7
  4649.8  857.13  4670.1  845.48  4723.3  829.71  4771.5  820.46  4792.1  812.32
  4844.4  803.68  4887.9  793.22  4974.8  779.15  4993.5  778.47  4996.3  777.97
  4999.5  778.47  5026.1  779.85  5102.9  786.31  5132.2  795.14  5173.9  817.89
  5196.9  824.48  5217.7  840.05  5253.2  854.67  5282.4  861.53  5288.7  872.23
  5303.3  883.31  5469.9  892.62  5574.5  902.34  5624.7  907.67  5646.9  913.98
#Mann= 8 ,-1 , 0
  4208.8     .05       0  4446.3     .16       0  4844.4      .1       0
  4993.5     .07       0  4999.5      .1       0  5026.1     .16       0
  5469.9     .05       0  5574.5      .1       0
Bank Sta=4887.9,5132.2
XS Rating Curve= 0 ,0
Exp/Cntr=0.3,0.1

Type RM Length L Ch R = 1 ,4262    ,642,642,642
BEGIN DESCRIPTION:
FLAT CREEK 8.0
END DESCRIPTION:
XS GIS Cut Line= 2
      2965886.09     10079590.78        2966650.     10080618.58
#Sta/Elev= 30
  4357.6  888.44  4403.3   887.5  4445.4  886.12  4647.9   879.2    4690  875.93
  4725.4  857.45  4775.5  842.41  4847.2  812.12  4875.6   802.4    4897   790.7
  4920.9  783.89  4930.4  782.38  4993.7  779.17  4996.5  778.67  4999.7  779.17
  5046.7  783.57  5105.1  782.67  5119.7   785.2  5133.8  791.38  5140.6  798.06
  5155.2  806.33  5246.9  839.09  5290.7  850.51  5305.4  856.82  5311.6  862.65
  5361.7  878.04  5403.3  884.73    5427  886.89  5500.1  893.58  5638.2  904.55
#Mann= 10 ,-1 , 0
  4357.6     .05       0  4403.3      .1       0  4445.4     .16       0
  4920.9      .1       0  4930.4     .16       0  4993.7     .07       0
  4999.7     .16       0  5403.3      .1       0    5427     .16       0
  5500.1      .1       0
Bank Sta=4897,5133.8
XS Rating Curve= 0 ,0
Exp/Cntr=0.3,0.1

Type RM Length L Ch R = 1 ,3620    ,406,406,406
BEGIN DESCRIPTION:
FLAT CREEK 7.0
END DESCRIPTION:
XS GIS Cut Line= 2
      2965438.24     10080448.47      2966565.11      10080836.8
#Sta/Elev= 30
  4539.9  890.21  4600.7  889.15  4688.2  887.27  4741.1  880.44    4751  872.28
  4756.3   874.6  4762.3  859.98  4772.8  847.45  4818.7  831.71  4881.1  803.88
  4920.9  781.95  4923.3  781.13  4943.5  774.53    4992  769.47  4994.7  768.97
    4998  769.47  5071.4  773.15  5094.3  775.58  5120.2  784.92  5156.7   803.3
  5213.9  812.79  5259.4  827.56  5276.3  837.99  5333.4  845.87  5369.9  856.81
    5418  886.08  5439.2  894.02  5608.4  905.65  5682.5  924.83  5731.8     927
#Mann= 6 ,-1 , 0
  4539.9      .1       0  4600.7     .16       0  4923.3      .1       0
    4992     .07       0    4998      .1       0  5071.4     .16       0
Bank Sta=4920.9,5120.2
XS Rating Curve= 0 ,0
Exp/Cntr=0.3,0.1

Type RM Length L Ch R = 1 ,3214    ,443,443,443
BEGIN DESCRIPTION:
FLAT CREEK 6.0
END DESCRIPTION:
XS GIS Cut Line= 2
      2965302.82     10080823.47      2966392.82     10081208.78
#Sta/Elev= 30
  4518.5  885.73  4628.1  882.17  4704.8  878.82  4717.5  874.85  4743.1   851.5
  4835.9  819.21  4866.8  805.18  4906.3  781.62  4937.5  767.88  4982.1  764.35
  4984.9  763.85  4988.1  764.35  5065.1  775.09  5086.6  782.54  5129.1  803.17
  5134.4  809.04    5160  819.08  5245.7  829.02  5266.9  834.81  5283.6  849.29
  5314.5  848.93  5362.4  861.38  5376.4   870.6  5383.6  881.08  5394.2  890.14
    5402  892.43  5556.5  905.96  5618.3  917.11    5644  926.77  5674.6  928.48
#Mann= 6 ,-1 , 0
  4518.5      .1       0  4628.1     .16       0  4937.5      .1       0
  4982.1     .07       0  4988.1      .1       0  5065.1     .16       0
Bank Sta=4906.3,5086.6
XS Rating Curve= 0 ,0
Exp/Cntr=0.3,0.1