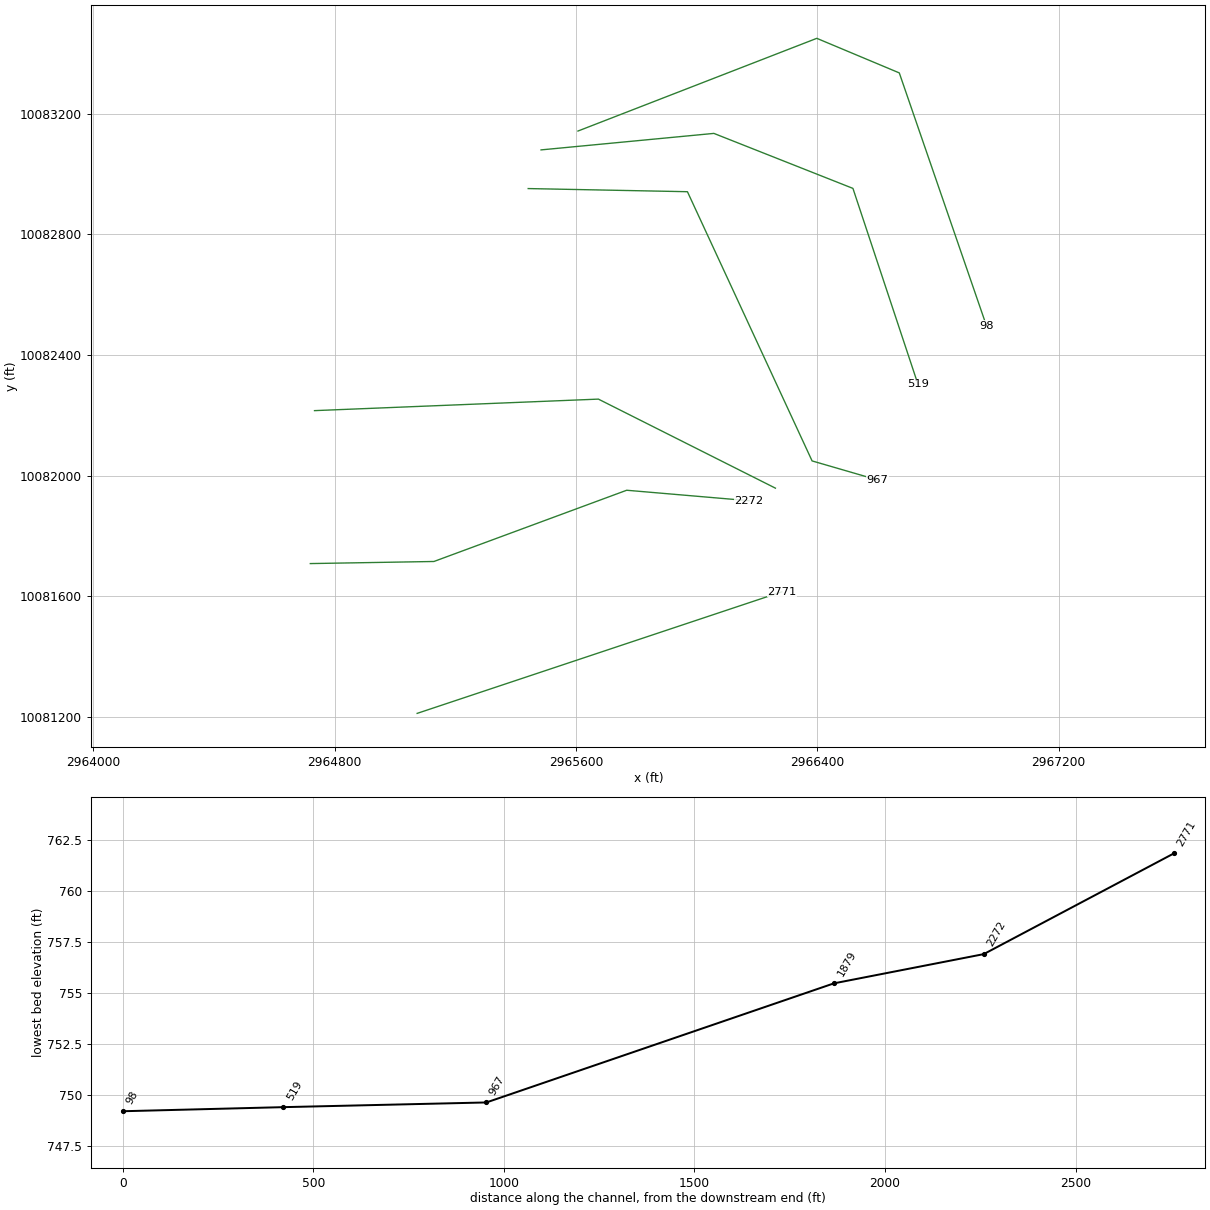
HEC-RAS study FLAT CREEK.prj: FLAT CREEK Base Level Engineering

--- FLAT CREEK.g01 (geometry) --- (continued)

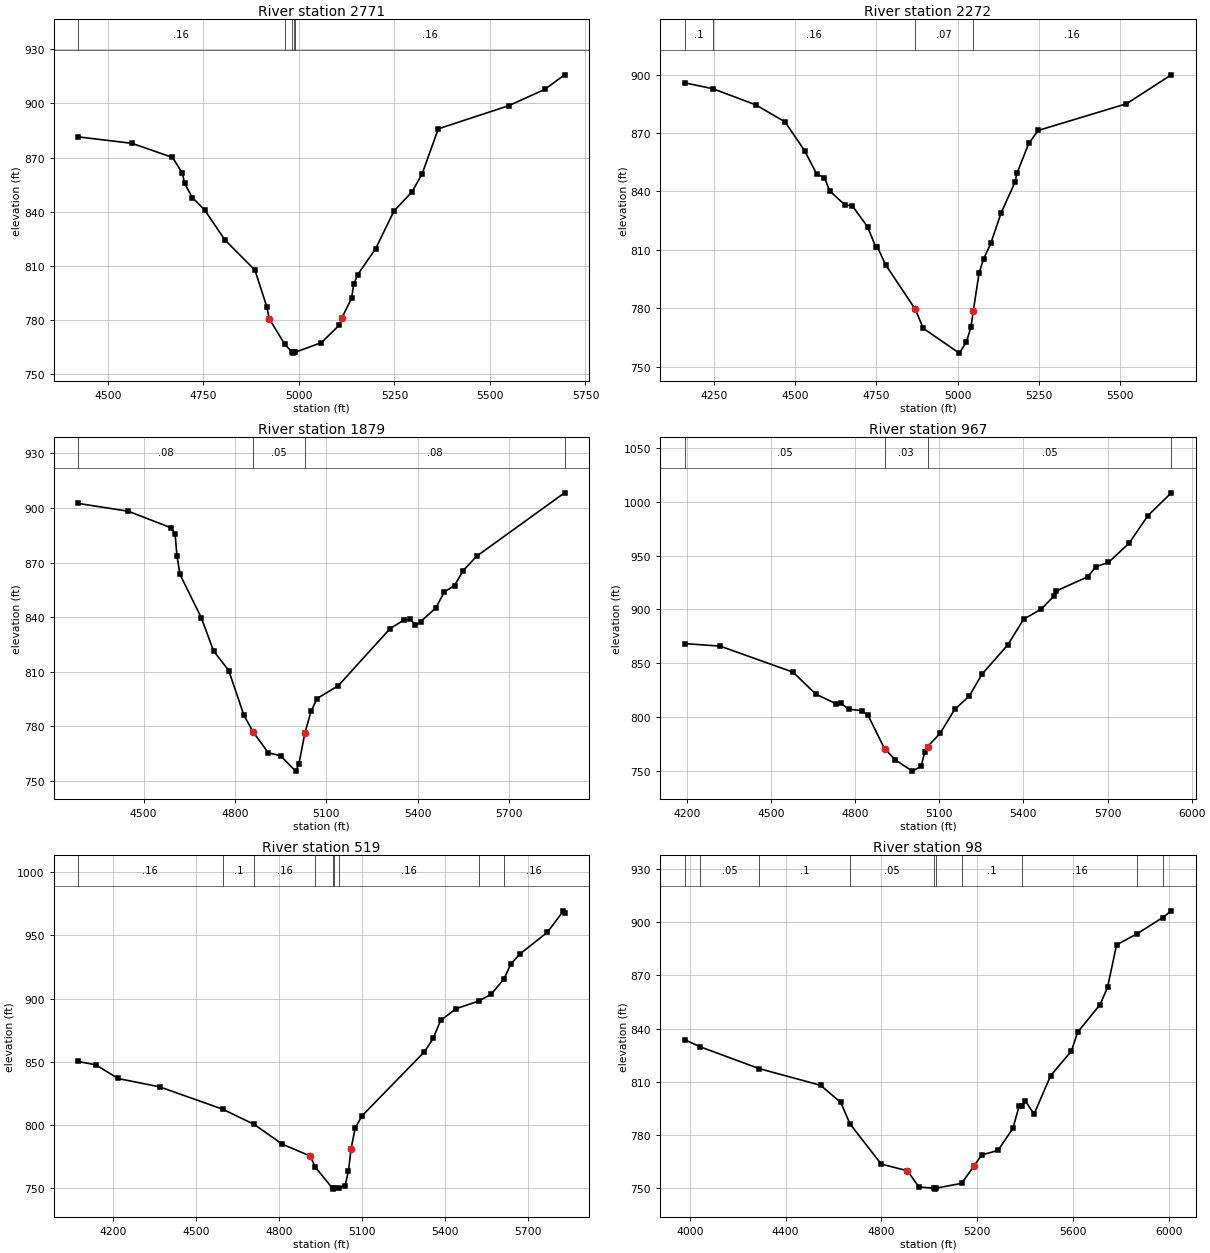
Type RM Length L Ch R = 1 ,2771    ,499,499,499
BEGIN DESCRIPTION:
FLAT CREEK 5.0
END DESCRIPTION:
XS GIS Cut Line= 2
      2965073.58     10081212.33      2966281.92     10081615.11
#Sta/Elev= 30
  4421.5  881.46  4563.3  877.86  4669.1  870.08  4695.1  861.32  4700.7  855.74
  4721.4  847.79  4753.1  841.07  4806.1  824.48  4884.8  807.78  4916.4  787.22
  4922.1  780.91  4962.7   766.8  4982.3  762.32  4985.1  761.82  4988.3  762.32
    4991  762.36  5059.1  767.64  5106.2  777.45  5111.8  781.03  5137.8   792.1
  5143.4  799.88    5154  805.29    5201  819.66  5248.8  840.44  5295.9  850.99
  5322.3  860.89  5364.8  885.89  5548.9  898.67  5643.8  907.75  5695.2  915.76
#Mann= 5 ,-1 , 0
  4421.5     .16       0  4962.7      .1       0  4982.3     .07       0
  4988.3      .1       0    4991     .16       0
Bank Sta=4922.1,5111.8
XS Rating Curve= 0 ,0
Exp/Cntr=0.3,0.1

Type RM Length L Ch R = 1 ,2272    ,393,393,393
BEGIN DESCRIPTION:
FLAT CREEK 4.0
END DESCRIPTION:
XS GIS Cut Line= 4
      2964719.41     10081708.87      2965129.17     10081715.81
      2965768.06     10081951.93      2966173.94     10081917.24
#Sta/Elev= 30
  4159.3  895.79  4246.2  892.78  4378.4  884.46  4468.4  875.74  4528.4  860.99
  4566.3  848.79  4589.7  847.12    4606  840.19  4653.7  832.93    4675  832.66
  4722.4  821.85  4747.5   811.5  4752.8  811.46  4777.9  802.33  4869.1   779.5
  4894.2   769.6  5004.9  756.89  5026.8  762.57  5040.9  770.43  5048.1  778.77
    5066  798.25  5080.1   805.5  5101.8  813.28  5133.4  828.85    5176  844.59
  5182.4  849.29  5218.7  864.62  5247.8  871.32  5519.6  885.04  5657.6  899.91
#Mann= 4 ,-1 , 0
  4159.3      .1       0  4246.2     .16       0  4869.1     .07       0
  5048.1     .16       0
Bank Sta=4869.1,5048.1
XS Rating Curve= 0 ,0
Exp/Cntr=0.3,0.1

Type RM Length L Ch R = 1 ,1879    ,912,912,912
BEGIN DESCRIPTION:
FLAT CREEK 3.0
END DESCRIPTION:
XS GIS Cut Line= 3
      2964733.37     10082215.82      2965674.31     10082254.01
      2966261.15     10081958.86
#Sta/Elev= 30
  4284.4  902.55  4449.6  898.24  4589.8  889.18  4603.8  885.72  4609.8  873.84
  4619.8  863.52  4689.8  839.74  4729.9  821.57  4779.9  810.73  4829.9  786.15
    4860  776.97    4910  765.54    4950  763.91  4999.8  755.46  5010.1  759.21
  5030.1  776.33  5050.1  788.25  5070.1  795.32  5140.2  802.45  5309.7  833.71
  5354.3  838.37  5376.6  838.96  5393.4  835.56  5409.9  837.46  5460.3  845.15
  5488.2  853.94  5521.7  857.43  5549.6  865.55  5594.3  873.53    5883  908.34
#Mann= 4 ,-1 , 0
  4284.4     .08       0    4860     .05       0  5030.1     .08       0
    5883      .1       0
Bank Sta=4860,5030.1
XS Rating Curve= 0 ,0
Exp/Cntr=0.3,0.1

Type RM Length L Ch R = 1 ,967     ,533,533,533
BEGIN DESCRIPTION:
FLAT CREEK 2.0
END DESCRIPTION:
XS GIS Cut Line= 4
      2965441.66     10082951.93      2965969.45     10082941.51
      2966382.65     10082049.15      2966597.89     10081986.66
#Sta/Elev= 30
    4192  868.22  4318.8  865.86  4578.9   841.6  4658.9  821.39  4731.7  812.25
  4749.1  812.66  4777.5   807.2  4823.4  805.89  4846.3  801.38  4904.8  770.49
  4943.5  760.09  5003.7  749.63  5035.2  754.04    5048  767.16  5058.1   772.3
  5103.1  784.83  5155.3  807.12  5206.6  819.32  5252.5  839.78  5344.1     867
    5401  890.93  5464.3  900.36  5510.1  912.82  5515.6  916.98  5630.2  930.44
  5658.6  939.74  5703.3  943.64  5776.8  961.52  5843.9  987.17  5927.4 1008.41
#Mann= 4 ,-1 , 0
    4192     .05       0  4904.8     .03       0  5058.1     .05       0
  5927.4     .16       0
Bank Sta=4904.8,5058.1
XS Rating Curve= 0 ,0
Exp/Cntr=0.3,0.1

Type RM Length L Ch R = 1 ,519     ,421,421,421
BEGIN DESCRIPTION:
Mapping XS 26a057fb
END DESCRIPTION:
XS GIS Cut Line= 4
      2965484.23      10083080.1       2966057.1     10083134.78
      2966518.04     10082952.49      2966733.82     10082302.52
#Sta/Elev= 30
  4074.4  850.28  4138.9  847.68  4219.3  836.83    4370  830.18  4596.5  812.59
  4710.1  800.59  4812.6  784.86  4912.9  775.53  4930.4  766.99  4993.7   749.9
  4996.5   749.4  4999.7   749.9    5015  750.45  5038.5   752.1  5050.8   763.7
    5060  781.28  5075.2  797.74  5099.5  807.28    5325  857.96  5356.7  868.56
  5383.1   882.7  5439.3     892  5520.1  897.98  5565.7  903.41  5612.2  915.62
  5636.5  927.17  5668.2     935  5768.5  952.39  5826.6  969.33  5830.4  967.55
#Mann= 9 ,-1 , 0
  4074.4     .16       0  4596.5      .1       0  4710.1     .16       0
  4930.4      .1       0  4993.7     .07       0  4999.7      .1       0
    5015     .16       0  5520.1      .1       0  5612.2     .16       0
Bank Sta=4912.9,5060
XS Rating Curve= 0 ,0
Exp/Cntr=0.3,0.1

Type RM Length L Ch R = 1 ,98      ,0,0,0
BEGIN DESCRIPTION:
FLAT CREEK 1.0
END DESCRIPTION:
XS GIS Cut Line= 4
       2965606.6      10083142.6      2966398.24     10083449.89
      2966671.68      10083335.3      2966960.41     10082497.73
#Sta/Elev= 30
  3978.2  833.71  4043.9  829.63  4289.3  817.33  4545.6  807.92    4630  798.23
  4668.4   786.1  4798.7  763.39  4908.5  759.56    4956  750.43  5019.8   749.7
  5022.5   749.2  5025.8   749.7  5134.4  752.47  5187.2  762.46  5218.4  768.54
  5286.1  771.05  5348.5  783.55  5374.5  796.03  5386.2  796.38  5400.4  799.11
  5436.9  791.63  5506.3  813.41  5592.9  827.26  5618.8  837.92  5712.5  853.56
  5743.7  863.29  5781.3  887.28  5868.6  893.72  5973.4  902.71  6009.8  906.55
#Mann= 10 ,-1 , 0
  3978.2     .16       0  4043.9     .05       0  4289.3      .1       0
  4668.4     .05       0  5019.8    .033       0  5025.8     .05       0
  5134.4      .1       0  5386.2     .16       0  5868.6      .1       0
  5973.4     .16       0
Bank Sta=4908.5,5187.2
XS Rating Curve= 0 ,0
Exp/Cntr=0.3,0.1

Chan Stop Cuts=-1
Use User Specified Reach Order=0
Composite Channel Slope=5