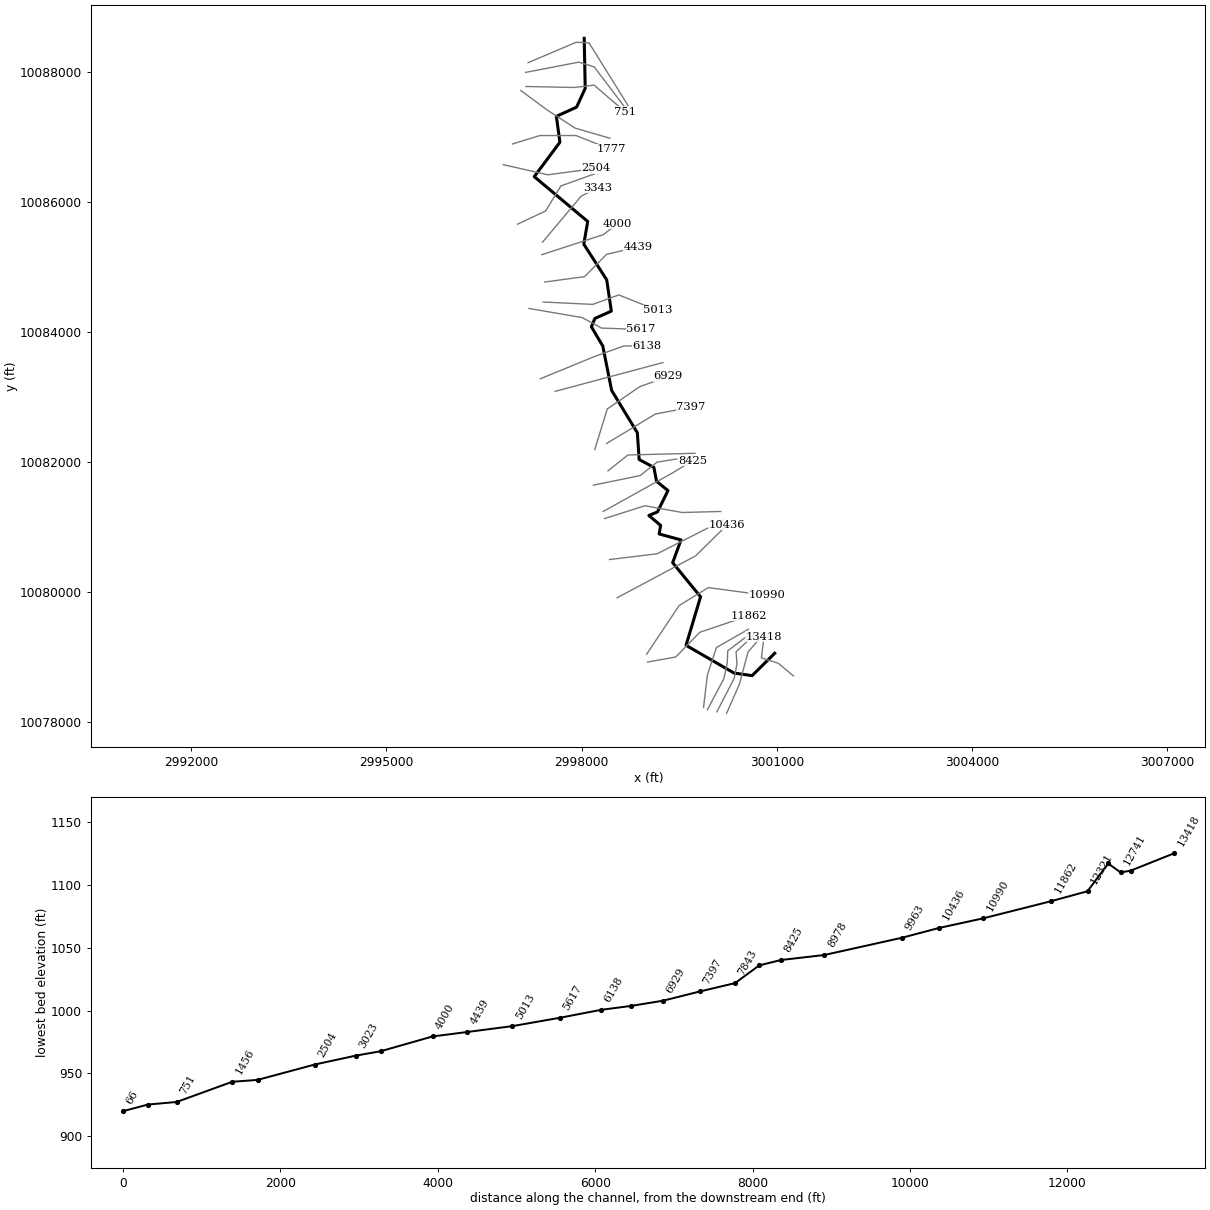
--- HAMILTON CREEK TRIB 1.prj (project) ---

Proj Title=HAMILTON CREEK TRIB 1 Base Level Engineering
Current Plan=p01
Default Exp/Contr=0.3,0.1
English Units
Geom File=g01
Flow File=f01
Plan File=p01
BEGIN DESCRIPTION:
HAMILTON CREEK TRIB 1
END DESCRIPTION:

--- HAMILTON CREEK TRIB 1.p01 (plan) ---

Plan Title=Multiple Run
Short Identifier=Multiple
Geom File=g01
Flow File=f01
Subcritical Flow
K Sum by GR= 0
Std Step Tol= 0.01
Critical Tol= 0.01
Num of Std Step Trials= 20
Max Error Tol= 0.3
Flow Tol Ratio= 0.001
Split Flow NTrial= 30
Split Flow Tol= 0.02
Split Flow Ratio= 0.02
Log Output Level= 0
Friction Slope Method= 1
Unsteady Friction Slope Method= 2
Unsteady Bridges Friction Slope Method= 1
Parabolic Critical Depth
Global Vel Dist=  1 , 1 , 1
Global Log Level= 0
CheckData=True
Encroach Param= -1, 0, 0, 0
BEGIN DESCRIPTION:
Multiple Run
END DESCRIPTION:

--- HAMILTON CREEK TRIB 1.f01 (steady flow) ---

Flow Title=Multiple
Number of Profiles=7
Profile Names=10-year,25-year,50-year,1pct_min,100-year,1pct_plu,500-year
River Rch & RM= HAMILTON CREEK T,Reach-1,13418
     924    1344    1710    1594    2156    2916    3437
River Rch & RM= HAMILTON CREEK T,Reach-1,10436
    1479    2196    2833    2672    3614    4888    5903
Boundary for River Rch & Prof#=HAMILTON CREEK T,Reach-1,1
Up Type=0
Dn Type=3
Dn Slope=0.005
Boundary for River Rch & Prof#=HAMILTON CREEK T,Reach-1,2
Up Type=0
Dn Type=3
Dn Slope=0.005
Boundary for River Rch & Prof#=HAMILTON CREEK T,Reach-1,3
Up Type=0
Dn Type=3
Dn Slope=0.005
Boundary for River Rch & Prof#=HAMILTON CREEK T,Reach-1,4
Up Type=0
Dn Type=3
Dn Slope=0.005
Boundary for River Rch & Prof#=HAMILTON CREEK T,Reach-1,5
Up Type=0
Dn Type=3
Dn Slope=0.005
Boundary for River Rch & Prof#=HAMILTON CREEK T,Reach-1,6
Up Type=0
Dn Type=3
Dn Slope=0.005
Boundary for River Rch & Prof#=HAMILTON CREEK T,Reach-1,7
Up Type=0
Dn Type=3
Dn Slope=0.005

--- HAMILTON CREEK TRIB 1.g01 (geometry) ---

Geom Title=Existing Conditions

River Reach=HAMILTON CREEK T,Reach-1
Reach XY= 30
      3000966.18     10079058.34      3000619.48     10078714.44
      3000341.25     10078753.86      2999603.79     10079181.11
      2999826.50     10079927.80      2999398.13     10080452.71
      2999526.26     10080803.19      2999190.67     10080894.99
      2999212.99     10081026.46      2999032.38     10081179.11
      2999164.33     10081234.39      2999325.95     10081562.60
      2999150.42     10081704.38      2999109.80     10081918.47
      2998883.00     10082041.13      2998855.29     10082452.42
      2998460.25     10083104.41      2998324.39     10083786.76
      2998149.15     10084083.68      2998202.31     10084211.69
      2998455.59     10084324.96      2998384.44     10084806.93
      2998032.25     10085355.32      2998092.38     10085704.90
      2997270.94     10086394.89      2997665.42     10086924.96
      2997610.57     10087322.82      2997921.42     10087464.43
      2998054.28     10087754.83      2998038.47     10088523.73

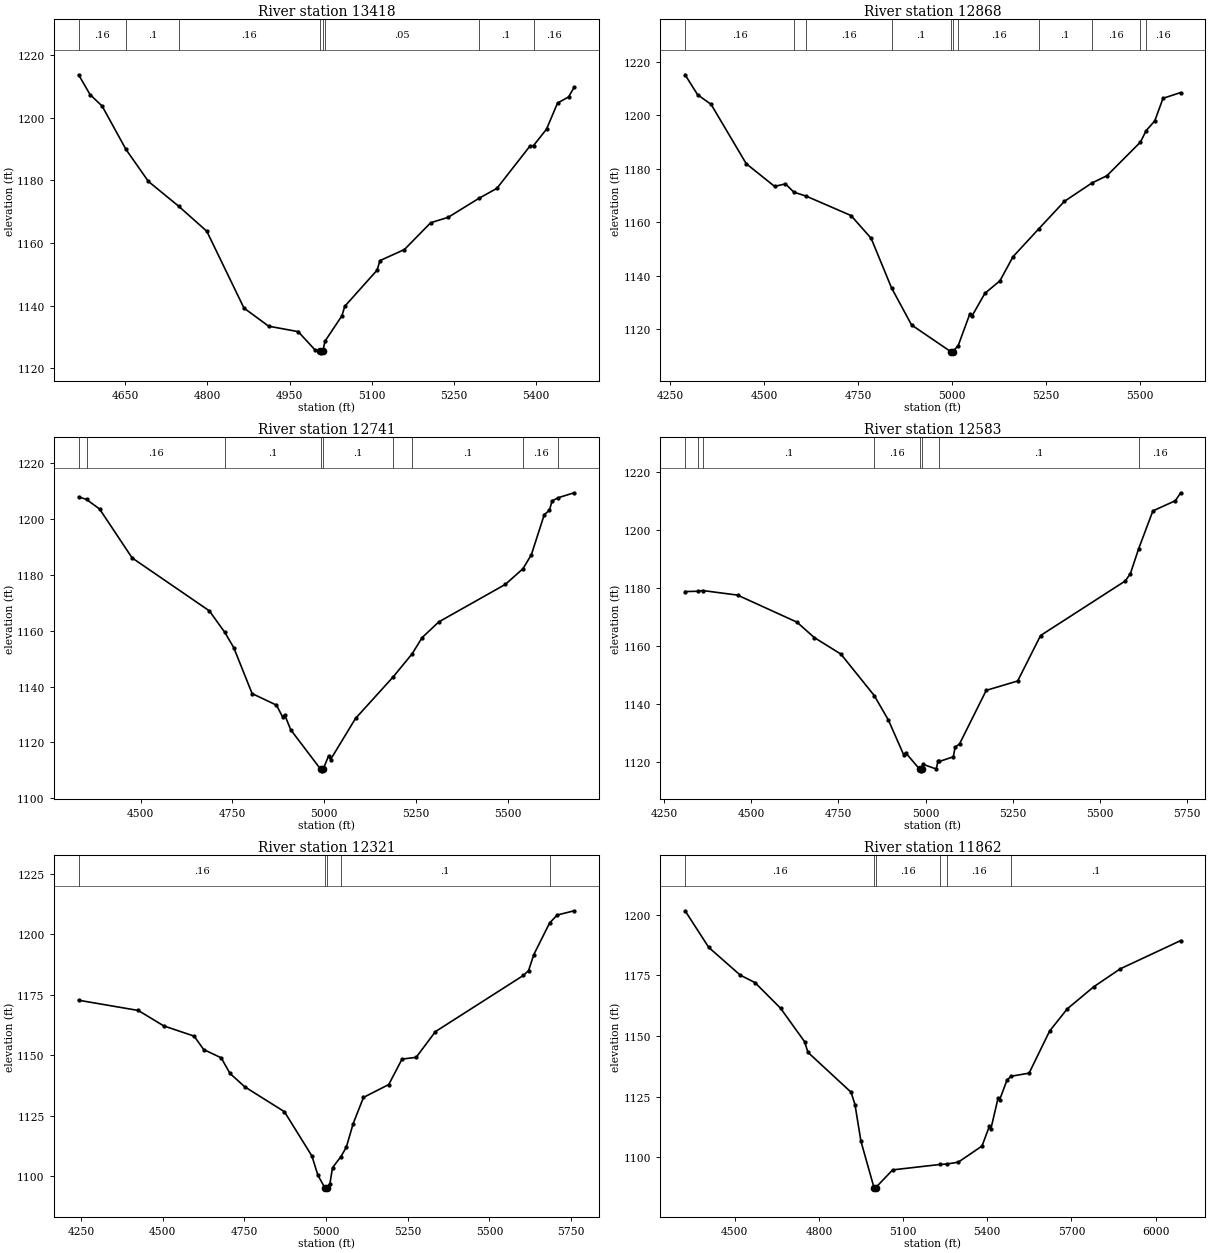
Type RM Length L Ch R = 1,13418,550,550,550
BEGIN DESCRIPTION:
HAMILTON CREEK TRIB 1 29.0
END DESCRIPTION:
XS GIS Cut Line= 4
      3001254.50     10078709.68      3001021.83     10078904.14
      3000761.42     10078987.48      3000803.08     10079313.87
#Sta/Elev= 30
  4564.5 1213.71  4585.4 1207.38  4607.4 1203.73  4651.0 1189.88  4692.0 1179.65
  4747.4 1171.72  4798.7 1163.75  4866.7 1139.20  4911.8 1133.41  4965.8 1131.67
  4997.3 1125.69  5004.8 1125.40  5007.5 1124.90  5010.8 1125.40  5014.8 1128.63
  5045.7 1136.73  5050.9 1139.76  5110.0 1151.31  5115.2 1154.35  5160.0 1157.90
  5208.0 1166.46  5239.8 1168.17  5296.3 1174.27  5328.9 1177.42  5389.3 1190.92
  5396.0 1191.12  5419.7 1196.35  5439.8 1204.68  5460.0 1206.63  5470.2 1209.73
#Mann=8,-1,0
  4564.5    0.16       0  4651.0     0.1       0  4747.4    0.16       0
  5004.8    0.07       0  5010.8    0.16       0  5014.8    0.05       0
  5296.3     0.1       0  5396.0    0.16       0
Bank Sta=5004.8,5010.8
Exp/Cntr=0.3,0.1

Type RM Length L Ch R = 1,12868,127,127,127
BEGIN DESCRIPTION:
Mapping XS 07a08e90
END DESCRIPTION:
XS GIS Cut Line= 4
      3000226.68     10078133.27      3000424.61     10078584.70
      3000556.56     10079077.75      3000761.39     10079317.30
#Sta/Elev= 30
  4289.2 1215.12  4322.5 1207.65  4358.3 1204.07  4451.8 1181.89  4527.3 1173.39
  4556.2 1174.33  4578.7 1171.23  4611.0 1169.77  4730.7 1162.49  4784.2 1153.98
  4838.5 1135.44  4891.8 1121.58  4995.5 1111.66  4998.3 1111.16  5001.5 1111.66
  5015.7 1113.82  5046.8 1125.71  5052.0 1124.80  5086.8 1133.39  5126.9 1138.09
  5161.7 1147.10  5230.4 1157.55  5298.5 1167.81  5371.2 1174.62  5411.5 1177.37
  5500.7 1189.94  5515.9 1194.23  5538.9 1197.89  5560.8 1206.32  5607.7 1208.48
#Mann=11,-1,0
  4289.2    0.16       0  4578.7     0.1       0  4611.0    0.16       0
  4838.5     0.1       0  4995.5    0.07       0  5001.5     0.1       0
  5015.7    0.16       0  5230.4     0.1       0  5371.2    0.16       0
  5500.7     0.1       0  5515.9    0.16       0
Bank Sta=4995.5,5001.5
Exp/Cntr=0.3,0.1

Type RM Length L Ch R = 1,12741,158,158,158
BEGIN DESCRIPTION:
HAMILTON CREEK TRIB 1 28.0
END DESCRIPTION:
XS GIS Cut Line= 5
      3000077.41     10078157.66      3000344.75     10078674.98
      3000386.42     10078897.20      3000372.53     10079081.23
      3000632.96     10079324.30
#Sta/Elev= 30
  4331.2 1207.90  4352.7 1206.94  4388.3 1203.53  4476.9 1186.02  4687.0 1167.09
  4729.0 1159.41  4753.6 1153.90  4803.5 1137.48  4869.9 1133.33  4886.5 1129.10
  4892.1 1129.94  4908.6 1124.52  4990.6 1110.32  4993.4 1109.82  4996.6 1110.32
  5012.0 1115.23  5017.1 1113.86  5085.2 1128.59  5187.7 1143.46  5239.2 1151.70
  5266.5 1157.52  5311.7 1163.12  5493.0 1176.55  5541.0 1182.16  5563.8 1187.15
  5599.0 1201.53  5613.2 1203.07  5620.0 1206.40  5636.8 1207.57  5680.4 1209.34
#Mann=9,-1,0
  4331.2     0.1       0  4352.7    0.16       0  4729.0     0.1       0
  4990.6    0.07       0  4996.6     0.1       0  5187.7    0.16       0
  5239.2     0.1       0  5541.0    0.16       0  5636.8     0.1       0
Bank Sta=4990.6,4996.6
Exp/Cntr=0.3,0.1

Type RM Length L Ch R = 1,12583,262,262,262
BEGIN DESCRIPTION:
Mapping XS e5c28808
END DESCRIPTION:
XS GIS Cut Line= 5
      2999931.57     10078188.89      3000185.03     10078668.03
      3000237.11     10078907.62      3000244.06     10079095.12
      3000598.22     10079365.94
#Sta/Elev= 30
  4310.3 1178.68  4346.9 1178.78  4360.8 1179.03  4460.6 1177.46  4631.0 1168.13
  4680.7 1162.82  4757.0 1157.12  4852.6 1142.83  4893.0 1134.42  4937.0 1122.42
  4942.2 1123.17  4983.2 1117.38  4985.9 1116.88  4989.2 1117.38  4991.3 1119.17
  5030.2 1117.52  5035.3 1120.13  5039.1 1120.10  5079.3 1121.73  5084.4 1124.98
  5097.5 1126.25  5173.7 1144.63  5263.8 1147.85  5329.4 1163.52  5572.5 1182.35
  5587.0 1184.88  5610.4 1193.36  5651.4 1206.48  5715.8 1209.99  5731.0 1212.73
#Mann=8,-1,0
  4310.3     0.1       0  4346.9    0.16       0  4360.8     0.1       0
  4852.6    0.16       0  4983.2    0.07       0  4989.2    0.16       0
  5039.1     0.1       0  5610.4    0.16       0
Bank Sta=4983.2,4989.2
Exp/Cntr=0.3,0.1

Type RM Length L Ch R = 1,12321,459,459,459
BEGIN DESCRIPTION:
HAMILTON CREEK TRIB 1 27.0
END DESCRIPTION:
XS GIS Cut Line= 4
      2999872.53     10078223.62      2999931.56     10078723.59
      3000070.44     10079147.20      3000563.52     10079428.46
#Sta/Elev= 30
  4242.3 1172.79  4424.8 1168.57  4502.7 1162.19  4595.7 1157.96  4625.1 1152.41
  4678.6 1149.00  4705.6 1142.53  4751.5 1136.94  4872.2 1126.72  4956.4 1108.40
  4974.4 1100.59  4995.5 1095.33  4998.2 1094.83  5001.5 1095.33  5011.5 1096.97
  5019.5 1103.59  5045.1 1108.13  5061.6 1112.00  5082.7 1121.78  5114.2 1132.62
  5191.5 1137.93  5232.3 1148.46  5275.5 1149.19  5334.5 1159.82  5603.9 1183.06
  5619.7 1185.07  5635.6 1191.64  5684.1 1204.75  5707.3 1208.02  5759.2 1209.77
#Mann=5,-1,0
  4242.3    0.16       0  4995.5    0.07       0  5001.5    0.16       0
  5045.1     0.1       0  5684.1    0.16       0
Bank Sta=4995.5,5001.5
Exp/Cntr=0.3,0.1

Type RM Length L Ch R = 1,11862,872,872,872
BEGIN DESCRIPTION:
HAMILTON CREEK TRIB 1 25.0
END DESCRIPTION:
XS GIS Cut Line= 4
      2999013.20     10078923.25      2999445.44     10079001.37
      2999815.24     10079381.57      3000570.45     10079636.78
#Sta/Elev= 30
  4322.7 1201.54  4407.0 1186.45  4519.1 1175.04  4571.9 1171.95  4663.4 1161.34
  4748.5 1147.63  4760.9 1143.19  4914.3 1126.80  4928.4 1121.69  4949.6 1106.60
  4996.2 1087.47  4998.9 1086.97  5002.2 1087.47  5062.7 1094.78  5230.8 1097.00
  5255.2 1097.18  5296.7 1097.96  5381.3 1104.61  5407.5 1112.72  5412.8 1111.59
  5438.9 1124.52  5444.2 1123.67  5470.4 1131.80  5485.0 1133.36  5549.1 1134.63
  5622.4 1151.99  5685.3 1161.13  5779.6 1170.22  5874.0 1177.61  6089.5 1189.25
#Mann=6,-1,0
  4322.7    0.16       0  4996.2    0.07       0  5002.2    0.16       0
  5230.8     0.1       0  5255.2    0.16       0  5485.0     0.1       0
Bank Sta=4996.2,5002.2
Exp/Cntr=0.3,0.1

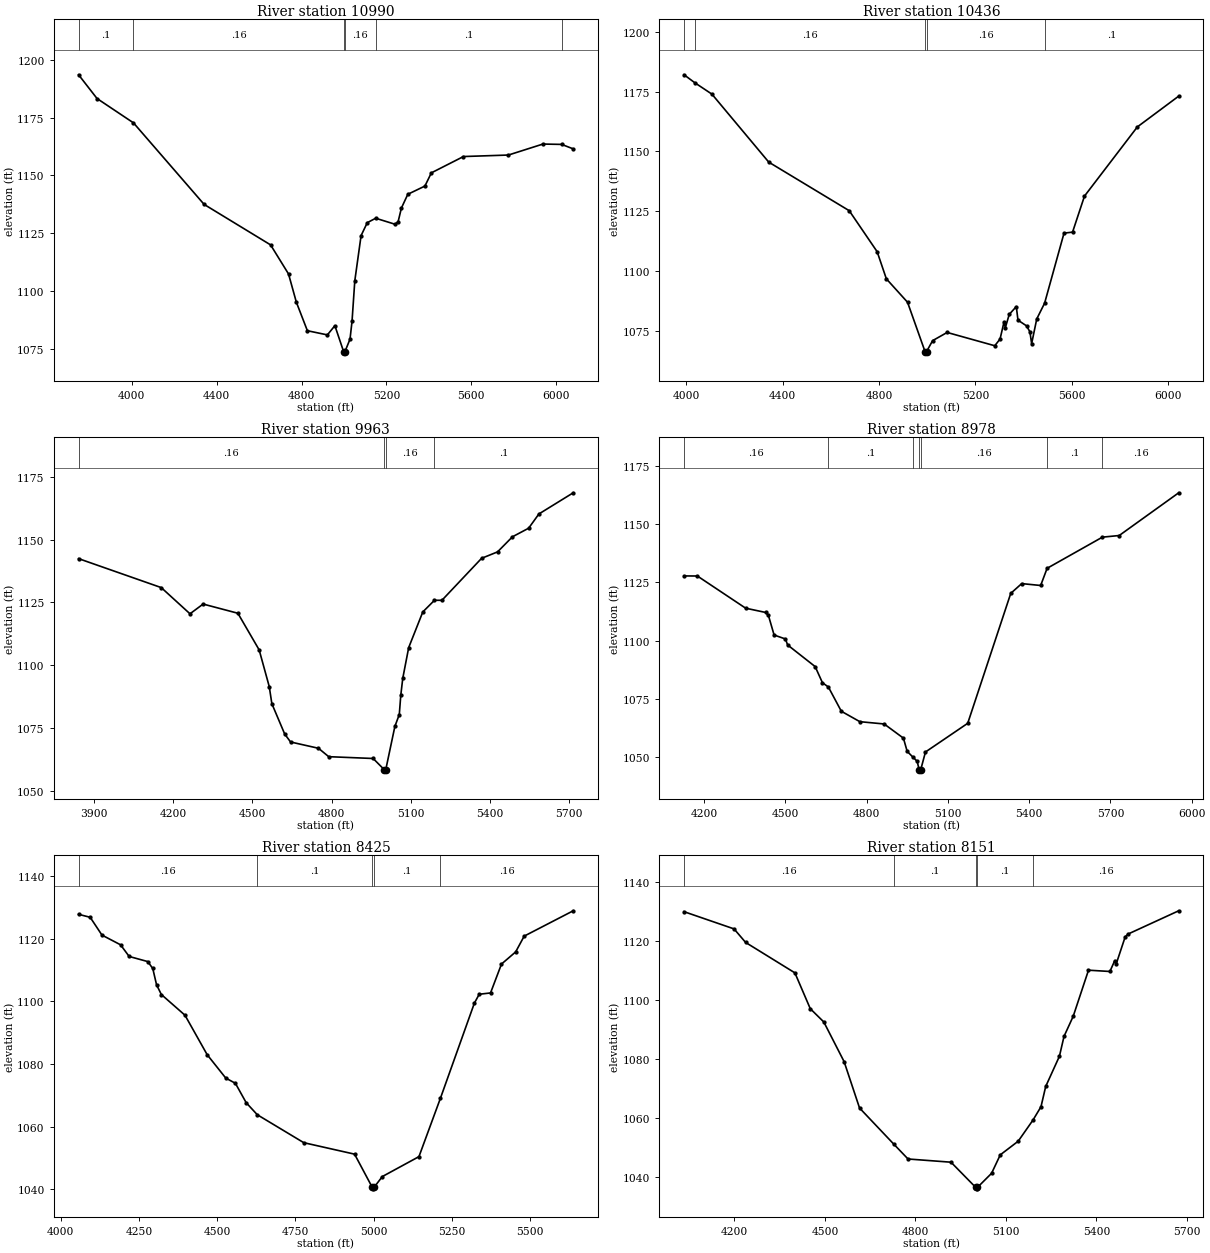
Type RM Length L Ch R = 1,10990,554,554,554
BEGIN DESCRIPTION:
HAMILTON CREEK TRIB 1 24.0
END DESCRIPTION:
XS GIS Cut Line= 4
      2998997.54     10079043.05      2999497.53     10079793.03
      2999945.44     10080069.07      3000841.26     10079949.28
#Sta/Elev= 30
  3749.4 1193.49  3836.3 1183.22  4008.2 1172.68  4341.1 1137.41  4654.3 1119.90
  4738.9 1107.32  4775.6 1095.15  4827.7 1082.77  4922.0 1080.96  4957.3 1084.96
  4998.6 1073.70  5001.3 1073.20  5004.6 1073.70  5028.7 1079.13  5038.2 1086.90
  5051.2 1104.38  5080.8 1123.91  5110.0 1129.51  5149.7 1131.43  5240.5 1128.84
  5255.3 1129.90  5270.8 1135.82  5301.0 1141.79  5381.7 1145.35  5412.0 1151.06
  5563.3 1158.12  5775.2 1158.77  5937.8 1163.52  6026.1 1163.37  6080.7 1161.44
#Mann=6,-1,0
  3749.4     0.1       0  4008.2    0.16       0  4998.6    0.07       0
  5004.6    0.16       0  5149.7     0.1       0  6026.1    0.16       0
Bank Sta=4998.6,5004.6
Exp/Cntr=0.3,0.1

Type RM Length L Ch R = 1,10436,473,473,473
BEGIN DESCRIPTION:
HAMILTON CREEK TRIB 1 23.0
END DESCRIPTION:
XS GIS Cut Line= 3
      2998544.40     10079912.82      2999752.74     10080558.66
      3000237.09     10081037.80
#Sta/Elev= 30
  3991.7 1182.13  4036.4 1178.78  4107.2 1174.02  4342.9 1145.54  4676.6 1125.20
  4792.4 1108.03  4830.6 1096.66  4918.4 1086.86  4991.1 1066.16  4993.9 1065.66
  4997.1 1066.16  5022.5 1070.77  5082.7 1074.20  5280.2 1068.63  5302.1 1071.44
  5318.4 1078.49  5324.1 1076.23  5340.3 1081.78  5369.5 1085.03  5376.5 1079.35
  5411.9 1076.96  5426.0 1074.46  5433.1 1069.50  5454.3 1079.86  5486.9 1086.46
  5567.4 1115.80  5602.8 1116.22  5652.3 1131.32  5871.5 1160.29  6043.1 1173.19
#Mann=5,-1,0
  3991.7     0.1       0  4036.4    0.16       0  4991.1    0.07       0
  4997.1    0.16       0  5486.9     0.1       0
Bank Sta=4991.1,4997.1
Exp/Cntr=0.3,0.1

Type RM Length L Ch R = 1,9963,985,985,985
BEGIN DESCRIPTION:
HAMILTON CREEK TRIB 1 21.0
END DESCRIPTION:
XS GIS Cut Line= 3
      2998429.78     10080501.36      2999158.99     10080589.91
      3000174.00     10081105.22
#Sta/Elev= 30
  3841.8 1142.40  4154.8 1130.86  4263.6 1120.42  4313.3 1124.30  4444.9 1120.64
  4525.5 1106.04  4563.7 1091.42  4573.6 1084.60  4622.1 1072.54  4644.4 1069.35
  4750.1 1066.84  4788.9 1063.49  4957.1 1062.77  4998.9 1058.35  5001.7 1057.85
  5004.9 1058.35  5039.4 1075.56  5056.1 1080.29  5061.7 1087.92  5069.2 1094.69
  5091.7 1106.97  5145.1 1121.16  5189.3 1125.81  5217.5 1125.80  5367.7 1142.53
  5428.1 1145.09  5484.6 1151.11  5545.8 1154.52  5584.7 1160.20  5714.7 1168.64
#Mann=4,-1,0
  3841.8    0.16       0  4998.9    0.07       0  5004.9    0.16       0
  5189.3     0.1       0
Bank Sta=4998.9,5004.9
Exp/Cntr=0.3,0.1

Type RM Length L Ch R = 1,8978,553,553,553
BEGIN DESCRIPTION:
HAMILTON CREEK TRIB 1 20.0
END DESCRIPTION:
XS GIS Cut Line= 4
      2998351.73     10081131.58      2998971.49     10081329.49
      2999544.40     10081225.32      3000138.20     10081240.95
#Sta/Elev= 30
  4125.4 1127.73  4174.5 1127.70  4352.9 1113.89  4426.4 1112.07  4436.9 1110.81
  4457.9 1102.39  4499.9 1100.68  4507.8 1098.13  4609.6 1088.84  4636.4 1081.93
  4658.3 1080.10  4706.2 1069.69  4774.7 1065.22  4864.4 1064.24  4935.5 1058.16
  4949.4 1052.49  4969.2 1050.19  4986.4 1048.21  4993.5 1044.64  4996.3 1044.14
  4999.5 1044.64  5016.9 1052.22  5173.0 1064.53  5331.9 1120.24  5372.4 1124.44
  5442.4 1123.63  5466.2 1131.00  5670.4 1144.36  5732.5 1145.06  5952.3 1163.39
#Mann=7,-1,0
  4125.4    0.16       0  4658.3     0.1       0  4969.2    0.16       0
  4993.5    0.07       0  4999.5    0.16       0  5466.2     0.1       0
  5670.4    0.16       0
Bank Sta=4993.5,4999.5
Exp/Cntr=0.3,0.1

Type RM Length L Ch R = 1,8425,274,274,274
BEGIN DESCRIPTION:
HAMILTON CREEK TRIB 1 19.0
END DESCRIPTION:
XS GIS Cut Line= 3
      2998330.82     10081240.93      2999377.74     10081824.28
      2999704.70     10082021.50
#Sta/Elev= 30
  4057.3 1127.75  4094.3 1126.80  4132.0 1121.12  4191.4 1118.02  4218.9 1114.30
  4278.3 1112.67  4294.3 1110.46  4306.4 1105.26  4321.7 1102.16  4397.2 1095.55
  4468.1 1082.95  4527.5 1075.49  4558.3 1073.82  4592.7 1067.64  4628.2 1063.79
  4776.7 1054.87  4939.0 1051.21  4995.4 1040.64  4998.2 1040.14  5001.4 1040.64
  5027.7 1044.06  5144.7 1050.42  5213.3 1069.05  5321.7 1099.39  5337.2 1102.24
  5373.4 1102.66  5408.4 1111.88  5453.7 1115.76  5480.9 1120.79  5637.6 1128.88
#Mann=5,-1,0
  4057.3    0.16       0  4628.2     0.1       0  4995.4    0.07       0
  5001.4     0.1       0  5213.3    0.16       0
Bank Sta=4995.4,5001.4
Exp/Cntr=0.3,0.1

Type RM Length L Ch R = 1,8151,308,308,308
BEGIN DESCRIPTION:
Mapping XS 43350d37
END DESCRIPTION:
XS GIS Cut Line= 4
      2998178.62     10081646.00      2998899.13     10081793.58
      2999157.38     10081999.74      2999723.63     10082093.03
#Sta/Elev= 30
  4033.1 1129.94  4198.8 1124.10  4237.1 1119.51  4400.5 1109.18  4451.5 1097.02
  4496.3 1092.52  4563.7 1079.04  4614.8 1063.32  4728.3 1051.06  4775.5 1046.02
  4918.0 1044.93  4999.8 1036.39  5002.6 1035.89  5005.8 1036.39  5052.5 1041.16
  5081.3 1047.42  5140.7 1052.05  5189.8 1059.23  5216.3 1063.75  5231.9 1070.62
  5277.4 1080.88  5292.7 1087.64  5323.1 1094.44  5373.8 1110.09  5444.7 1109.65
  5460.9 1113.35  5466.0 1112.32  5495.4 1121.39  5505.5 1122.38  5672.9 1130.25
#Mann=5,-1,0
  4033.1    0.16       0  4728.3     0.1       0  4999.8    0.07       0
  5005.8     0.1       0  5189.8    0.16       0
Bank Sta=4999.8,5005.8
Exp/Cntr=0.3,0.1

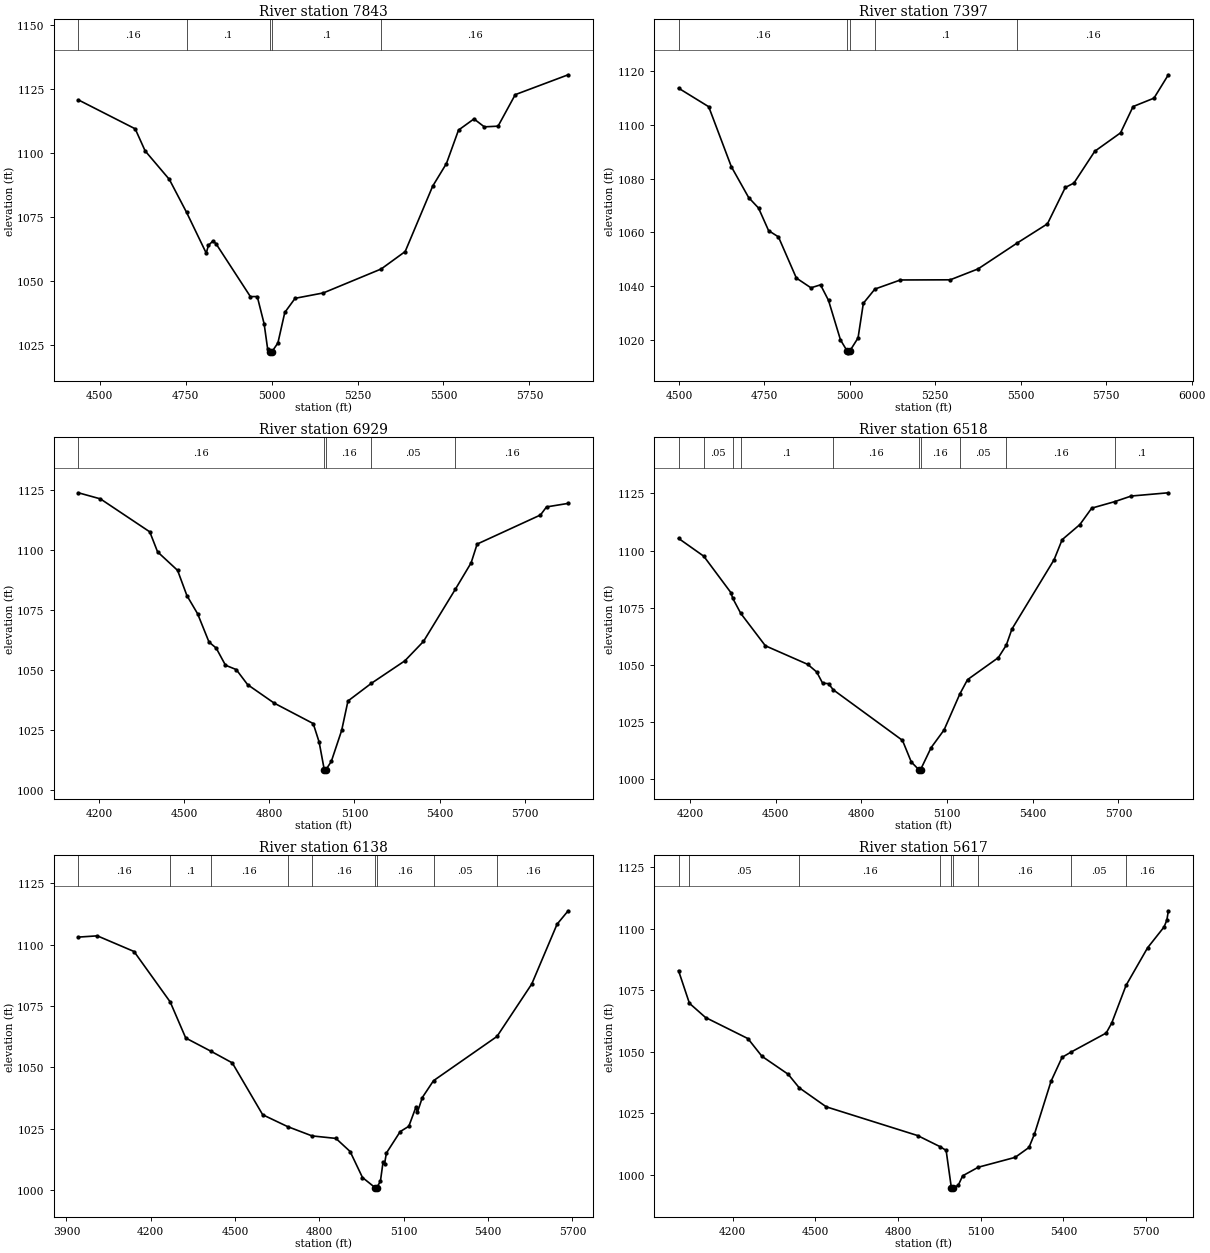
Type RM Length L Ch R = 1,7843,446,446,446
BEGIN DESCRIPTION:
HAMILTON CREEK TRIB 1 18.0
END DESCRIPTION:
XS GIS Cut Line= 3
      2998403.81     10081865.97      2998711.07     10082110.74
      2999742.30     10082136.78
#Sta/Elev= 30
  4438.2 1120.83  4603.5 1109.50  4632.4 1100.86  4702.8 1089.69  4753.0 1076.77
  4810.1 1060.82  4816.5 1063.85  4829.4 1065.56  4838.4 1064.54  4938.5 1043.80
  4958.5 1043.82  4978.5 1033.12  4988.5 1023.47  4995.5 1022.28  4998.2 1021.78
  5001.5 1022.28  5018.5 1025.64  5038.5 1037.59  5068.5 1043.13  5150.6 1045.24
  5318.9 1054.62  5388.6 1061.44  5468.6 1087.05  5508.6 1095.91  5543.7 1109.00
  5588.7 1113.38  5618.7 1110.27  5658.7 1110.54  5708.7 1122.88  5862.6 1130.66
#Mann=5,-1,0
  4438.2    0.16       0  4753.0     0.1       0  4995.5    0.07       0
  5001.5     0.1       0  5318.9    0.16       0
Bank Sta=4995.5,5001.5
Exp/Cntr=0.3,0.1

Type RM Length L Ch R = 1,7397,468,468,468
BEGIN DESCRIPTION:
HAMILTON CREEK TRIB 1 16.0
END DESCRIPTION:
XS GIS Cut Line= 3
      2998382.91     10082287.80      2999132.94     10082740.95
      2999679.82     10082845.12
#Sta/Elev= 30
  4498.8 1113.78  4587.1 1106.86  4653.3 1084.52  4703.9 1073.03  4732.9 1069.10
  4762.3 1060.69  4791.1 1058.36  4843.5 1043.03  4886.2 1039.39  4914.2 1040.50
  4937.6 1034.70  4972.6 1019.98  4993.0 1015.66  4995.7 1015.16  4999.0 1015.66
  5024.0 1020.71  5039.5 1033.63  5073.4 1038.93  5147.9 1042.31  5293.7 1042.37
  5375.1 1046.43  5490.2 1056.13  5578.1 1063.23  5630.3 1076.77  5655.6 1078.42
  5716.6 1090.27  5791.9 1097.12  5828.6 1106.92  5889.7 1110.05  5931.8 1118.76
#Mann=5,-1,0
  4498.8    0.16       0  4993.0    0.07       0  4999.0    0.16       0
  5073.4     0.1       0  5490.2    0.16       0
Bank Sta=4993,4999
Exp/Cntr=0.3,0.1

Type RM Length L Ch R = 1,6929,411,411,411
BEGIN DESCRIPTION:
HAMILTON CREEK TRIB 1 15.0
END DESCRIPTION:
XS GIS Cut Line= 4
      2998200.66     10082194.11      2998393.36     10082819.07
      2998893.36     10083162.82      2999330.36     10083318.90
#Sta/Elev= 30
  4127.8 1123.96  4205.5 1121.41  4379.3 1107.64  4406.8 1099.28  4477.3 1091.54
  4510.0 1081.03  4547.9 1073.39  4587.8 1061.63  4613.2 1059.08  4645.9 1051.93
  4683.8 1050.11  4723.9 1043.81  4817.4 1036.10  4954.8 1027.56  4975.7 1019.82
  4993.7 1008.31  4996.4 1007.81  4999.7 1008.31  5018.6 1011.76  5055.0 1024.70
  5077.2 1036.99  5159.5 1044.36  5277.5 1053.76  5343.1 1061.87  5455.5 1083.70
  5510.8 1094.68  5532.0 1102.53  5755.0 1114.68  5776.3 1118.05  5852.6 1119.53
#Mann=5,-1,0
  4127.8    0.16       0  4993.7    0.07       0  4999.7    0.16       0
  5159.5    0.05       0  5455.5    0.16       0
Bank Sta=4993.7,4999.7
Exp/Cntr=0.3,0.1

Type RM Length L Ch R = 1,6518,380,380,380
BEGIN DESCRIPTION:
HAMILTON CREEK TRIB 1 14.0
END DESCRIPTION:
XS GIS Cut Line= 2
      2997591.27     10083089.90      2999247.52     10083532.61
#Sta/Elev= 30
  4160.2 1105.32  4248.6 1097.51  4343.6 1081.57  4349.6 1079.20  4378.2 1072.47
  4464.1 1058.34  4612.7 1050.19  4643.8 1046.87  4664.5 1041.98  4685.2 1041.77
  4701.7 1039.08  4944.0 1016.96  4975.0 1007.48  5001.3 1004.13  5004.0 1003.63
  5007.3 1004.13  5044.3 1013.78  5089.6 1021.52  5144.9 1037.28  5171.7 1043.52
  5279.5 1053.14  5307.4 1058.62  5327.0 1065.63  5474.7 1095.99  5502.9 1104.75
  5565.0 1111.37  5606.4 1118.54  5686.7 1121.38  5744.8 1123.84  5874.6 1125.26
#Mann=10,-1,0
  4160.2     0.1       0  4248.6    0.05       0  4349.6    0.16       0
  4378.2     0.1       0  4701.7    0.16       0  5001.3    0.07       0
  5007.3    0.16       0  5144.9    0.05       0  5307.4    0.16       0
  5686.7     0.1       0
Bank Sta=5001.3,5007.3
Exp/Cntr=0.3,0.1

Type RM Length L Ch R = 1,6138,521,521,521
BEGIN DESCRIPTION:
HAMILTON CREEK TRIB 1 13.0
END DESCRIPTION:
XS GIS Cut Line= 4
      2997362.10     10083282.61      2998185.03     10083621.16
      2998643.36     10083787.82      2999007.98     10083793.03
#Sta/Elev= 30
  3942.5 1103.13  4010.0 1103.64  4140.6 1097.26  4269.2 1076.70  4324.5 1061.99
  4414.5 1056.58  4490.0 1051.86  4598.2 1030.71  4686.6 1025.89  4773.7 1022.09
  4858.6 1021.07  4909.1 1015.73  4953.1 1005.13  4997.9 1001.01  5000.6 1000.51
  5003.9 1001.01  5016.9 1003.61  5026.2 1011.38  5031.5 1010.63  5038.2 1015.10
  5087.3 1023.85  5117.9 1026.01  5143.2 1033.82  5148.5 1031.72  5165.9 1037.73
  5205.7 1044.59  5431.5 1062.63  5555.2 1084.02  5645.2 1108.39  5684.7 1113.86
#Mann=9,-1,0
  3942.5    0.16       0  4269.2     0.1       0  4414.5    0.16       0
  4686.6    0.05       0  4773.7    0.16       0  4997.9    0.07       0
  5003.9    0.16       0  5205.7    0.05       0  5431.5    0.16       0
Bank Sta=4997.9,5003.9
Exp/Cntr=0.3,0.1

Type RM Length L Ch R = 1,5617,604,604,604
BEGIN DESCRIPTION:
HAMILTON CREEK TRIB 1 12.0
END DESCRIPTION:
XS GIS Cut Line= 4
      2997190.28     10084365.94      2998007.94     10084225.32
      2998304.82     10084063.87      2998913.85     10084043.04
#Sta/Elev= 30
  4003.8 1082.99  4043.3 1069.72  4101.8 1063.93  4255.6 1055.35  4306.4 1048.15
  4401.6 1040.84  4441.6 1035.34  4539.7 1027.59  4871.1 1015.90  4952.2 1011.40
  4974.6 1009.87  4993.5  994.72  4996.2  994.22  4999.5  994.72  5018.3  995.59
  5034.5  999.51  5091.1 1003.01  5225.1 1007.03  5275.1 1011.05  5295.1 1016.52
  5355.2 1037.99  5395.2 1047.72  5428.5 1049.90  5555.3 1057.61  5575.3 1061.66
  5627.4 1077.02  5705.4 1092.28  5765.4 1100.79  5775.4 1103.57  5780.8 1107.35
#Mann=9,-1,0
  4003.8    0.16       0  4043.3    0.05       0  4441.6    0.16       0
  4952.2     0.1       0  4993.5    0.07       0  4999.5     0.1       0
  5091.1    0.16       0  5428.5    0.05       0  5627.4    0.16       0
Bank Sta=4993.5,4999.5
Exp/Cntr=0.3,0.1

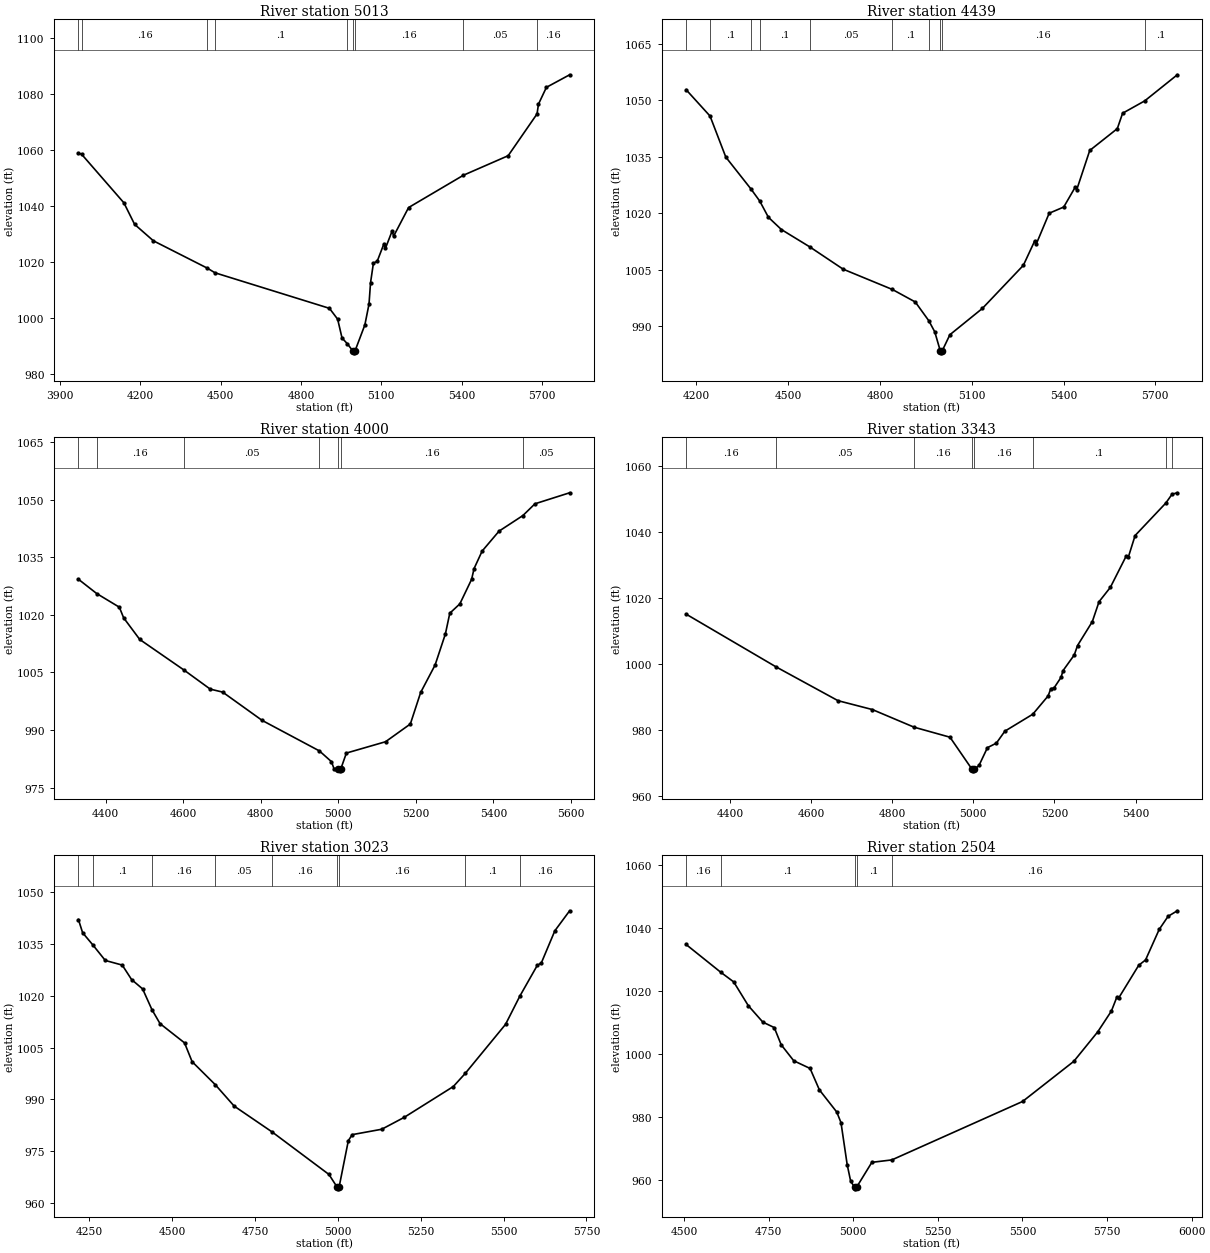
Type RM Length L Ch R = 1,5013,574,574,574
BEGIN DESCRIPTION:
HAMILTON CREEK TRIB 1 11.0
END DESCRIPTION:
XS GIS Cut Line= 4
      2997408.99     10084464.91      2998169.40     10084428.45
      2998570.44     10084574.28      2999169.39     10084334.71
#Sta/Elev= 30
  3969.7 1058.83  3981.8 1058.38  4139.4 1041.08  4179.4 1033.40  4249.5 1027.53
  4450.5 1017.79  4479.5 1016.12  4906.5 1003.45  4937.1  999.58  4953.4  992.88
  4973.4  990.80  4995.2  988.08  4998.0  987.58  5001.2  988.08  5038.6  997.53
  5054.1 1004.96  5059.8 1012.57  5070.5 1019.55  5084.7 1020.24  5110.0 1026.52
  5115.3 1024.83  5140.6 1031.08  5145.9 1029.18  5201.8 1039.39  5406.3 1050.91
  5573.4 1057.88  5681.2 1072.79  5686.5 1076.27  5716.1 1082.26  5802.8 1086.74
#Mann=9,-1,0
  3969.7    0.05       0  3981.8    0.16       0  4450.5    0.05       0
  4479.5     0.1       0  4973.4    0.16       0  4995.2    0.07       0
  5001.2    0.16       0  5406.3    0.05       0  5681.2    0.16       0
Bank Sta=4995.2,5001.2
Exp/Cntr=0.3,0.1

Type RM Length L Ch R = 1,4439,439,439,439
BEGIN DESCRIPTION:
HAMILTON CREEK TRIB 1 10.0
END DESCRIPTION:
XS GIS Cut Line= 4
      2997429.82     10084772.20      2998044.40     10084855.53
      2998382.94     10085199.28      2998872.54     10085313.87
#Sta/Elev= 30
  4166.4 1052.83  4244.7 1045.82  4296.2 1034.92  4378.2 1026.47  4407.1 1023.24
  4435.4 1018.93  4477.9 1015.67  4570.5 1011.07  4679.7 1005.14  4840.8  999.74
  4915.5  996.42  4959.7  991.44  4979.2  988.48  4997.3  983.41  5000.1  982.91
  5003.3  983.41  5028.6  987.72  5134.8  994.71  5268.7 1006.16  5305.5 1012.59
  5310.6 1011.76  5353.1 1020.00  5400.7 1021.65  5438.1 1026.91  5443.2 1026.26
  5485.7 1036.68  5575.8 1042.48  5593.1 1046.57  5665.3 1049.85  5771.9 1056.79
#Mann=10,-1,0
  4166.4    0.16       0  4244.7     0.1       0  4378.2    0.05       0
  4407.1     0.1       0  4570.5    0.05       0  4840.8     0.1       0
  4959.7    0.16       0  4997.3    0.07       0  5003.3    0.16       0
  5665.3     0.1       0
Bank Sta=4997.3,5003.3
Exp/Cntr=0.3,0.1

Type RM Length L Ch R = 1,4000,657,657,657
BEGIN DESCRIPTION:
HAMILTON CREEK TRIB 1 9.0
END DESCRIPTION:
XS GIS Cut Line= 3
      2997388.14     10085194.07      2998330.86     10085501.37
      2998549.58     10085668.01
#Sta/Elev= 30
  4330.0 1029.28  4377.1 1025.56  4435.5 1022.00  4446.6 1019.23  4488.1 1013.60
  4601.8 1005.66  4669.9 1000.66  4701.8  999.89  4803.6  992.52  4951.3  984.57
  4982.4  981.77  4989.0  979.92  5000.5  979.88  5003.2  979.38  5006.5  979.88
  5020.9  984.01  5121.9  986.96  5185.8  991.58  5212.4  999.79  5249.6 1006.94
  5276.2 1015.05  5287.5 1020.43  5313.4 1022.86  5343.7 1029.24  5350.1 1032.06
  5370.9 1036.62  5414.5 1041.81  5476.0 1045.87  5507.1 1048.93  5596.5 1051.80
#Mann=7,-1,0
  4330.0     0.1       0  4377.1    0.16       0  4601.8    0.05       0
  4951.3    0.16       0  5000.5    0.07       0  5006.5    0.16       0
  5476.0    0.05       0
Bank Sta=5000.5,5006.5
Exp/Cntr=0.3,0.1

Type RM Length L Ch R = 1,3343,320,320,320
BEGIN DESCRIPTION:
HAMILTON CREEK TRIB 1 7.0
END DESCRIPTION:
XS GIS Cut Line= 3
      2997398.59     10085386.81      2997992.32     10086095.12
      2998247.49     10086225.31
#Sta/Elev= 30
  4292.1 1015.10  4513.7  999.14  4666.5  988.90  4751.2  986.21  4854.1  980.87
  4942.5  977.84  4996.7  968.16  4999.5  967.66  5002.7  968.16  5014.0  969.28
  5034.8  974.67  5056.9  976.05  5077.8  979.67  5146.6  984.80  5184.4  990.34
  5191.0  992.53  5198.8  992.72  5216.3  995.96  5221.0  997.97  5248.8 1002.73
  5256.9 1005.60  5293.3 1012.82  5309.9 1018.86  5337.7 1023.18  5376.6 1032.63
  5382.2 1032.40  5398.8 1038.89  5474.4 1048.71  5489.9 1051.40  5502.8 1051.83
#Mann=8,-1,0
  4292.1    0.16       0  4513.7    0.05       0  4854.1    0.16       0
  4996.7    0.07       0  5002.7    0.16       0  5146.6     0.1       0
  5474.4    0.16       0  5489.9     0.1       0
Bank Sta=4996.7,5002.7
Exp/Cntr=0.3,0.1

Type RM Length L Ch R = 1,3023,519,519,519
BEGIN DESCRIPTION:
HAMILTON CREEK TRIB 1 6.0
END DESCRIPTION:
XS GIS Cut Line= 4
      2997013.14     10085662.82      2997445.44     10085865.95
      2997679.82     10086251.37      2998200.47     10086438.80
#Sta/Elev= 30
  4217.4 1042.12  4230.1 1038.29  4261.1 1034.74  4298.5 1030.26  4349.6 1028.92
  4378.0 1024.71  4411.1 1022.02  4439.1 1016.04  4463.6 1011.97  4537.6 1006.39
  4560.4 1000.95  4630.0  994.31  4687.3  988.08  4801.9  980.58  4973.3  968.28
  4997.9  964.61  5000.6  964.11  5003.9  964.61  5031.8  978.08  5043.6  979.81
  5132.6  981.37  5200.3  984.81  5348.5  993.74  5384.5  997.54  5506.1 1011.75
  5549.3 1019.94  5601.7 1028.81  5614.2 1029.57  5654.9 1038.86  5699.5 1044.65
#Mann=9,-1,0
  4217.4    0.16       0  4261.1     0.1       0  4439.1    0.16       0
  4630.0    0.05       0  4801.9    0.16       0  4997.9    0.07       0
  5003.9    0.16       0  5384.5     0.1       0  5549.3    0.16       0
Bank Sta=4997.9,5003.9
Exp/Cntr=0.3,0.1

Type RM Length L Ch R = 1,2504,727,727,727
BEGIN DESCRIPTION:
HAMILTON CREEK TRIB 1 5.0
END DESCRIPTION:
XS GIS Cut Line= 3
      2996794.41     10086579.49      2997481.90     10086423.24
      2998221.48     10086522.20
#Sta/Elev= 30
  4506.5 1034.71  4608.4 1025.93  4647.2 1022.82  4690.3 1015.27  4733.3 1010.04
  4767.0 1008.31  4787.5 1002.84  4824.6  997.76  4872.8  995.32  4900.4  988.50
  4951.6  981.48  4964.1  978.12  4982.4  964.77  4992.6  959.55  5004.1  957.57
  5006.9  957.07  5010.1  957.57  5055.3  965.49  5114.3  966.26  5500.6  984.83
  5652.0  997.59  5722.6 1006.95  5763.0 1013.57  5779.4 1018.08  5784.5 1017.71
  5843.7 1028.10  5863.9 1029.80  5904.2 1039.50  5930.5 1043.66  5957.7 1045.42
#Mann=5,-1,0
  4506.5    0.16       0  4608.4     0.1       0  5004.1    0.07       0
  5010.1     0.1       0  5114.3    0.16       0
Bank Sta=5004.1,5010.1
Exp/Cntr=0.3,0.1

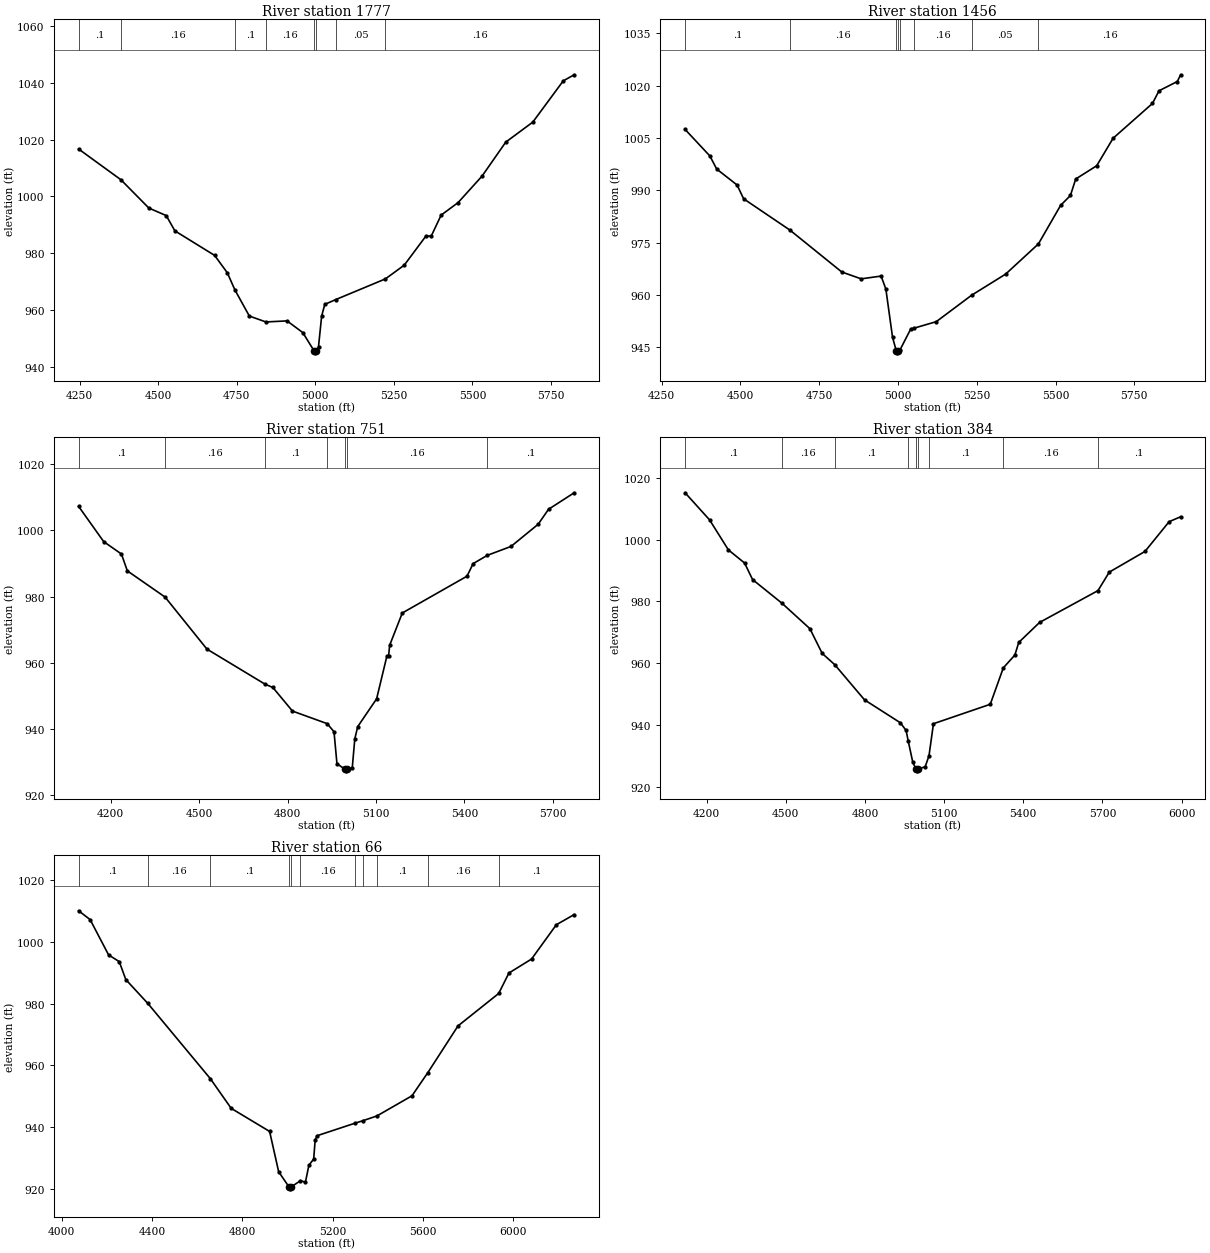
Type RM Length L Ch R = 1,1777,321,321,321
BEGIN DESCRIPTION:
HAMILTON CREEK TRIB 1 4.0
END DESCRIPTION:
XS GIS Cut Line= 4
      2996935.06     10086897.21      2997356.90     10087027.41
      2997914.19     10087027.41      2998450.68     10086813.85
#Sta/Elev= 30
  4247.2 1016.69  4381.6 1005.87  4470.5  995.89  4525.9  993.23  4553.3  987.85
  4679.9  979.18  4720.2  973.05  4744.2  967.04  4790.2  957.81  4842.9  955.73
  4910.2  956.10  4960.2  951.98  4997.2  945.34  5000.0  944.84  5003.2  945.34
  5010.2  947.02  5020.2  957.82  5030.2  961.93  5064.7  963.60  5223.0  970.91
  5282.9  975.75  5351.7  985.99  5369.0  986.05  5400.2  993.39  5454.2  997.81
  5530.4 1007.15  5605.8 1019.13  5691.9 1026.19  5788.7 1040.73  5823.4 1042.87
#Mann=8,-1,0
  4247.2     0.1       0  4381.6    0.16       0  4744.2     0.1       0
  4842.9    0.16       0  4997.2    0.07       0  5003.2    0.16       0
  5064.7    0.05       0  5223.0    0.16       0
Bank Sta=4997.2,5003.2
Exp/Cntr=0.3,0.1

Type RM Length L Ch R = 1,1456,705,705,705
BEGIN DESCRIPTION:
HAMILTON CREEK TRIB 1 3.0
END DESCRIPTION:
XS GIS Cut Line= 4
      2997065.22     10087720.13      2997466.28     10087423.24
      2997898.57     10087141.99      2998434.29     10086985.95
#Sta/Elev= 30
  4324.3 1007.43  4403.0  999.82  4424.6  996.07  4489.3  991.49  4510.1  987.54
  4656.9  978.57  4821.5  966.55  4883.1  964.58  4946.4  965.38  4961.5  961.64
  4982.6  947.86  4994.7  943.86  4997.5  943.36  5000.7  943.86  5005.8  944.11
  5040.6  950.24  5050.0  950.41  5121.6  952.31  5233.6  959.88  5341.6  965.94
  5445.6  974.60  5516.0  985.64  5547.2  988.49  5564.0  993.22  5630.5  997.01
  5682.6 1004.90  5807.6 1014.89  5828.4 1018.52  5886.4 1021.18  5897.0 1023.11
#Mann=8,-1,0
  4324.3     0.1       0  4656.9    0.16       0  4994.7    0.07       0
  5000.7    0.16       0  5005.8     0.1       0  5050.0    0.16       0
  5233.6    0.05       0  5445.6    0.16       0
Bank Sta=4994.7,5000.7
Exp/Cntr=0.3,0.1

Type RM Length L Ch R = 1,751,367,367,367
BEGIN DESCRIPTION:
HAMILTON CREEK TRIB 1 2.0
END DESCRIPTION:
XS GIS Cut Line= 4
      2997143.35     10087782.62      2997882.94     10087766.99
      2998190.24     10087803.45      2998669.41     10087391.99
#Sta/Elev= 30
  4091.3 1007.23  4176.4  996.58  4236.5  992.84  4256.5  987.75  4384.5  979.83
  4526.5  964.11  4723.9  953.49  4750.1  952.51  4816.6  945.38  4934.4  941.58
  4957.5  939.14  4967.5  929.46  4994.7  927.82  4997.5  927.32  5000.7  927.82
  5019.3  928.10  5028.0  936.99  5038.0  940.69  5102.0  949.08  5137.1  962.08
  5142.6  962.08  5146.3  965.28  5189.1  975.02  5408.5  986.14  5429.4  989.94
  5477.6  992.45  5557.8  995.13  5650.0 1001.84  5685.1 1006.36  5772.1 1011.35
#Mann=7,-1,0
  4091.3     0.1       0  4384.5    0.16       0  4723.9     0.1       0
  4934.4    0.16       0  4994.7    0.07       0  5000.7    0.16       0
  5477.6     0.1       0
Bank Sta=4994.7,5000.7
Exp/Cntr=0.3,0.1

Type RM Length L Ch R = 1,384,318,318,318
BEGIN DESCRIPTION:
Mapping XS fc339d8d
END DESCRIPTION:
XS GIS Cut Line= 4
      2997137.22     10087999.19      2997955.39     10088157.61
      2998191.94     10088083.83      2998673.55     10087448.87
#Sta/Elev= 30
  4118.4 1015.10  4211.3 1006.33  4282.6  996.63  4343.8  992.41  4374.1  987.06
  4485.2  979.43  4591.4  971.18  4638.0  963.19  4685.3  959.57  4798.4  948.18
  4934.5  940.76  4956.0  938.28  4963.7  935.02  4981.4  927.99  4993.9  925.74
  4996.6  925.24  4999.9  925.74  5028.3  926.56  5042.7  930.09  5059.7  940.47
  5275.0  946.75  5324.4  958.51  5368.3  962.67  5382.9  966.74  5461.9  973.20
  5683.2  983.48  5726.1  989.46  5861.3  996.14  5952.9 1005.76  5996.5 1007.35
#Mann=9,-1,0
  4118.4     0.1       0  4485.2    0.16       0  4685.3     0.1       0
  4963.7    0.16       0  4993.9    0.07       0  4999.9    0.16       0
  5042.7     0.1       0  5324.4    0.16       0  5683.2     0.1       0
Bank Sta=4993.9,4999.9
Exp/Cntr=0.3,0.1

Type RM Length L Ch R = 1,66,0,0,0
BEGIN DESCRIPTION:
HAMILTON CREEK TRIB 1 1.0
END DESCRIPTION:
XS GIS Cut Line= 4
      2997176.30     10088148.93      2997916.33     10088463.60
      2998111.64     10088454.92      2998743.90     10087439.42
#Sta/Elev= 30
  4074.5 1010.08  4125.4 1007.22  4207.3  995.77  4254.5  993.60  4283.6  987.78
  4381.3  980.03  4658.2  955.65  4750.6  946.03  4920.8  938.55  4960.9  925.48
  5007.9  920.44  5010.7  919.94  5013.9  920.44  5057.6  922.59  5079.5  922.10
  5094.9  927.59  5116.1  929.60  5122.7  935.80  5131.5  937.17  5297.2  941.17
  5335.1  942.05  5396.0  943.56  5551.6  950.10  5621.8  957.60  5755.8  972.77
  5936.0  983.28  5981.2  989.90  6081.6  994.44  6191.3 1005.55  6270.4 1008.85
#Mann=11,-1,0
  4074.5     0.1       0  4381.3    0.16       0  4658.2     0.1       0
  5007.9    0.07       0  5013.9     0.1       0  5057.6    0.16       0
  5297.2     0.1       0  5335.1    0.16       0  5396.0     0.1       0
  5621.8    0.16       0  5936.0     0.1       0
Bank Sta=5007.9,5013.9
Exp/Cntr=0.3,0.1

Chan Stop Cuts=-1