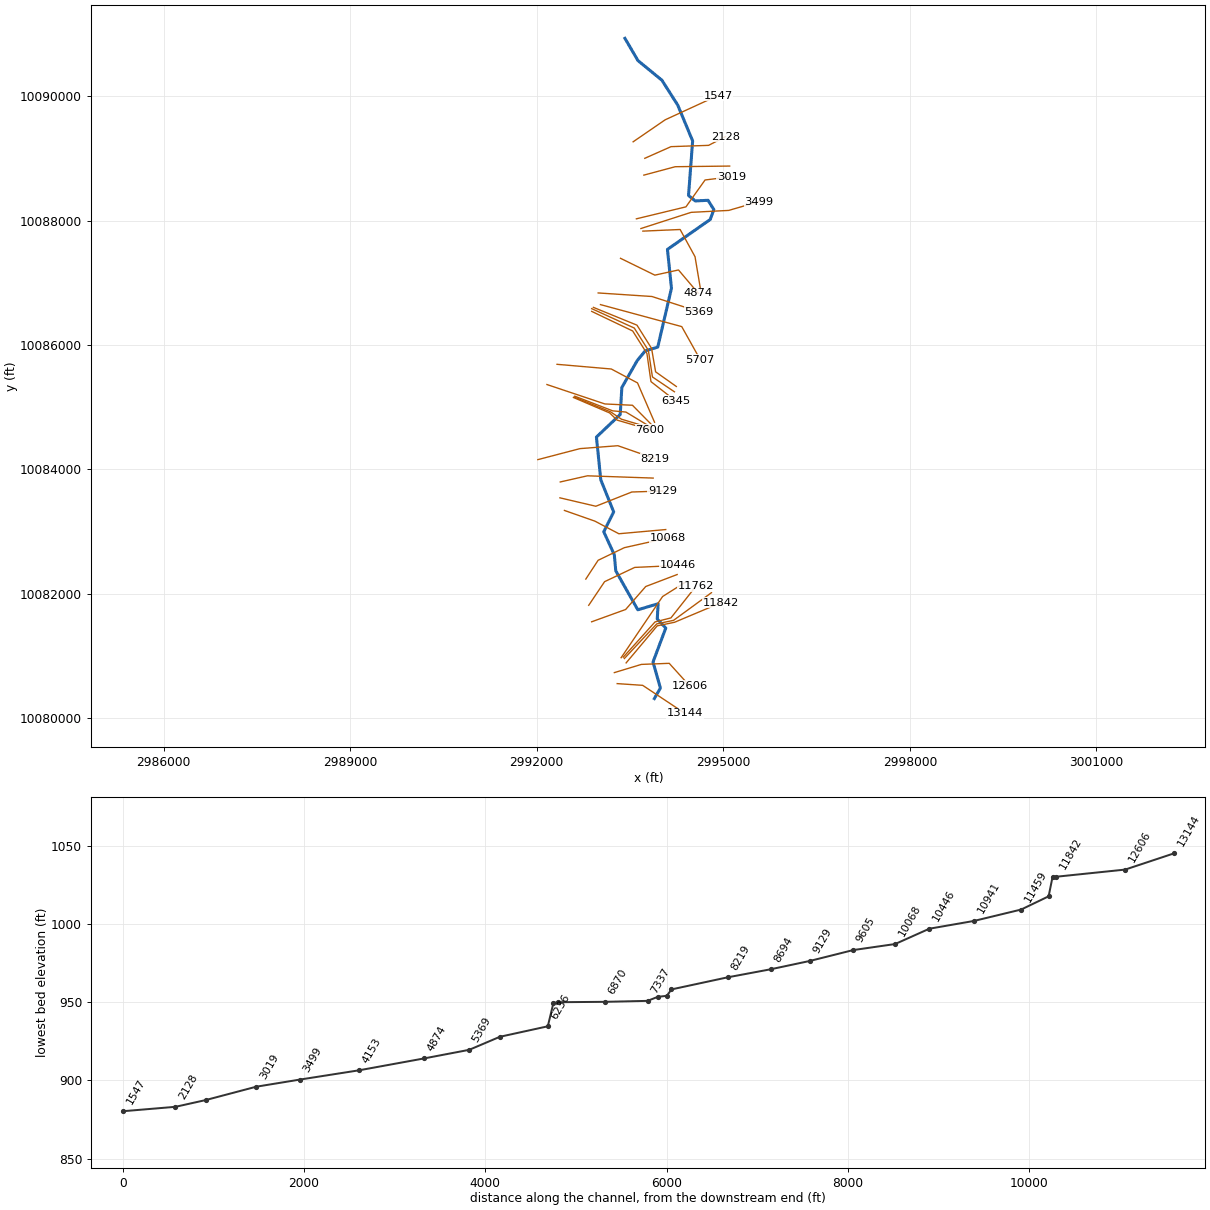
--- HAMILTON CREEK TRIB 2.prj (project) ---

Proj Title=HAMILTON CREEK TRIB 2 Base Level Engineering
Current Plan=p01
Default Exp/Contr=0.3,0.1
English Units
Geom File=g01
Flow File=f01
Plan File=p01
BEGIN DESCRIPTION:
HAMILTON CREEK TRIB 2
END DESCRIPTION:

--- HAMILTON CREEK TRIB 2.p01 (plan) ---

Plan Title=Multiple Run
Short Identifier=Multiple
Geom File=g01
Flow File=f01
Subcritical Flow
K Sum by GR= 0
Std Step Tol= 0.01
Critical Tol= 0.01
Num of Std Step Trials= 20
Max Error Tol= 0.3
Flow Tol Ratio= 0.001
Split Flow NTrial= 30
Split Flow Tol= 0.02
Split Flow Ratio= 0.02
Log Output Level= 0
Friction Slope Method= 1
Unsteady Friction Slope Method= 2
Unsteady Bridges Friction Slope Method= 1
Parabolic Critical Depth
Global Vel Dist=  1 , 1 , 1
Global Log Level= 0
CheckData=True
Encroach Param= -1, 0, 0, 0
BEGIN DESCRIPTION:
Multiple Run
END DESCRIPTION:

--- HAMILTON CREEK TRIB 2.f01 (steady flow) ---

Flow Title=Multiple
Number of Profiles=7
Profile Names=10-year,25-year,50-year,1pct_min,100-year,1pct_plu,500-year
River Rch & RM= HAMILTON CREEK T,Reach-1,13144
     918    1334    1697    1582    2139    2892    3409
River Rch & RM= HAMILTON CREEK T,Reach-1,11842
    1404    2084    2687    2535    3428    4636    5599
River Rch & RM= HAMILTON CREEK T,Reach-1,3499
    1751    2626    3412    3238    4379    5922    7245
Boundary for River Rch & Prof#=HAMILTON CREEK T,Reach-1,1
Up Type=0
Dn Type=3
Dn Slope=0.005
Boundary for River Rch & Prof#=HAMILTON CREEK T,Reach-1,2
Up Type=0
Dn Type=3
Dn Slope=0.005
Boundary for River Rch & Prof#=HAMILTON CREEK T,Reach-1,3
Up Type=0
Dn Type=3
Dn Slope=0.005
Boundary for River Rch & Prof#=HAMILTON CREEK T,Reach-1,4
Up Type=0
Dn Type=3
Dn Slope=0.005
Boundary for River Rch & Prof#=HAMILTON CREEK T,Reach-1,5
Up Type=0
Dn Type=3
Dn Slope=0.005
Boundary for River Rch & Prof#=HAMILTON CREEK T,Reach-1,6
Up Type=0
Dn Type=3
Dn Slope=0.005
Boundary for River Rch & Prof#=HAMILTON CREEK T,Reach-1,7
Up Type=0
Dn Type=3
Dn Slope=0.005

--- HAMILTON CREEK TRIB 2.g01 (geometry) ---

Geom Title=Existing Conditions

River Reach=HAMILTON CREEK T,Reach-1
Reach XY= 30
      2993891.61     10080309.67      2993988.74     10080478.56
      2993870.35     10080898.15      2994075.14     10081443.18
      2993938.17     10081589.40      2993952.66     10081835.57
      2993625.60     10081738.17      2993271.22     10082364.88
      2993247.76     10082623.28      2993078.34     10082992.99
      2993237.68     10083313.89      2993030.20     10083829.42
      2992960.39     10084517.96      2993342.97     10084880.96
      2993368.88     10085315.07      2993616.10     10085748.54
      2993746.04     10085905.86      2993945.83     10085964.59
      2994167.02     10086913.14      2994102.16     10087537.00
      2994790.25     10088019.05      2994847.99     10088178.61
      2994754.82     10088327.52      2994549.48     10088317.10
      2994441.27     10088404.97      2994507.18     10089283.55
      2994267.63     10089859.40      2994013.14     10090259.58
      2993627.54     10090576.19      2993418.47     10090933.73

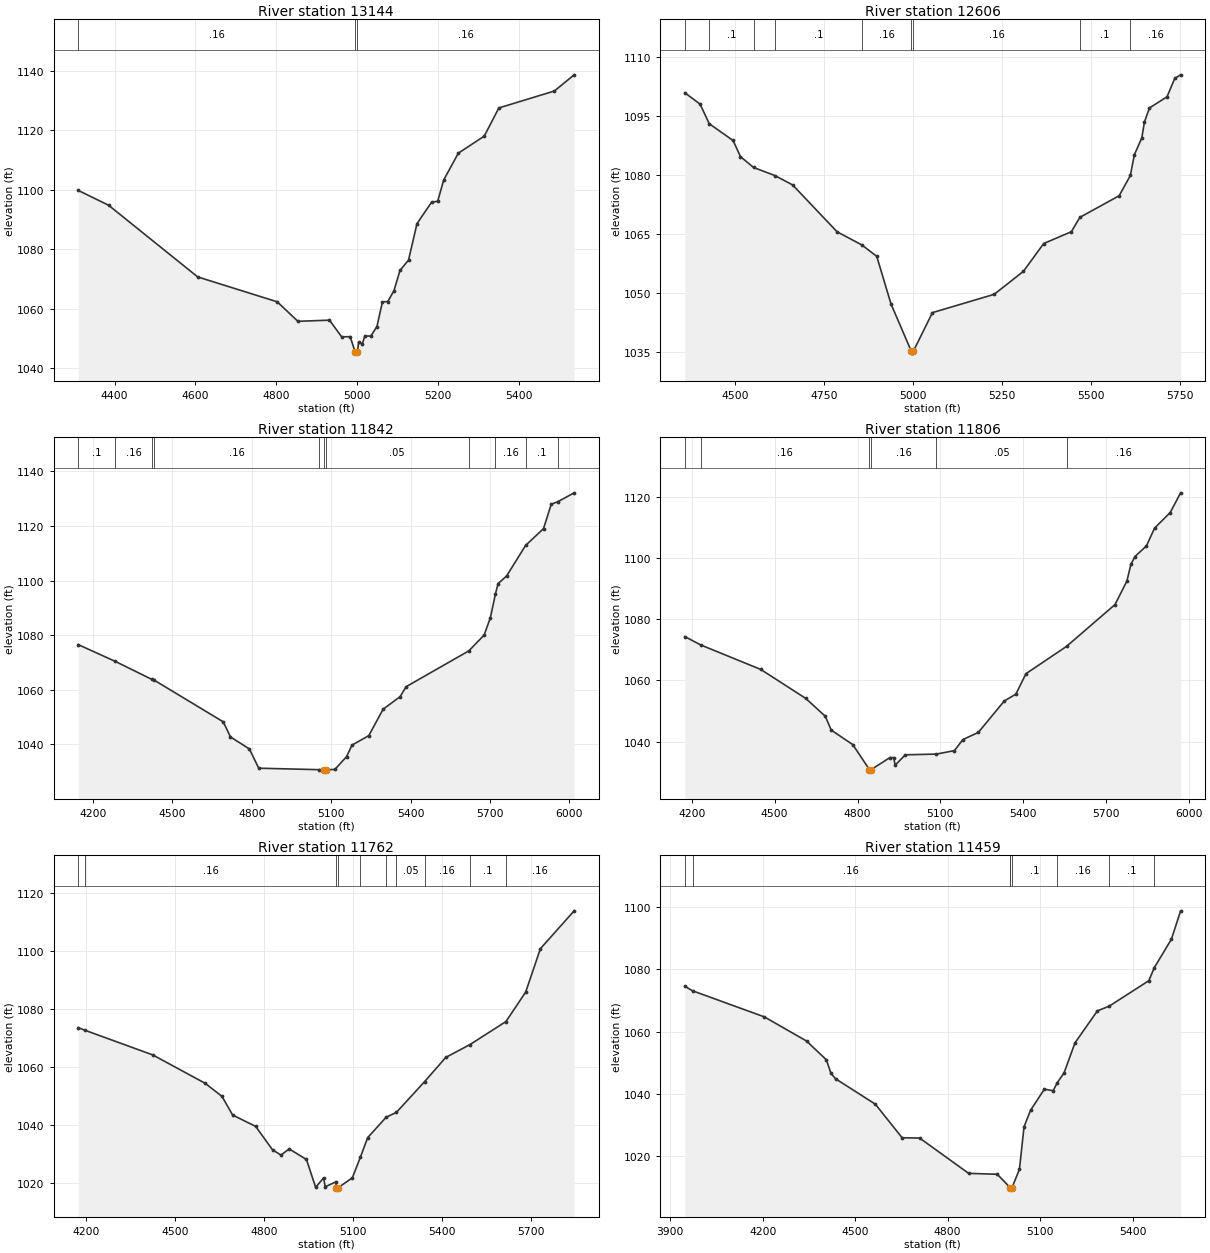
Type RM Length L Ch R = 1,13144,538,538,538
BEGIN DESCRIPTION:
HAMILTON CREEK TRIB 2 30.0
END DESCRIPTION:
XS GIS Cut Line= 3
      2993293.86     10080550.26      2993703.55     10080522.49
      2994383.79     10080071.30
#Sta/Elev= 30
  4310.2 1099.82  4385.0 1094.86  4605.5 1070.77  4802.4 1062.40  4853.5 1055.85
  4931.7 1056.24  4961.8 1050.64  4982.8 1050.69  4994.9 1045.66  4997.6 1045.16
  5000.9 1045.66  5003.9 1048.87  5012.9 1048.26  5018.9 1050.88  5034.0 1050.92
  5049.0 1054.06  5062.7 1062.38  5076.0 1062.50  5091.1 1066.09  5106.1 1072.94
  5127.2 1076.41  5148.2 1088.67  5184.3 1095.88  5199.4 1096.20  5214.4 1103.37
  5250.5 1112.35  5314.7 1118.08  5350.7 1127.54  5488.1 1133.23  5537.1 1138.67
#Mann=3,-1,0
  4310.2    0.16       0  4994.9    0.07       0  5000.9    0.16       0
Bank Sta=4994.9,5000.9
Exp/Cntr=0.3,0.1

Type RM Length L Ch R = 1,12606,764,764,764
BEGIN DESCRIPTION:
Mapping XS 2e42faf1
END DESCRIPTION:
XS GIS Cut Line= 4
      2993248.69     10080727.35      2993682.71     10080859.29
      2994130.63     10080876.65      2994460.52     10080512.03
#Sta/Elev= 30
  4359.1 1100.91  4402.1 1098.02  4427.7 1093.06  4494.7 1088.79  4515.6 1084.70
  4552.2 1081.95  4612.3 1079.89  4662.0 1077.52  4787.4 1065.59  4856.3 1062.30
  4898.6 1059.38  4938.6 1047.31  4995.6 1035.31  4998.4 1034.81  5001.6 1035.31
  5055.1 1045.09  5228.8 1049.74  5311.0 1055.59  5367.8 1062.63  5445.5 1065.63
  5469.7 1069.29  5580.0 1074.77  5611.4 1079.91  5622.6 1085.15  5643.6 1089.45
  5651.0 1093.49  5665.2 1097.06  5714.5 1099.89  5736.2 1104.55  5752.7 1105.46
#Mann=9,-1,0
  4359.1    0.16       0  4427.7     0.1       0  4552.2    0.16       0
  4612.3     0.1       0  4856.3    0.16       0  4995.6    0.07       0
  5001.6    0.16       0  5469.7     0.1       0  5611.4    0.16       0
Bank Sta=4995.6,5001.6
Exp/Cntr=0.3,0.1

Type RM Length L Ch R = 1,11842,36,36,36
BEGIN DESCRIPTION:
HAMILTON CREEK TRIB 2 29.0
END DESCRIPTION:
XS GIS Cut Line= 4
      2993437.92     10080883.59      2993937.92     10081479.95
      2994216.57     10081537.24      2994963.67     10081852.23
#Sta/Elev= 30
  4144.5 1076.55  4283.7 1070.44  4422.8 1063.80  4428.8 1063.68  4692.1 1048.28
  4719.4 1042.75  4791.0 1038.33  4826.1 1031.29  5055.1 1030.75  5073.4 1030.72
  5076.2 1030.22  5079.4 1030.72  5113.7 1030.83  5158.1 1035.54  5178.5 1039.74
  5242.0 1043.23  5296.1 1052.89  5360.6 1057.52  5382.9 1061.15  5619.8 1074.26
  5677.9 1080.07  5701.6 1086.49  5720.3 1095.04  5730.7 1098.93  5762.7 1101.71
  5834.6 1112.90  5902.2 1119.06  5931.4 1127.98  5957.1 1128.96  6018.0 1132.17
#Mann=11,-1,0
  4144.5     0.1       0  4283.7    0.16       0  4422.8     0.1       0
  4428.8    0.16       0  5055.1    0.05       0  5073.4    0.07       0
  5079.4    0.05       0  5619.8     0.1       0  5720.3    0.16       0
  5834.6     0.1       0  5957.1    0.16       0
Bank Sta=5073.4,5079.4
Exp/Cntr=0.3,0.1

Type RM Length L Ch R = 1,11806,44,44,44
BEGIN DESCRIPTION:
HAMILTON CREEK TRIB 2 28.0
END DESCRIPTION:
XS GIS Cut Line= 4
      2993409.29     10080953.93      2993930.11     10081511.20
      2994200.94     10081568.49      2994810.29     10082013.78
#Sta/Elev= 30
  4175.0 1074.34  4232.4 1071.60  4450.0 1063.58  4612.7 1054.11  4683.5 1048.27
  4705.0 1043.74  4782.7 1039.02  4843.2 1030.83  4846.0 1030.33  4849.2 1030.83
  4917.0 1034.74  4931.2 1034.75  4936.1 1032.27  4973.0 1035.67  5085.6 1035.90
  5150.7 1037.04  5181.4 1040.65  5237.2 1042.99  5331.4 1053.29  5373.1 1055.50
  5409.7 1062.20  5556.7 1071.14  5731.7 1084.79  5774.7 1092.44  5789.4 1097.96
  5804.0 1100.51  5845.7 1103.99  5875.1 1109.81  5931.5 1114.89  5969.3 1121.34
#Mann=6,-1,0
  4175.0     0.1       0  4232.4    0.16       0  4843.2    0.07       0
  4849.2    0.16       0  5085.6    0.05       0  5556.7    0.16       0
Bank Sta=4843.2,4849.2
Exp/Cntr=0.3,0.1

Type RM Length L Ch R = 1,11762,303,303,303
BEGIN DESCRIPTION:
HAMILTON CREEK TRIB 2 27.0
END DESCRIPTION:
XS GIS Cut Line= 4
      2993392.19     10080976.16      2993902.18     10081542.58
      2994158.26     10081607.68      2994557.56     10082113.32
#Sta/Elev= 30
  4174.1 1073.52  4196.1 1072.64  4424.9 1064.10  4601.4 1054.30  4658.1 1049.78
  4694.0 1043.33  4771.7 1039.40  4828.5 1031.29  4856.9 1029.50  4884.6 1031.62
  4942.8 1027.96  4973.7 1018.35  5000.7 1021.62  5005.8 1018.52  5041.6 1020.23
  5043.8 1018.22  5046.5 1017.72  5049.8 1018.22  5097.5 1021.65  5124.1 1028.66
  5149.1 1035.52  5211.3 1042.56  5246.0 1044.26  5340.9 1054.88  5412.1 1063.23
  5493.9 1067.69  5615.0 1075.64  5681.4 1085.81  5731.1 1100.83  5844.8 1113.90
#Mann=10,-1,0
  4174.1     0.1       0  4196.1    0.16       0  5043.8    0.07       0
  5049.8    0.16       0  5124.1    0.05       0  5211.3     0.1       0
  5246.0    0.05       0  5340.9    0.16       0  5493.9     0.1       0
  5615.0    0.16       0
Bank Sta=5043.8,5049.8
Exp/Cntr=0.3,0.1

Type RM Length L Ch R = 1,11459,518,518,518
BEGIN DESCRIPTION:
HAMILTON CREEK TRIB 2 26.0
END DESCRIPTION:
XS GIS Cut Line= 3
      2993357.18     10080966.91      2994023.86     10081951.31
      2994377.99     10082175.24
#Sta/Elev= 30
  3947.5 1074.58  3972.6 1073.12  4205.9 1064.70  4342.2 1056.95  4406.6 1050.90
  4421.6 1046.53  4436.5 1044.79  4565.3 1036.63  4652.2 1025.81  4709.1 1025.71
  4867.9 1014.35  4960.8 1014.05  5000.9 1009.94  5002.7 1009.77  5005.4 1009.27
  5008.7 1009.77  5032.7 1015.66  5047.6 1029.33  5068.6 1034.63  5113.5 1041.44
  5142.1 1040.96  5155.6 1043.56  5177.4 1046.69  5212.8 1056.35  5285.5 1066.66
  5323.6 1068.16  5452.5 1076.38  5469.9 1080.54  5525.4 1089.70  5555.4 1098.86
#Mann=8,-1,0
  3947.5     0.1       0  3972.6    0.16       0  5000.9     0.1       0
  5002.7    0.07       0  5008.7     0.1       0  5155.6    0.16       0
  5323.6     0.1       0  5469.9    0.16       0
Bank Sta=5002.7,5008.7
Exp/Cntr=0.3,0.1

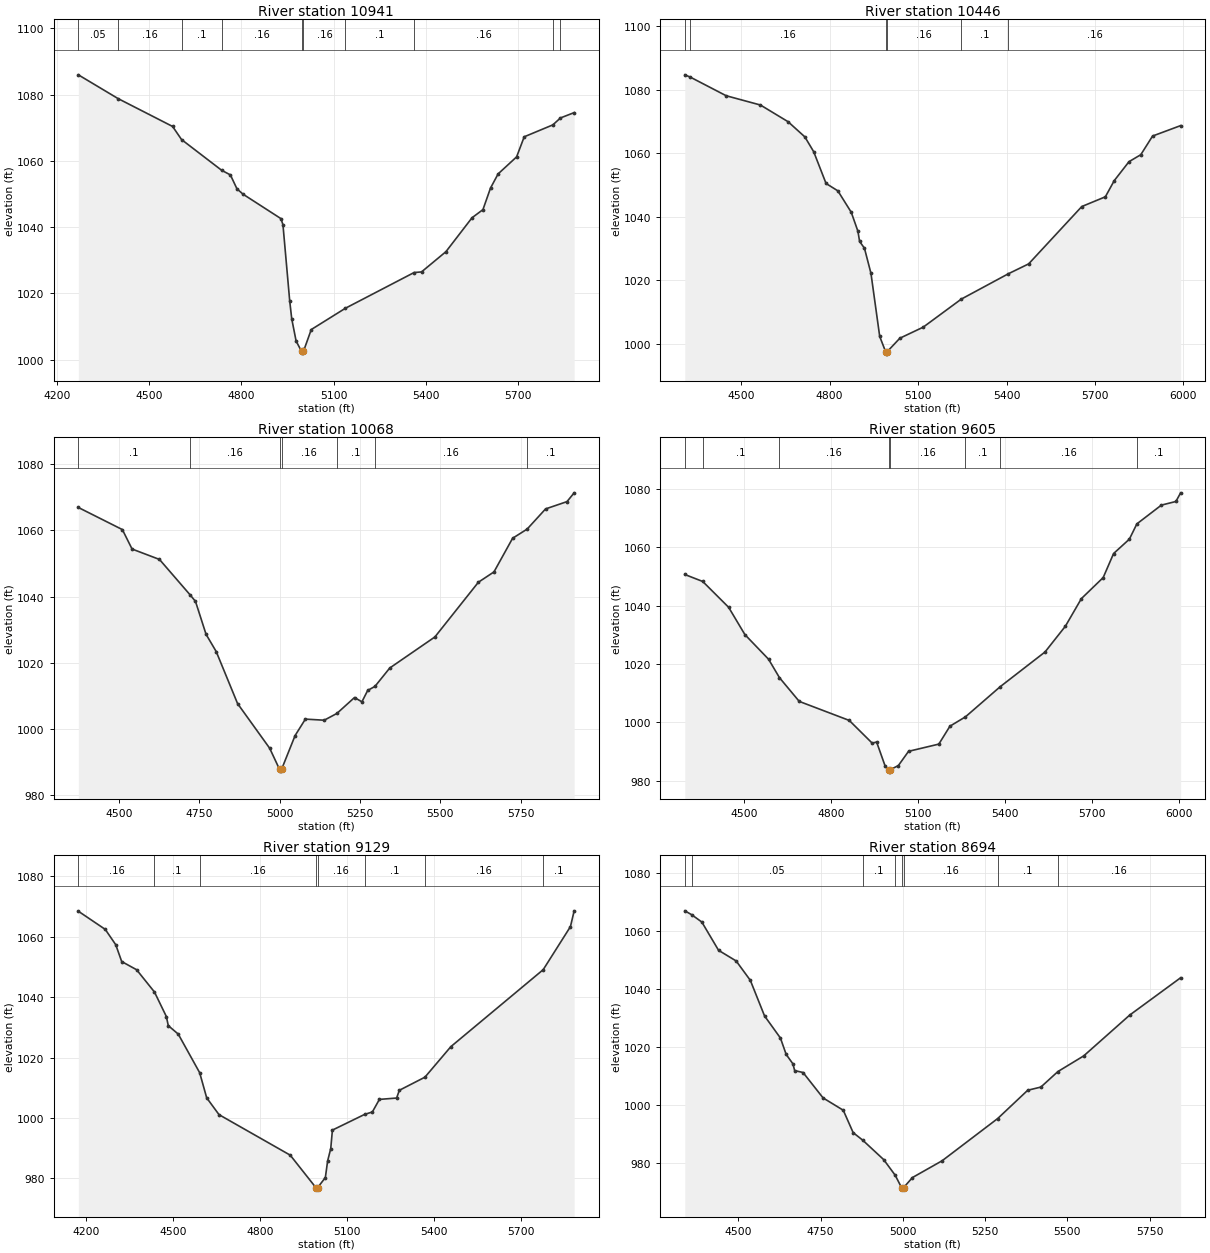
Type RM Length L Ch R = 1,10941,495,495,495
BEGIN DESCRIPTION:
HAMILTON CREEK TRIB 2 25.0
END DESCRIPTION:
XS GIS Cut Line= 4
      2992883.20     10081545.05      2993430.11     10081742.97
      2993753.03     10082112.77      2994258.26     10082305.48
#Sta/Elev= 30
  4269.6 1085.95  4398.8 1078.79  4576.3 1070.38  4605.5 1066.42  4735.9 1057.16
  4764.4 1055.76  4785.7 1051.57  4805.5 1049.95  4928.8 1042.58  4935.4 1040.74
  4957.3 1017.83  4963.9 1012.39  4978.2 1005.65  4996.0 1002.51  4998.8 1002.01
  5002.0 1002.51  5027.5 1009.12  5138.7 1015.55  5362.1 1026.32  5386.2 1026.50
  5465.7 1032.61  5550.7 1042.85  5586.1 1045.29  5610.8 1051.81  5635.5 1056.07
  5695.7 1061.21  5720.4 1067.26  5813.5 1070.85  5838.4 1072.95  5882.9 1074.55
#Mann=10,-1,0
  4269.6    0.05       0  4398.8    0.16       0  4605.5     0.1       0
  4735.9    0.16       0  4996.0    0.07       0  5002.0    0.16       0
  5138.7     0.1       0  5362.1    0.16       0  5813.5     0.1       0
  5838.4    0.16       0
Bank Sta=4996,5002
Exp/Cntr=0.3,0.1

Type RM Length L Ch R = 1,10446,378,378,378
BEGIN DESCRIPTION:
HAMILTON CREEK TRIB 2 24.0
END DESCRIPTION:
XS GIS Cut Line= 4
      2992836.35     10081810.67      2993091.57     10082190.89
      2993575.94     10082420.06      2994263.45     10082451.31
#Sta/Elev= 30
  4308.6 1084.76  4326.8 1084.06  4448.9 1078.17  4565.2 1075.24  4658.9 1069.98
  4715.9 1065.19  4745.9 1060.51  4787.8 1050.50  4827.8 1048.18  4873.3 1041.42
  4895.9 1035.43  4901.6 1032.22  4918.0 1030.10  4940.1 1022.18  4969.8 1002.27
  4989.6  997.51  4992.3  997.01  4995.6  997.51  5038.1 1001.71  5117.4 1005.20
  5246.7 1014.05  5406.1 1022.03  5475.1 1025.15  5655.3 1043.23  5735.3 1046.30
  5765.4 1051.40  5815.4 1057.37  5855.5 1059.58  5895.5 1065.46  5990.6 1068.75
#Mann=6,-1,0
  4308.6    0.05       0  4326.8    0.16       0  4989.6    0.07       0
  4995.6    0.16       0  5246.7     0.1       0  5406.1    0.16       0
Bank Sta=4989.6,4995.6
Exp/Cntr=0.3,0.1

Type RM Length L Ch R = 1,10068,463,463,463
BEGIN DESCRIPTION:
HAMILTON CREEK TRIB 2 23.0
END DESCRIPTION:
XS GIS Cut Line= 4
      2992789.46     10082232.53      2992987.40     10082534.64
      2993409.28     10082737.77      2994105.34     10082893.60
#Sta/Elev= 30
  4373.4 1066.95  4510.4 1060.26  4540.6 1054.38  4625.9 1051.23  4720.7 1040.57
  4737.9 1038.55  4770.8 1028.59  4802.4 1023.37  4868.9 1007.63  4968.8  994.12
  4999.6  987.71  5002.4  987.21  5005.6  987.71  5047.9  997.98  5079.8 1002.94
  5138.4 1002.61  5177.8 1004.65  5232.7 1009.47  5255.7 1008.17  5273.7 1011.61
  5296.4 1012.85  5342.4 1018.40  5482.8 1027.79  5618.1 1044.34  5666.6 1047.46
  5724.6 1057.64  5769.7 1060.40  5827.1 1066.51  5893.8 1068.72  5916.1 1071.38
#Mann=7,-1,0
  4373.4     0.1       0  4720.7    0.16       0  4999.6    0.07       0
  5005.6    0.16       0  5177.8     0.1       0  5296.4    0.16       0
  5769.7     0.1       0
Bank Sta=4999.6,5005.6
Exp/Cntr=0.3,0.1

Type RM Length L Ch R = 1,9605,476,476,476
BEGIN DESCRIPTION:
HAMILTON CREEK TRIB 2 22.0
END DESCRIPTION:
XS GIS Cut Line= 4
      2992445.70     10083336.74      2992935.32     10083164.85
      2993320.73     10082961.72      2994074.73     10083029.32
#Sta/Elev= 30
  4294.1 1050.66  4356.0 1048.27  4445.4 1039.43  4501.5 1030.09  4583.2 1021.66
  4621.0 1015.32  4689.2 1007.21  4861.8 1000.70  4940.9  992.93  4956.3  993.30
  4986.1  984.96  4997.4  983.84  5000.2  983.34  5003.4  983.84  5031.3  985.24
  5066.5  990.12  5171.0  992.59  5209.4  998.73  5262.9 1001.92  5382.9 1012.25
  5537.6 1024.13  5607.8 1032.94  5663.1 1042.40  5738.4 1049.61  5774.3 1057.84
  5828.7 1062.75  5854.7 1067.99  5939.2 1074.41  5989.4 1075.66  6005.7 1078.62
#Mann=8,-1,0
  4294.1    0.16       0  4356.0     0.1       0  4621.0    0.16       0
  4997.4    0.07       0  5003.4    0.16       0  5262.9     0.1       0
  5382.9    0.16       0  5854.7     0.1       0
Bank Sta=4997.4,5003.4
Exp/Cntr=0.3,0.1

Type RM Length L Ch R = 1,9129,435,435,435
BEGIN DESCRIPTION:
HAMILTON CREEK TRIB 2 21.0
END DESCRIPTION:
XS GIS Cut Line= 4
      2992372.81     10083539.85      2992950.94     10083404.43
      2993529.07     10083633.60      2994023.65     10083649.22
#Sta/Elev= 30
  4173.0 1068.47  4265.9 1062.45  4302.1 1057.37  4322.6 1051.80  4374.0 1049.09
  4435.7 1041.70  4476.7 1033.58  4483.3 1030.57  4517.7 1027.77  4591.6 1014.98
  4615.8 1006.66  4658.3 1001.09  4904.0  987.67  4992.5  976.92  4995.2  976.42
  4998.5  976.92  5025.2  980.25  5033.0  985.74  5043.8  989.87  5049.5  995.97
  5161.0 1001.19  5187.3 1001.97  5211.6 1006.14  5271.0 1006.59  5280.5 1009.16
  5368.7 1013.50  5458.1 1023.61  5776.7 1049.11  5870.7 1063.37  5883.5 1068.60
#Mann=8,-1,0
  4173.0    0.16       0  4435.7     0.1       0  4591.6    0.16       0
  4992.5    0.07       0  4998.5    0.16       0  5161.0     0.1       0
  5368.7    0.16       0  5776.7     0.1       0
Bank Sta=4992.5,4998.5
Exp/Cntr=0.3,0.1

Type RM Length L Ch R = 1,8694,475,475,475
BEGIN DESCRIPTION:
HAMILTON CREEK TRIB 2 20.0
END DESCRIPTION:
XS GIS Cut Line= 3
      2992378.05     10083795.06      2992815.53     10083894.02
      2993872.77     10083857.56
#Sta/Elev= 30
  4337.6 1066.99  4358.1 1065.68  4389.3 1063.13  4440.2 1053.38  4493.6 1049.71
  4536.7 1043.03  4579.9 1030.76  4628.2 1023.13  4645.6 1017.49  4666.1 1014.24
  4671.4 1011.92  4696.9 1011.26  4757.7 1002.50  4819.1  998.25  4849.1  990.53
  4877.9  987.96  4941.8  981.24  4976.8  975.85  4996.2  971.56  4998.9  971.06
  5002.2  971.56  5029.2  975.05  5119.3  980.83  5288.3  995.40  5379.4 1005.14
  5419.4 1006.24  5471.2 1011.59  5549.5 1016.98  5689.6 1031.08  5844.0 1043.92
#Mann=8,-1,0
  4337.6    0.16       0  4358.1    0.05       0  4877.9     0.1       0
  4976.8    0.16       0  4996.2    0.07       0  5002.2    0.16       0
  5288.3     0.1       0  5471.2    0.16       0
Bank Sta=4996.2,5002.2
Exp/Cntr=0.3,0.1

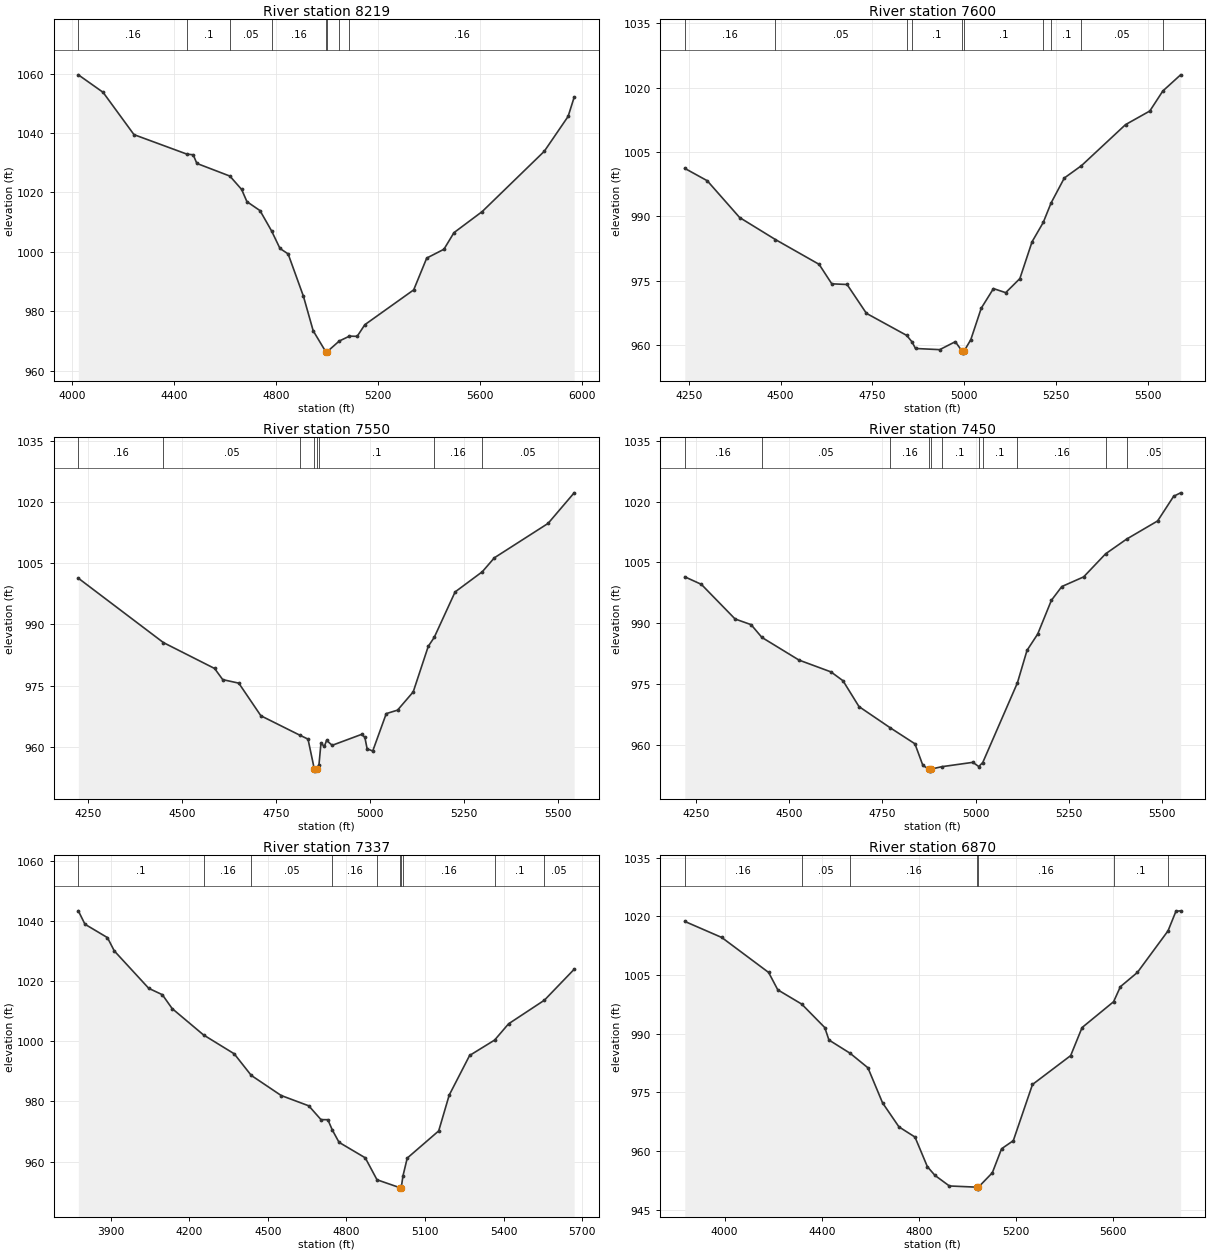
Type RM Length L Ch R = 1,8219,619,619,619
BEGIN DESCRIPTION:
HAMILTON CREEK TRIB 2 19.0
END DESCRIPTION:
XS GIS Cut Line= 4
      2992018.69     10084154.44      2992695.73     10084331.52
      2993305.11     10084378.39      2993903.74     10084170.17
#Sta/Elev= 30
  4023.9 1059.58  4120.9 1053.70  4242.2 1039.45  4449.7 1032.89  4474.4 1032.67
  4488.8 1029.76  4618.3 1025.50  4664.5 1020.99  4685.2 1016.89  4736.5 1013.88
  4781.7 1007.07  4814.8 1001.14  4846.8  999.30  4907.0  985.00  4945.1  973.43
  4994.2  966.41  4997.0  965.91  5000.2  966.41  5047.3  969.98  5087.5  971.63
  5117.6  971.56  5147.7  975.48  5339.3  987.20  5390.4  997.90  5457.9 1000.87
  5497.3 1006.46  5608.1 1013.56  5851.6 1033.85  5944.9 1045.57  5968.7 1052.03
#Mann=8,-1,0
  4023.9    0.16       0  4449.7     0.1       0  4618.3    0.05       0
  4781.7    0.16       0  4994.2    0.07       0  5000.2    0.16       0
  5047.3    0.05       0  5087.5    0.16       0
Bank Sta=4994.2,5000.2
Exp/Cntr=0.3,0.1

Type RM Length L Ch R = 1,7600,50,50,50
BEGIN DESCRIPTION:
Mapping XS 76a897af
END DESCRIPTION:
XS GIS Cut Line= 4
      2992590.97     10085154.35      2993172.61     10084905.85
      2993291.97     10084790.84      2993822.58     10084634.58
#Sta/Elev= 30
  4238.8 1001.18  4299.9  998.31  4388.3  989.74  4485.8  984.62  4604.9  978.85
  4639.4  974.32  4681.1  974.16  4733.8  967.45  4843.5  962.32  4857.7  960.85
  4867.6  959.27  4933.6  959.00  4976.1  960.85  4994.2  958.69  4996.9  958.19
  5000.2  958.69  5018.3  961.32  5046.8  968.65  5080.1  973.21  5113.4  972.26
  5152.0  975.53  5185.3  984.11  5215.7  988.59  5237.2  993.15  5273.2  998.94
  5319.9 1001.81  5440.0 1011.36  5506.2 1014.53  5541.7 1019.19  5590.2 1022.95
#Mann=10,-1,0
  4238.8    0.16       0  4485.8    0.05       0  4843.5    0.16       0
  4857.7     0.1       0  4994.2    0.07       0  5000.2     0.1       0
  5215.7    0.16       0  5237.2     0.1       0  5319.9    0.05       0
  5541.7     0.1       0
Bank Sta=4994.2,5000.2
Exp/Cntr=0.3,0.1

Type RM Length L Ch R = 1,7550,100,100,100
BEGIN DESCRIPTION:
Mapping XS 800ea5dd
END DESCRIPTION:
XS GIS Cut Line= 4
      2992602.98     10085161.92      2993189.97     10084922.13
      2993362.50     10084804.94      2993818.47     10084668.48
#Sta/Elev= 30
  4224.5 1001.32  4450.9  985.55  4586.9  979.22  4608.5  976.49  4651.2  975.63
  4710.0  967.64  4812.8  962.92  4835.3  961.93  4852.1  954.59  4854.8  954.09
  4858.1  954.59  4864.5  955.69  4869.8  960.96  4878.7  960.12  4884.7  961.61
  4899.6  960.41  4977.6  963.08  4986.4  962.40  4992.5  959.57  5007.4  959.01
  5043.4  968.17  5073.4  969.02  5115.1  973.49  5155.1  984.64  5170.9  986.82
  5226.5  997.96  5298.7 1002.89  5331.0 1006.32  5473.8 1014.74  5543.1 1022.22
#Mann=8,-1,0
  4224.5    0.16       0  4450.9    0.05       0  4812.8    0.16       0
  4852.1    0.07       0  4858.1    0.16       0  4864.5     0.1       0
  5170.9    0.16       0  5298.7    0.05       0
Bank Sta=4852.1,4858.1
Exp/Cntr=0.3,0.1

Type RM Length L Ch R = 1,7450,113,113,113
BEGIN DESCRIPTION:
Mapping XS d3ce33a1
END DESCRIPTION:
XS GIS Cut Line= 4
      2992612.68     10085174.97      2993221.44     10084939.49
      2993434.11     10084919.96      2993831.25     10084680.16
#Sta/Elev= 30
  4219.8 1001.45  4264.2  999.59  4354.7  991.04  4397.6  989.64  4426.6  986.49
  4526.2  980.89  4612.0  977.97  4644.2  975.79  4687.1  969.41  4771.6  964.13
  4837.2  960.22  4858.6  954.86  4874.7  953.97  4877.4  953.47  4880.7  953.97
  4909.0  954.56  4992.6  955.64  5008.5  954.60  5019.2  955.60  5112.1  975.26
  5137.9  983.29  5166.5  987.31  5203.3  995.65  5231.3  999.05  5289.8 1001.43
  5348.7 1007.13  5404.9 1010.75  5488.3 1015.25  5531.3 1021.34  5550.0 1022.19
#Mann=11,-1,0
  4219.8    0.16       0  4426.6    0.05       0  4771.6    0.16       0
  4874.7    0.07       0  4880.7    0.16       0  4909.0     0.1       0
  5008.5    0.16       0  5019.2     0.1       0  5112.1    0.16       0
  5348.7     0.1       0  5404.9    0.05       0
Bank Sta=4874.7,4880.7
Exp/Cntr=0.3,0.1

Type RM Length L Ch R = 1,7337,467,467,467
BEGIN DESCRIPTION:
HAMILTON CREEK TRIB 2 18.0
END DESCRIPTION:
XS GIS Cut Line= 4
      2992164.45     10085362.78      2993096.78     10085050.27
      2993539.48     10085029.43      2993866.31     10084697.41
#Sta/Elev= 30
  3776.6 1043.32  3801.9 1038.87  3887.7 1034.42  3913.9 1030.00  4045.4 1017.57
  4097.2 1015.46  4134.8 1010.84  4254.5 1002.09  4371.5  995.83  4436.6  988.65
  4550.8  981.97  4656.2  978.54  4702.7  973.96  4729.0  973.93  4745.9  970.53
  4771.6  966.42  4871.7  961.27  4916.5  953.98  5003.1  951.37  5005.8  950.87
  5009.1  951.37  5015.5  955.21  5031.9  961.18  5152.0  970.21  5192.1  982.11
  5270.0  995.27  5365.5 1000.39  5418.6 1005.78  5555.5 1013.64  5669.0 1023.90
#Mann=10,-1,0
  3776.6     0.1       0  4254.5    0.16       0  4436.6    0.05       0
  4745.9    0.16       0  4916.5     0.1       0  5003.1    0.07       0
  5009.1     0.1       0  5015.5    0.16       0  5365.5     0.1       0
  5555.5    0.05       0
Bank Sta=5003.1,5009.1
Exp/Cntr=0.3,0.1

Type RM Length L Ch R = 1,6870,525,525,525
BEGIN DESCRIPTION:
HAMILTON CREEK TRIB 2 17.0
END DESCRIPTION:
XS GIS Cut Line= 4
      2992326.83     10085688.28      2993199.21     10085612.77
      2993621.08     10085388.81      2993894.51     10084756.03
#Sta/Elev= 30
  3835.9 1018.69  3988.1 1014.59  4181.2 1005.65  4219.0 1001.20  4317.5  997.56
  4412.6  991.55  4429.7  988.38  4516.7  985.00  4590.3  981.28  4650.6  972.31
  4718.2  966.17  4784.2  963.57  4835.2  956.00  4866.5  953.77  4925.8  951.07
  5039.4  950.76  5042.1  950.26  5045.4  950.76  5102.7  954.43  5140.9  960.58
  5189.2  962.65  5268.2  977.01  5425.5  984.39  5472.5  991.56  5602.4  998.17
  5630.4 1002.01  5700.3 1005.64  5826.7 1016.29  5859.2 1021.29  5878.5 1021.40
#Mann=7,-1,0
  3835.9    0.16       0  4317.5    0.05       0  4516.7    0.16       0
  5039.4    0.07       0  5045.4    0.16       0  5602.4     0.1       0
  5826.7    0.05       0
Bank Sta=5039.4,5045.4
Exp/Cntr=0.3,0.1

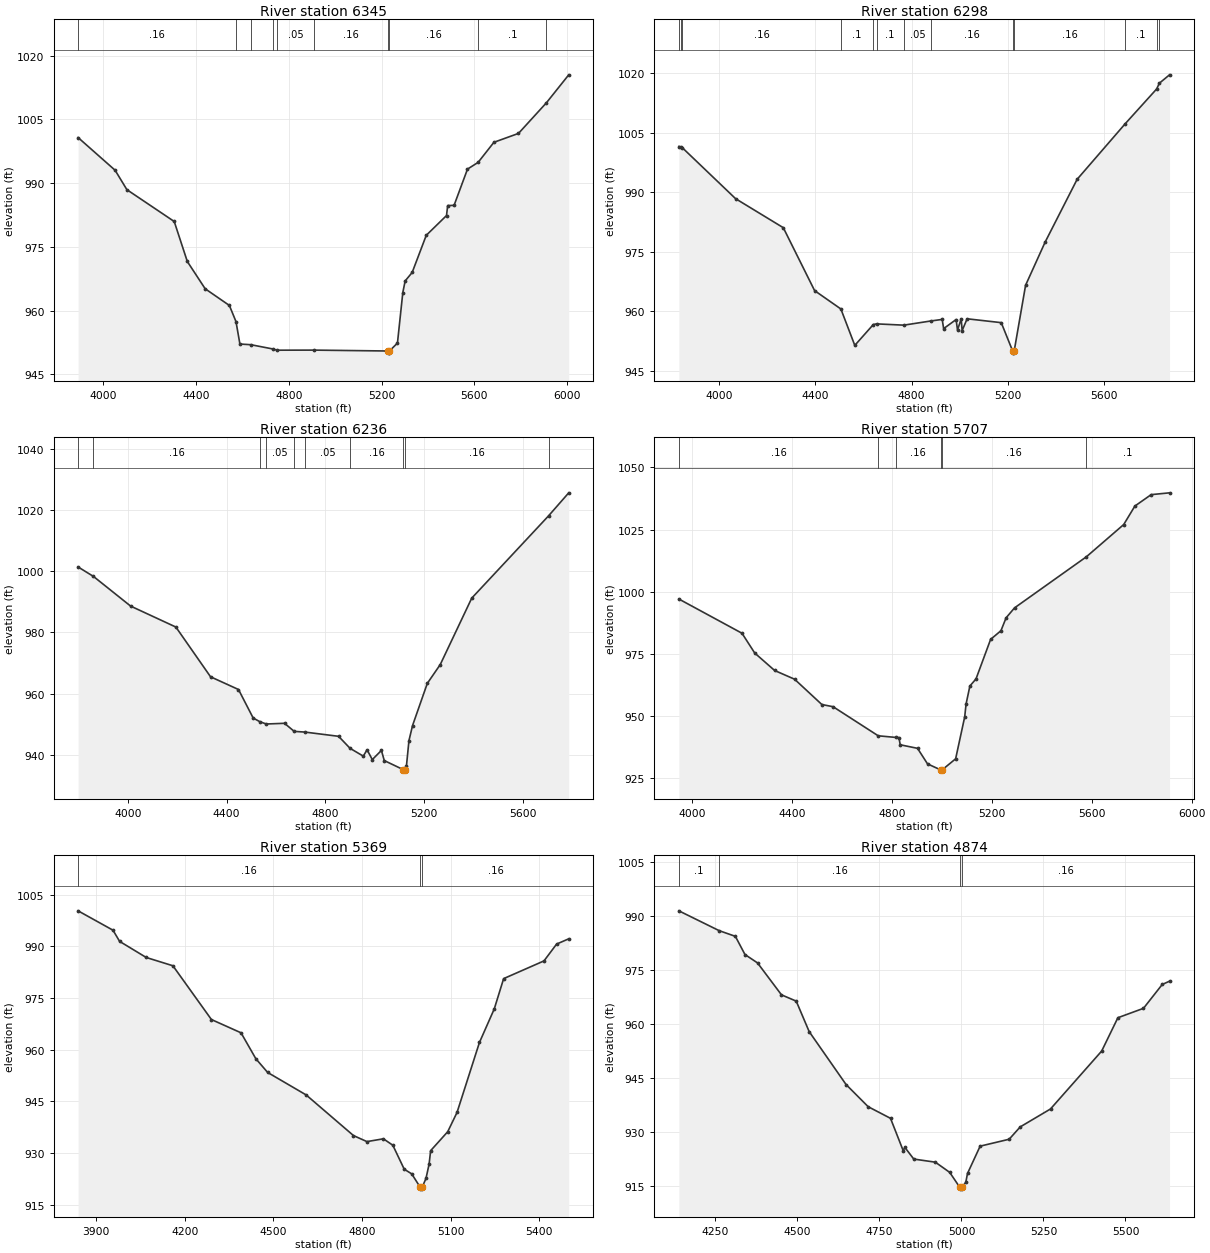
Type RM Length L Ch R = 1,6345,47,47,47
BEGIN DESCRIPTION:
HAMILTON CREEK TRIB 2 16.0
END DESCRIPTION:
XS GIS Cut Line= 5
      2992884.10     10086539.85      2993542.96     10086224.74
      2993772.12     10085862.77      2993837.23     10085409.64
      2994230.47     10085102.34
#Sta/Elev= 30
  3891.6 1000.75  4051.3  993.05  4102.1  988.48  4306.2  980.99  4362.6  971.58
  4439.6  965.16  4544.0  961.23  4572.5  957.43  4589.4  952.15  4636.8  951.99
  4732.1  950.98  4750.1  950.70  4909.3  950.72  5228.2  950.51  5231.0  950.01
  5234.2  950.51  5268.7  952.38  5291.8  964.27  5301.9  967.00  5332.2  969.00
  5392.9  977.74  5480.2  982.39  5485.3  984.74  5512.8  984.79  5570.7  993.32
  5616.6  994.91  5684.6  999.63  5790.5 1001.72  5911.0 1008.93  6007.2 1015.51
#Mann=10,-1,0
  3891.6    0.16       0  4572.5     0.1       0  4636.8    0.05       0
  4732.1     0.1       0  4750.1    0.05       0  4909.3    0.16       0
  5228.2    0.07       0  5234.2    0.16       0  5616.6     0.1       0
  5911.0    0.05       0
Bank Sta=5228.2,5234.2
Exp/Cntr=0.3,0.1

Type RM Length L Ch R = 1,6298,62,62,62
BEGIN DESCRIPTION:
HAMILTON CREEK TRIB 2 15.0
END DESCRIPTION:
XS GIS Cut Line= 5
      2992884.12     10086584.11      2993569.00     10086271.62
      2993795.56     10085912.24      2993860.66     10085485.16
      2994214.14     10085246.05
#Sta/Elev= 30
  3834.4 1001.48  3843.2 1001.37  3849.1 1001.16  4070.0  988.35  4267.9  981.05
  4397.8  965.22  4506.8  960.60  4564.6  951.44  4641.4  956.68  4654.7  956.85
  4768.0  956.53  4881.2  957.59  4927.4  957.97  4933.3  955.66  4985.0  957.94
  4990.9  955.31  5006.2  958.11  5010.1  955.16  5030.8  958.13  5172.4  957.16
  5220.0  949.99  5222.7  949.49  5226.0  949.99  5273.5  966.58  5354.5  977.42
  5487.4  993.23  5687.6 1007.26  5817.5 1015.97  5828.6 1017.41  5870.8 1019.52
#Mann=13,-1,0
  3834.4    0.16       0  3843.2     0.1       0  3849.1    0.16       0
  4506.8     0.1       0  4641.4    0.05       0  4654.7     0.1       0
  4768.0    0.05       0  4881.2    0.16       0  5220.0    0.07       0
  5226.0    0.16       0  5687.6     0.1       0  5817.5    0.05       0
  5828.6     0.1       0
Bank Sta=5220,5226
Exp/Cntr=0.3,0.1

Type RM Length L Ch R = 1,6236,529,529,529
BEGIN DESCRIPTION:
HAMILTON CREEK TRIB 2 14.0
END DESCRIPTION:
XS GIS Cut Line= 5
      2992911.40     10086604.70      2993612.39     10086318.23
      2993846.76     10085944.97      2993911.87     10085567.36
      2994244.74     10085331.76
#Sta/Elev= 30
  3798.2 1001.46  3860.7  998.35  4011.1  988.65  4194.7  981.78  4335.2  965.50
  4448.5  961.33  4508.0  952.00  4535.2  950.79  4561.3  950.04  4635.1  950.27
  4674.4  947.62  4717.3  947.40  4854.2  946.01  4900.7  942.08  4954.4  939.52
  4969.7  941.60  4990.9  938.39  5027.9  941.39  5039.4  938.07  5116.2  935.11
  5119.0  934.61  5122.2  935.11  5129.4  936.36  5139.5  944.60  5154.1  949.54
  5213.9  963.34  5266.4  969.50  5394.0  991.25  5705.5 1018.20  5787.2 1025.73
#Mann=10,-1,0
  3798.2     0.1       0  3860.7    0.16       0  4535.2     0.1       0
  4561.3    0.05       0  4674.4     0.1       0  4717.3    0.05       0
  4900.7    0.16       0  5116.2    0.07       0  5122.2    0.16       0
  5705.5     0.1       0
Bank Sta=5116.2,5122.2
Exp/Cntr=0.3,0.1

Type RM Length L Ch R = 1,5707,338,338,338
BEGIN DESCRIPTION:
HAMILTON CREEK TRIB 2 13.0
END DESCRIPTION:
XS GIS Cut Line= 3
      2993024.69     10086649.23      2994332.02     10086295.06
      2994628.88     10085763.83
#Sta/Elev= 30
  3948.4  997.08  4201.0  983.32  4251.9  975.37  4331.6  968.35  4411.3  964.85
  4520.5  954.67  4565.5  953.79  4746.0  942.10  4817.2  941.44  4828.8  941.37
  4834.0  938.49  4903.3  937.06  4943.2  930.82  4995.7  928.40  4998.5  927.90
  5001.7  928.40  5055.7  932.85  5092.0  949.71  5097.4  954.82  5112.7  962.11
  5137.2  964.96  5195.6  980.85  5237.0  984.34  5257.7  989.54  5291.4  993.52
  5578.8 1014.05  5728.2 1027.02  5772.8 1034.44  5837.9 1039.03  5911.4 1039.76
#Mann=6,-1,0
  3948.4    0.16       0  4746.0     0.1       0  4817.2    0.16       0
  4995.7    0.07       0  5001.7    0.16       0  5578.8     0.1       0
Bank Sta=4995.7,5001.7
Exp/Cntr=0.3,0.1

Type RM Length L Ch R = 1,5369,495,495,495
BEGIN DESCRIPTION:
HAMILTON CREEK TRIB 2 12.0
END DESCRIPTION:
XS GIS Cut Line= 3
      2992988.22     10086836.73      2993852.85     10086779.43
      2994608.04     10086534.65
#Sta/Elev= 30
  3839.2 1000.27  3957.4  994.65  3979.8  991.41  4069.9  986.74  4160.1  984.34
  4290.4  968.75  4390.6  964.90  4440.8  957.38  4480.8  953.40  4611.1  946.88
  4771.2  935.10  4816.7  933.35  4872.4  934.16  4904.3  932.30  4942.9  925.35
  4968.3  923.99  4997.3  920.07  5000.0  919.57  5003.3  920.07  5016.5  922.66
  5027.0  926.77  5032.3  930.72  5090.1  936.22  5121.6  941.81  5197.5  962.11
  5247.7  971.85  5279.3  980.61  5415.9  985.75  5458.6  990.63  5499.6  992.15
#Mann=3,-1,0
  3839.2    0.16       0  4997.3    0.07       0  5003.3    0.16       0
Bank Sta=4997.3,5003.3
Exp/Cntr=0.3,0.1

Type RM Length L Ch R = 1,4874,721,721,721
BEGIN DESCRIPTION:
HAMILTON CREEK TRIB 2 11.0
END DESCRIPTION:
XS GIS Cut Line= 4
      2993347.61     10087394.03      2993899.73     10087123.18
      2994279.94     10087206.52      2994597.64     10086831.52
#Sta/Elev= 30
  4138.5  991.42  4261.4  985.91  4310.8  984.33  4340.0  979.28  4378.3  976.95
  4451.3  968.08  4496.3  966.33  4535.7  957.87  4648.2  943.16  4715.6  937.00
  4783.7  933.77  4822.4  924.78  4827.5  925.69  4854.6  922.45  4920.3  921.59
  4964.1  918.76  4994.9  914.60  4997.6  914.10  5000.9  914.60  5013.1  915.96
  5018.4  918.45  5056.9  926.04  5145.4  927.96  5179.1  931.39  5271.4  936.37
  5427.4  952.46  5476.8  961.72  5554.8  964.33  5612.0  970.96  5634.2  971.87
#Mann=4,-1,0
  4138.5     0.1       0  4261.4    0.16       0  4994.9    0.07       0
  5000.9    0.16       0
Bank Sta=4994.9,5000.9
Exp/Cntr=0.3,0.1

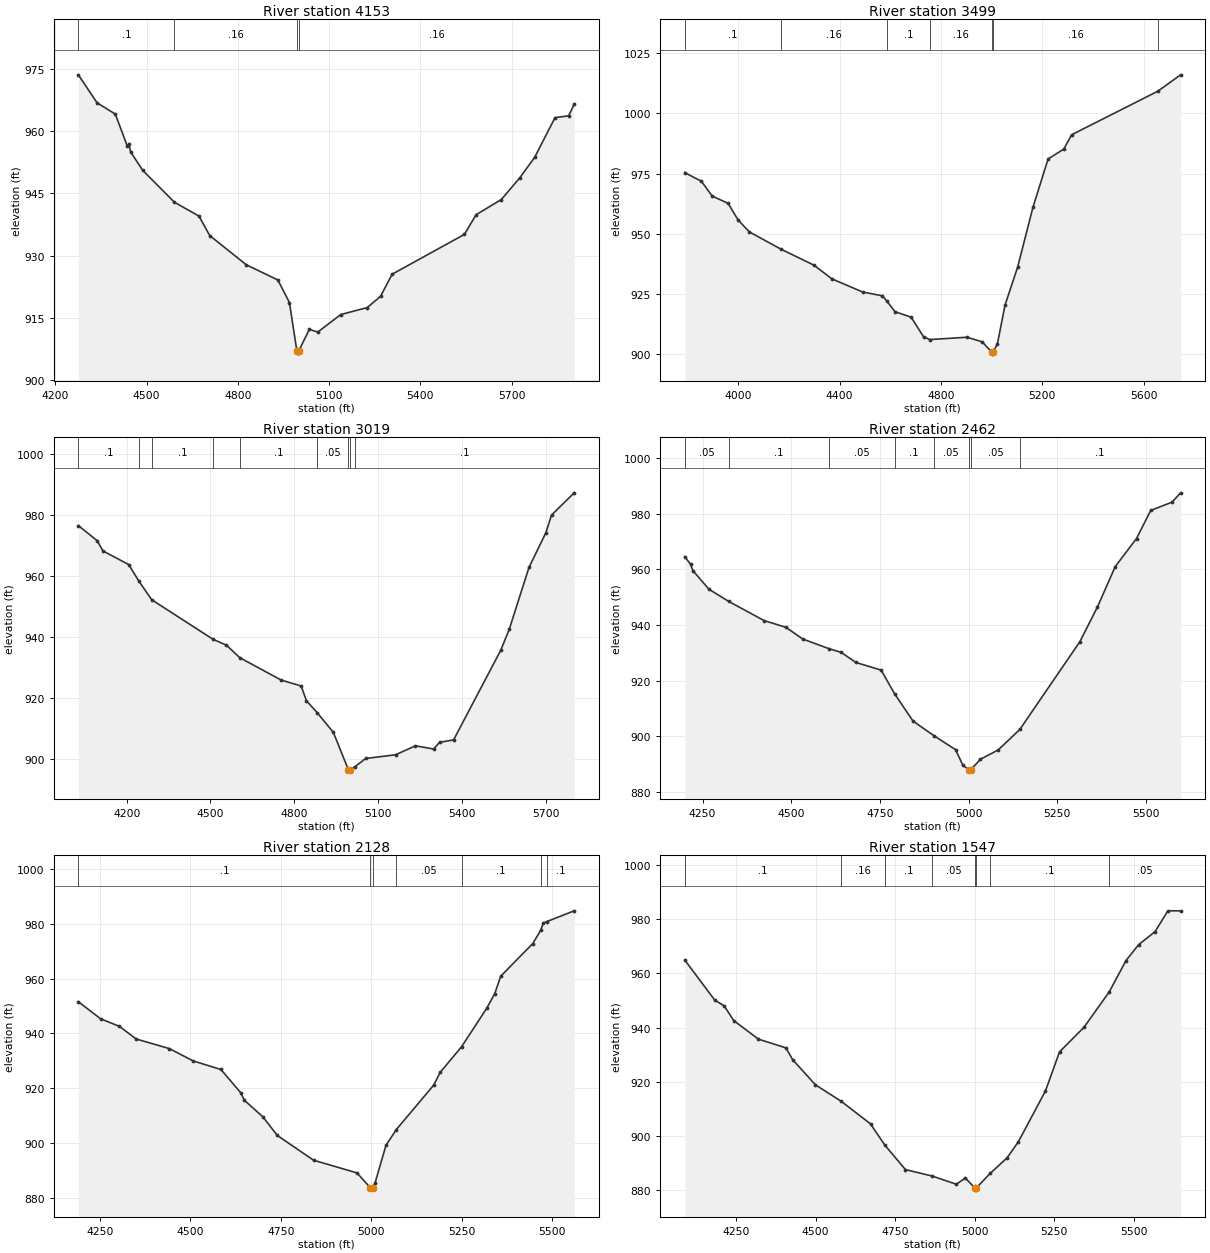
Type RM Length L Ch R = 1,4153,654,654,654
BEGIN DESCRIPTION:
HAMILTON CREEK TRIB 2 9.0
END DESCRIPTION:
XS GIS Cut Line= 4
      2993707.04     10087831.52      2994305.98     10087857.56
      2994545.56     10087420.06      2994633.78     10086895.94
#Sta/Elev= 30
  4275.8  973.63  4337.3  966.88  4397.3  964.16  4437.1  956.37  4442.1  957.04
  4447.4  955.07  4487.4  950.58  4591.8  942.87  4672.4  939.54  4707.6  934.85
  4827.7  927.80  4931.8  924.11  4969.7  918.68  4994.2  906.97  4996.9  906.47
  5000.2  906.97  5035.1  912.21  5062.6  911.54  5138.5  915.78  5225.7  917.47
  5269.3  920.19  5307.2  925.51  5545.0  935.13  5583.3  939.87  5666.1  943.53
  5726.7  948.76  5776.0  953.74  5842.7  963.30  5887.6  963.74  5905.6  966.53
#Mann=4,-1,0
  4275.8     0.1       0  4591.8    0.16       0  4994.2    0.07       0
  5000.2    0.16       0
Bank Sta=4994.2,5000.2
Exp/Cntr=0.3,0.1

Type RM Length L Ch R = 1,3499,480,480,480
BEGIN DESCRIPTION:
HAMILTON CREEK TRIB 2 8.0
END DESCRIPTION:
XS GIS Cut Line= 4
      2993675.77     10087873.18      2994483.06     10088133.60
      2995087.23     10088164.85      2995571.60     10088305.47
#Sta/Elev= 30
  3788.8  975.40  3854.7  971.77  3896.7  965.68  3959.8  962.64  3999.4  955.72
  4043.8  950.79  4170.2  943.55  4298.4  937.03  4369.5  931.33  4490.6  925.89
  4569.2  924.29  4585.8  922.21  4618.8  917.72  4682.5  915.42  4732.0  907.22
  4756.5  906.16  4902.8  907.12  4962.9  905.23  5000.0  901.03  5002.7  900.53
  5006.0  901.03  5023.0  904.35  5053.0  920.42  5103.1  936.27  5163.2  960.94
  5223.2  981.06  5285.0  985.13  5316.2  991.09  5655.8 1009.11  5746.4 1015.94
#Mann=7,-1,0
  3788.8     0.1       0  4170.2    0.16       0  4585.8     0.1       0
  4756.5    0.16       0  5000.0    0.07       0  5006.0    0.16       0
  5655.8    0.05       0
Bank Sta=5000,5006
Exp/Cntr=0.3,0.1

Type RM Length L Ch R = 1,3019,557,557,557
BEGIN DESCRIPTION:
HAMILTON CREEK TRIB 2 7.0
END DESCRIPTION:
XS GIS Cut Line= 4
      2993602.87     10088029.44      2994399.73     10088222.14
      2994707.02     10088654.43      2995128.91     10088706.52
#Sta/Elev= 30
  4026.8  976.57  4094.3  971.61  4114.9  968.25  4207.5  963.74  4243.0  958.40
  4289.6  952.22  4508.6  939.27  4557.3  937.30  4604.9  933.21  4752.7  925.88
  4824.7  923.91  4843.4  919.10  4882.7  915.09  4940.0  908.68  4993.5  896.48
  4996.3  895.98  4999.5  896.48  5017.1  897.42  5055.6  900.13  5162.6  901.34
  5233.9  904.30  5299.1  903.23  5320.0  905.42  5370.4  906.23  5539.7  935.73
  5569.9  942.58  5640.4  962.83  5700.9  974.23  5721.0  980.00  5802.1  987.31
#Mann=9,-1,0
  4026.8     0.1       0  4243.0    0.05       0  4289.6     0.1       0
  4508.6    0.16       0  4604.9     0.1       0  4882.7    0.05       0
  4993.5   0.035       0  4999.5    0.05       0  5017.1     0.1       0
Bank Sta=4993.5,4999.5
Exp/Cntr=0.3,0.1

Type RM Length L Ch R = 1,2462,334,334,334
BEGIN DESCRIPTION:
HAMILTON CREEK TRIB 2 6.0
END DESCRIPTION:
XS GIS Cut Line= 3
      2993722.69     10088732.57      2994227.85     10088867.97
      2995102.89     10088878.39
#Sta/Elev= 30
  4199.8  964.60  4216.1  961.84  4222.5  959.60  4267.9  952.88  4323.6  948.50
  4423.2  941.62  4485.3  939.15  4532.3  934.97  4607.4  931.45  4640.6  930.19
  4682.0  926.55  4753.4  923.79  4791.2  915.31  4843.4  905.44  4902.1  900.22
  4963.4  895.16  4983.4  889.67  5000.4  887.95  5003.2  887.45  5006.4  887.95
  5033.4  891.73  5083.4  895.05  5144.4  902.43  5313.5  933.95  5363.5  946.53
  5413.5  961.02  5473.5  971.12  5513.5  981.21  5573.5  984.20  5597.9  987.56
#Mann=8,-1,0
  4199.8    0.05       0  4323.6     0.1       0  4607.4    0.05       0
  4791.2     0.1       0  4902.1    0.05       0  5000.4   0.035       0
  5006.4    0.05       0  5144.4     0.1       0
Bank Sta=5000.4,5006.4
Exp/Cntr=0.3,0.1

Type RM Length L Ch R = 1,2128,581,581,581
BEGIN DESCRIPTION:
HAMILTON CREEK TRIB 2 4.0
END DESCRIPTION:
XS GIS Cut Line= 4
      2993738.27     10089003.39      2994160.14     10089190.89
      2994764.31     10089211.72      2995034.29     10089351.91
#Sta/Elev= 30
  4190.3  951.57  4251.7  945.33  4303.7  942.56  4350.2  937.95  4442.2  934.42
  4507.9  929.93  4584.5  926.81  4639.2  918.30  4649.3  915.57  4700.3  909.53
  4740.3  902.72  4840.4  893.69  4960.5  889.05  4997.5  883.63  5000.2  883.13
  5003.5  883.63  5010.5  885.43  5040.5  899.08  5069.3  904.90  5172.6  921.12
  5190.6  925.80  5249.4  935.09  5319.1  949.18  5341.2  954.49  5357.7  960.86
  5446.2  972.78  5468.1  977.59  5475.3  980.29  5484.7  980.79  5560.7  984.74
#Mann=7,-1,0
  4190.3     0.1       0  4997.5    0.07       0  5003.5     0.1       0
  5069.3    0.05       0  5249.4     0.1       0  5468.1    0.05       0
  5484.7     0.1       0
Bank Sta=4997.5,5003.5
Exp/Cntr=0.3,0.1

Type RM Length L Ch R = 1,1547,452,452,452
BEGIN DESCRIPTION:
HAMILTON CREEK TRIB 2 3.0
END DESCRIPTION:
XS GIS Cut Line= 3
      2993550.81     10089269.04      2994066.39     10089623.18
      2994914.43     10090013.38
#Sta/Elev= 30
  4088.6  964.94  4182.8  950.15  4212.4  948.05  4242.2  942.61  4320.0  935.73
  4406.6  932.50  4427.6  928.15  4499.3  918.85  4579.8  912.81  4672.5  904.42
  4717.3  896.59  4782.4  887.52  4866.5  885.13  4942.4  882.11  4970.8  884.42
  4999.6  880.80  5002.3  880.30  5005.6  880.80  5049.1  886.15  5101.7  891.84
  5137.1  897.74  5222.7  916.60  5266.8  931.01  5343.8  940.11  5423.4  953.24
  5475.9  964.78  5515.6  970.64  5567.1  975.44  5607.5  983.14  5647.6  983.14
#Mann=8,-1,0
  4088.6     0.1       0  4579.8    0.16       0  4717.3     0.1       0
  4866.5    0.05       0  4999.6   0.035       0  5005.6    0.05       0
  5049.1     0.1       0  5423.4    0.05       0
Bank Sta=4999.6,5005.6
Exp/Cntr=0.3,0.1