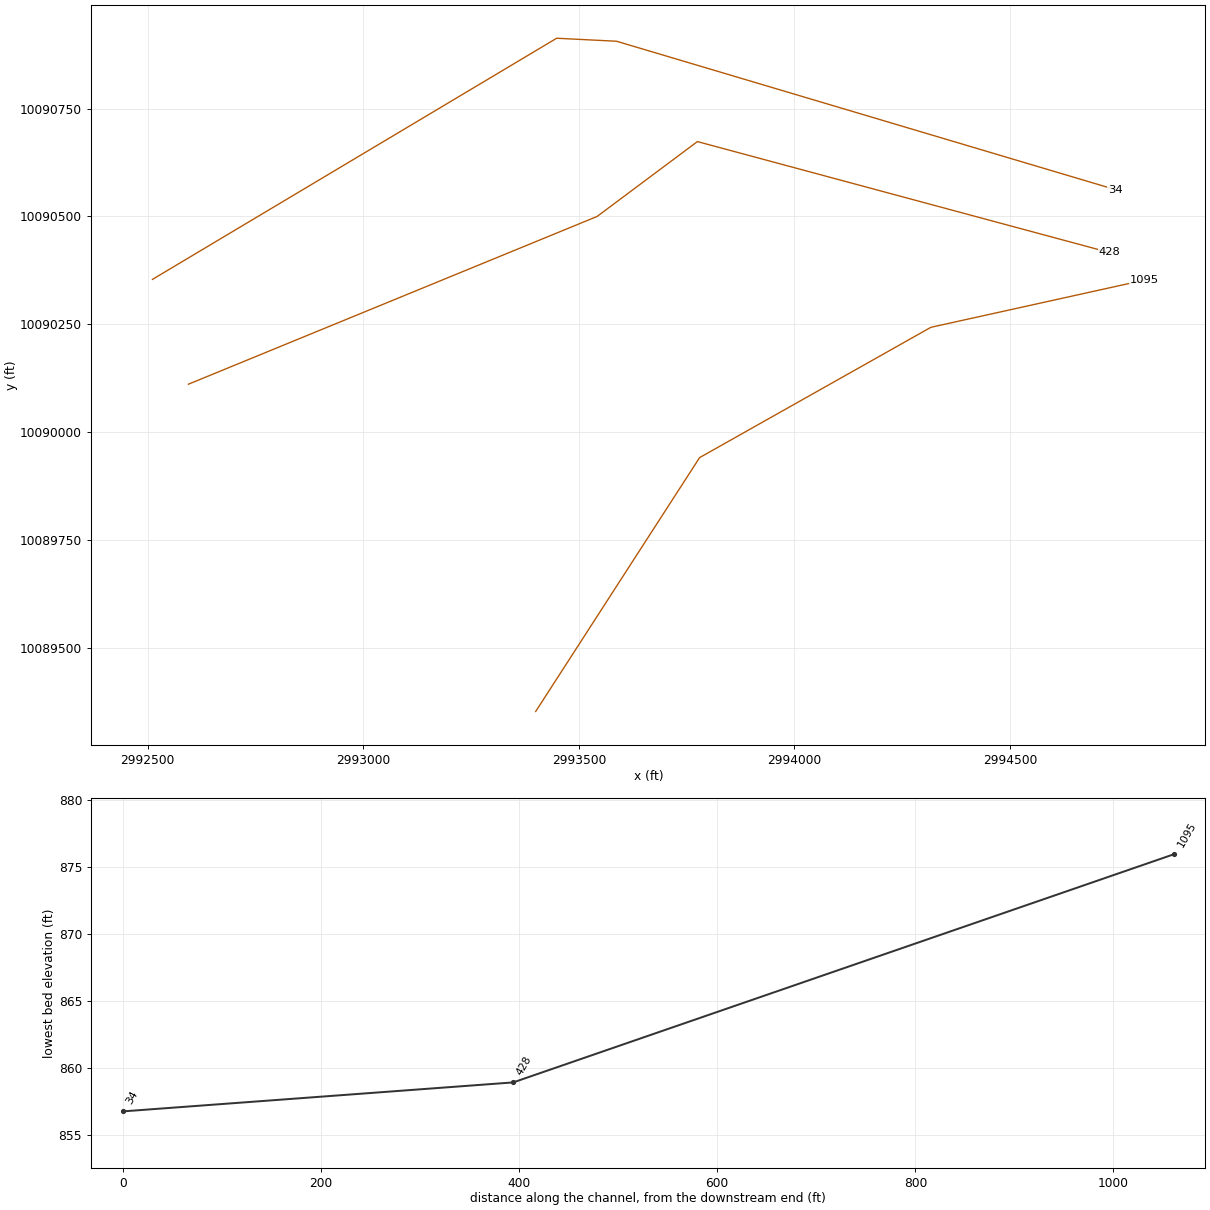
HEC-RAS study HAMILTON CREEK TRIB 2.prj: HAMILTON CREEK TRIB 2 Base Level Engineering

--- HAMILTON CREEK TRIB 2.g01 (geometry) --- (continued)

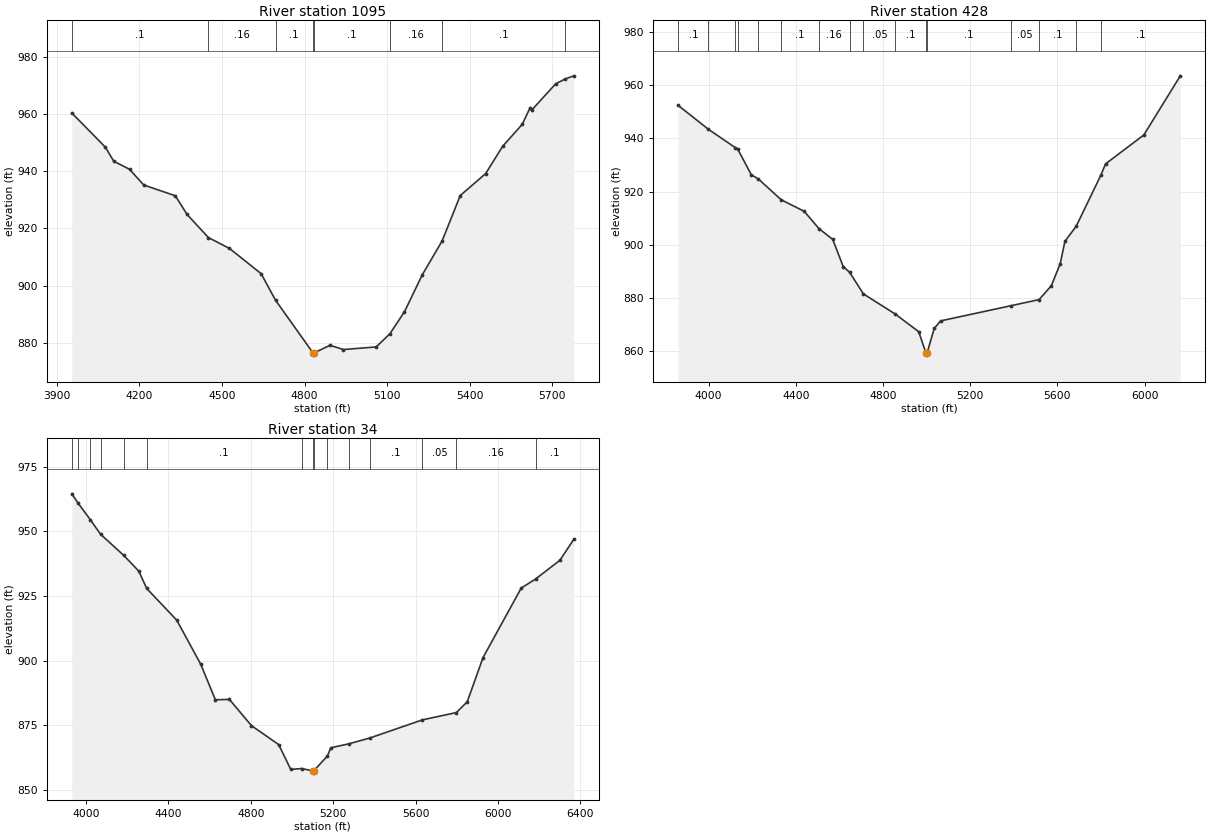
Type RM Length L Ch R = 1,1095,667,667,667
BEGIN DESCRIPTION:
HAMILTON CREEK TRIB 2 2.0
END DESCRIPTION:
XS GIS Cut Line= 4
      2993399.74     10089352.37      2993779.94     10089940.89
      2994316.39     10090242.97      2994811.14     10090352.34
#Sta/Elev= 30
  3954.8  960.53  4076.8  948.52  4107.2  943.59  4164.6  940.76  4216.0  935.26
  4330.8  931.48  4373.1  924.96  4450.9  916.82  4527.4  913.01  4642.2  904.17
  4694.6  894.85  4830.1  876.43  4832.8  875.93  4836.1  876.43  4892.3  879.02
  4941.4  877.54  5059.9  878.45  5109.5  883.03  5162.5  890.73  5227.6  903.78
  5299.4  915.60  5365.4  931.57  5457.6  939.26  5519.0  948.79  5590.7  956.56
  5619.2  962.43  5624.3  961.48  5711.6  970.73  5746.6  972.46  5777.8  973.55
#Mann=8,-1,0
  3954.8     0.1       0  4450.9    0.16       0  4694.6     0.1       0
  4830.1    0.07       0  4836.1     0.1       0  5109.5    0.16       0
  5299.4     0.1       0  5746.6    0.05       0
Bank Sta=4830.1,4836.1
Exp/Cntr=0.3,0.1

Type RM Length L Ch R = 1,428,394,394,394
BEGIN DESCRIPTION:
Mapping XS db1c2578
END DESCRIPTION:
XS GIS Cut Line= 4
      2992594.21     10090111.06      2993542.13     10090499.95
      2993774.77     10090673.56      2994729.63     10090416.62
#Sta/Elev= 30
  3860.3  952.38  3998.6  943.43  4122.9  936.48  4132.3  936.09  4195.6  926.34
  4227.8  924.75  4332.6  916.94  4438.5  912.58  4506.1  906.08  4569.2  902.03
  4617.2  891.83  4647.1  889.62  4709.8  881.56  4856.8  873.94  4963.9  867.33
  4996.4  859.42  4999.1  858.92  5002.4  859.42  5034.8  868.56  5064.0  871.41
  5387.2  877.12  5516.3  879.42  5572.5  884.66  5612.9  892.90  5634.7  901.35
  5686.4  906.98  5798.9  926.08  5821.1  930.42  5996.9  941.31  6164.0  963.51
#Mann=16,-1,0
  3860.3     0.1       0  3998.6    0.16       0  4122.9     0.1       0
  4132.3    0.16       0  4227.8    0.05       0  4332.6     0.1       0
  4506.1    0.16       0  4647.1     0.1       0  4709.8    0.05       0
  4856.8     0.1       0  4996.4    0.07       0  5002.4     0.1       0
  5387.2    0.05       0  5516.3     0.1       0  5686.4    0.16       0
  5798.9     0.1       0
Bank Sta=4996.4,5002.4
Exp/Cntr=0.3,0.1

Type RM Length L Ch R = 1,34,0,0,0
BEGIN DESCRIPTION:
HAMILTON CREEK TRIB 2 1.0
END DESCRIPTION:
XS GIS Cut Line= 4
      2992510.92     10090354.14      2993448.38     10090913.15
      2993587.27     10090906.20      2994743.51     10090562.45
#Sta/Elev= 30
  3931.5  964.58  3962.9  960.90  4021.2  954.59  4071.0  948.94  4183.1  940.78
  4256.7  934.64  4295.1  927.92  4440.9  915.65  4557.4  898.56  4628.4  884.80
  4696.6  884.93  4803.6  874.78  4936.0  867.41  4994.4  857.79  5047.3  858.16
  5100.2  857.26  5102.9  856.76  5106.2  857.26  5172.5  863.04  5188.8  866.19
  5276.8  867.73  5379.1  870.01  5633.4  877.01  5798.1  879.84  5850.8  884.00
  5927.6  901.14  6112.7  928.04  6182.7  931.59  6300.4  938.82  6368.3  946.98
#Mann=15,-1,0
  3931.5    0.05       0  3962.9     0.1       0  4021.2    0.05       0
  4071.0     0.1       0  4183.1    0.16       0  4295.1     0.1       0
  5047.3    0.16       0  5100.2    0.07       0  5106.2    0.16       0
  5172.5     0.1       0  5276.8    0.16       0  5379.1     0.1       0
  5633.4    0.05       0  5798.1    0.16       0  6182.7     0.1       0
Bank Sta=5100.2,5106.2
Exp/Cntr=0.3,0.1

Chan Stop Cuts=-1