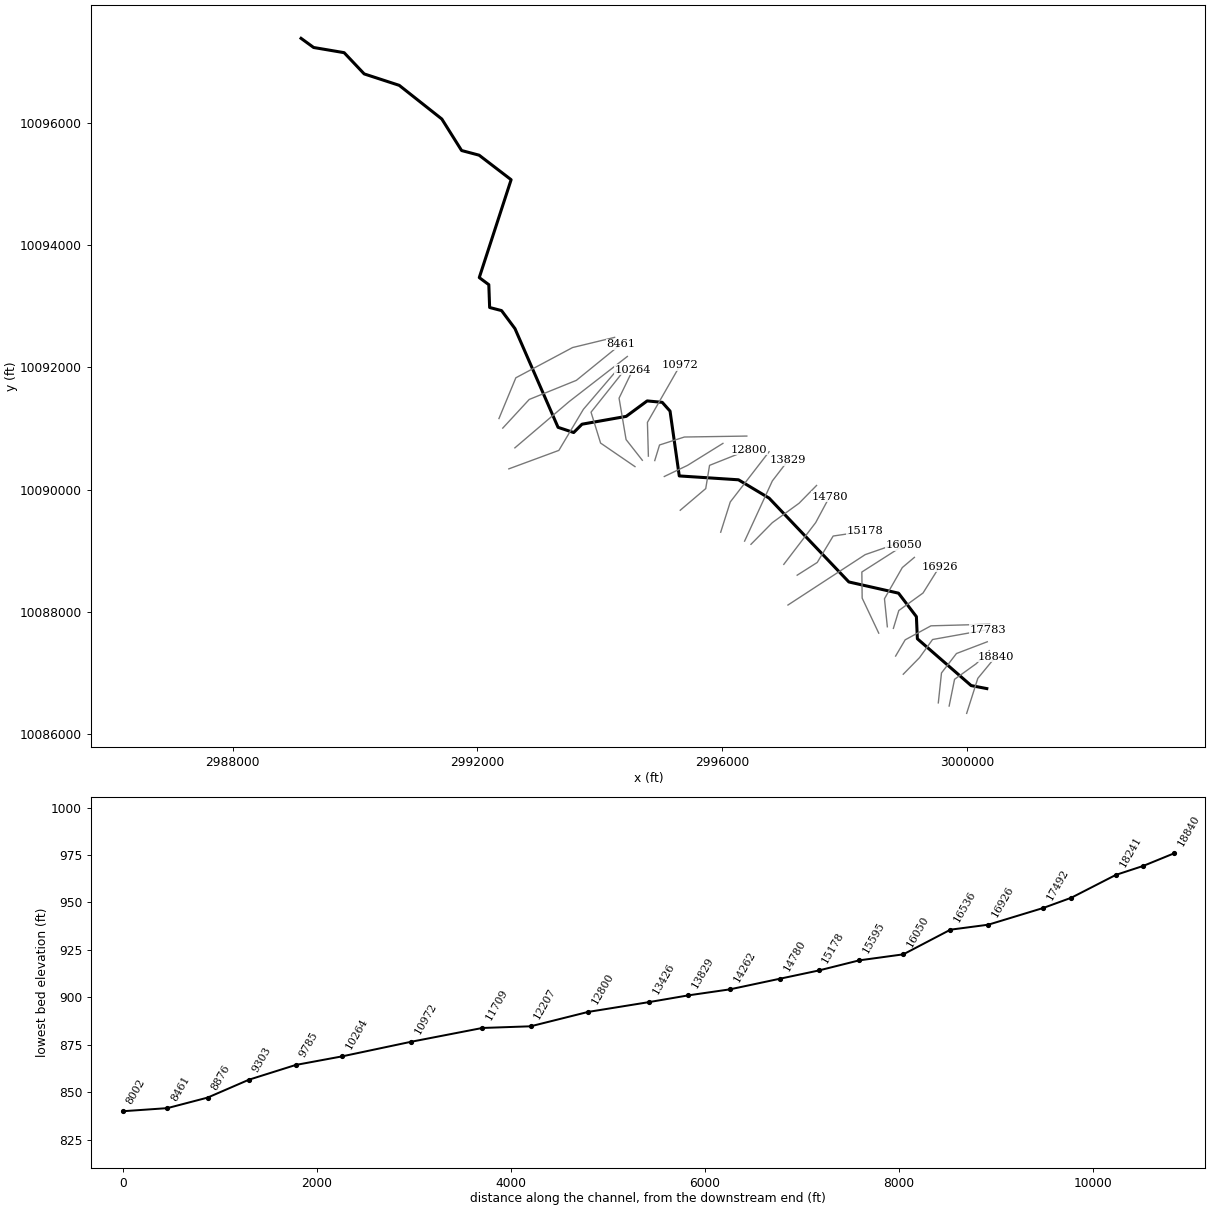
--- HAMILTON CREEK.prj (project) ---

Proj Title=HAMILTON CREEK Base Level Engineering
Current Plan=p01
Default Exp/Contr=0.3,0.1
English Units
Geom File=g01
Flow File=f01
Plan File=p01
Y Axis Title=Elevation
X Axis Title(PF)=Main Channel Distance
X Axis Title(XS)=Station
BEGIN DESCRIPTION:
HAMILTON CREEK
END DESCRIPTION:
DSS Export Rating Curves= 0
DSS Export Rating Curve Sorted= 0
DSS Export Volume Flow Curves= 0
DXF OffsetX= 0
DXF OffsetY= 0
DXF ScaleX= 1
DXF ScaleY= 10

--- HAMILTON CREEK.p01 (plan) ---

Plan Title=Multiple Run
Short Identifier=Multiple
Geom File=g01
Flow File=f01
Subcritical Flow
K Sum by GR= 0
Std Step Tol= 0.01
Critical Tol= 0.01
Num of Std Step Trials= 20
Max Error Tol= 0.3
Flow Tol Ratio= 0.001
Split Flow NTrial= 30
Split Flow Tol= 0.02
Split Flow Ratio= 0.02
Log Output Level= 0
Friction Slope Method= 1
Unsteady Friction Slope Method= 2
Unsteady Bridges Friction Slope Method= 1
Parabolic Critical Depth
Global Vel Dist=  1 , 1 , 1
Global Log Level= 0
CheckData=True
Encroach Param= -1, 0, 0, 0
BEGIN DESCRIPTION:
Multiple Run
END DESCRIPTION:

--- HAMILTON CREEK.f01 (steady flow) ---

Flow Title=Multiple
Program Version=4.10
Number of Profiles= 7
Profile Names=10-year,25-year,50-year,1pct_min,100-year,1pct_plu,500-year
River Rch & RM=HAMILTON CREEK,Reach-1         ,18840
    1017    1492    1912    1795    2428    3283    3925
River Rch & RM=HAMILTON CREEK,Reach-1         ,17783
    1382    2062    2671    2532    3424    4631    5648
River Rch & RM=HAMILTON CREEK,Reach-1         ,15595
    2439    3705    4854    4641    6276    8488   10537
River Rch & RM=HAMILTON CREEK,Reach-1         ,9303
    3914    6078    8082    7832   10592   14325   18277
River Rch & RM=HAMILTON CREEK,Reach-1         ,8876
    3914    6078    8082    7832   10592   14325   18277
Boundary for River Rch & Prof#=HAMILTON CREEK,Reach-1         , 1
Up Type= 0
Dn Type= 3
Dn Slope=0.025
Boundary for River Rch & Prof#=HAMILTON CREEK,Reach-1         , 2
Up Type= 0
Dn Type= 3
Dn Slope=0.025
Boundary for River Rch & Prof#=HAMILTON CREEK,Reach-1         , 3
Up Type= 0
Dn Type= 3
Dn Slope=0.025
Boundary for River Rch & Prof#=HAMILTON CREEK,Reach-1         , 4
Up Type= 0
Dn Type= 3
Dn Slope=0.025
Boundary for River Rch & Prof#=HAMILTON CREEK,Reach-1         , 5
Up Type= 0
Dn Type= 3
Dn Slope=0.025
Boundary for River Rch & Prof#=HAMILTON CREEK,Reach-1         , 6
Up Type= 0
Dn Type= 3
Dn Slope=0.025
Boundary for River Rch & Prof#=HAMILTON CREEK,Reach-1         , 7
Up Type= 0
Dn Type= 3
Dn Slope=0.025
DSS Import GetInterval= 0
DSS Import GetPeak= 0
DSS Import FillOption= 0

--- HAMILTON CREEK.g01 (geometry) ---

Geom Title=Existing Conditions
Program Version=4.10

River Reach=HAMILTON CREEK  ,Reach-1
Reach XY= 30
       3000326.8      10086745.4      3000070.49     10086794.75
      2999191.96     10087560.32      2999175.69     10087922.17
      2998883.49     10088306.35      2998071.66     10088489.69
      2996767.66     10089861.31      2996267.33     10090160.98
      2995299.32     10090224.25      2995148.48     10091284.69
      2995020.89     10091428.19      2994774.46     10091451.26
      2994431.27     10091198.25      2993709.46     10091070.49
      2993573.41     10090934.04      2993317.82     10091019.18
      2992613.41     10092634.24       2992394.2     10092928.87
      2992199.31     10092979.62      2992185.84     10093352.72
      2992029.83     10093468.93      2992550.53     10095070.15
      2992027.43     10095471.23      2991740.96      10095547.4
      2991417.64     10096062.94      2990721.51      10096613.7
      2990148.73      10096800.6       2989820.9     10097148.25
      2989322.15      10097232.9      2989116.45     10097382.71

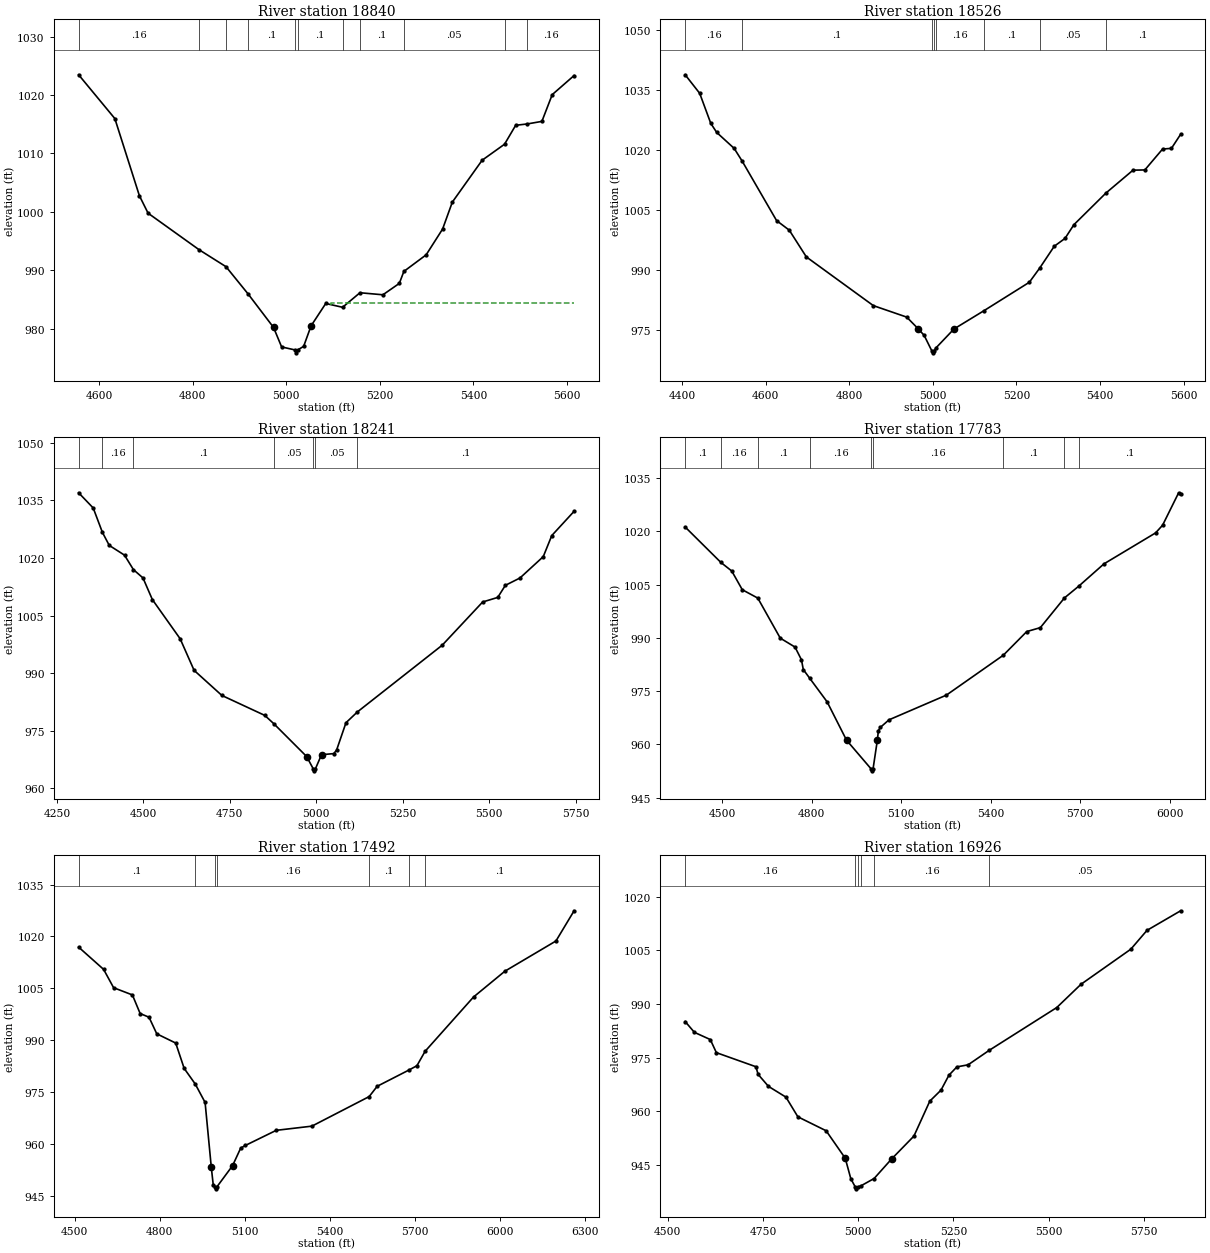
Type RM Length L Ch R = 1 ,18840   ,314,314,314
BEGIN DESCRIPTION:
HAMILTON CREEK 43.0
END DESCRIPTION:
XS GIS Cut Line= 3
      2999997.52     10086339.88      3000179.82     10086912.82
      3000471.46     10087266.95
#Sta/Elev= 30
  4555.6 1023.45  4633.1 1015.95  4685.6 1002.74  4704.2  999.75  4813.4  993.49
  4870.9  990.59    4918  985.94  4972.6  980.19  4989.9  976.85  5018.4  976.34
  5021.1  975.84  5024.4  976.34    5037  976.95  5052.9  980.46  5084.3  984.29
  5120.3  983.64  5157.5  986.13  5206.6  985.78  5241.7  987.73  5251.4  989.78
  5299.1  992.62  5334.3  997.04  5355.1 1001.65  5418.9 1008.82  5466.8 1011.56
  5490.6  1014.8  5515.3 1015.03  5546.7 1015.47  5568.8 1020.05  5615.6 1023.32
#Mann= 11 ,-1 , 0
  4555.6     .16       0  4813.4     .05       0  4870.9     .16       0
    4918      .1       0  5018.4     .07       0  5024.4      .1       0
  5120.3     .16       0  5157.5      .1       0  5251.4     .05       0
  5466.8      .1       0  5515.3     .16       0
#XS Ineff= 2 , 0
                         5094.98          984.41
Permanent Ineff=
       T       T
Bank Sta=4972.6,5052.9
XS Rating Curve= 0 ,0
Exp/Cntr=0.3,0.1

Type RM Length L Ch R = 1 ,18526   ,285,285,285
BEGIN DESCRIPTION:
HAMILTON CREEK 42.0
END DESCRIPTION:
XS GIS Cut Line= 4
      2999711.07     10086459.72      2999799.61      10086897.2
      3000153.78     10087152.41      3000367.33     10087365.96
#Sta/Elev= 30
  4407.8 1038.78  4442.5 1034.15  4469.1 1026.62  4483.3 1024.36    4525 1020.38
  4544.4 1017.15  4626.4 1002.34  4656.8  999.94  4697.6  993.26  4857.8  981.09
  4937.6  978.22  4964.6  975.35  4979.3  973.66  4997.6  969.79  5000.4  969.29
  5003.6  969.79  5006.9  970.45  5050.5  975.24  5123.1  979.87  5230.9  986.93
  5255.7  990.48  5290.5  995.93  5316.2  997.89  5337.4 1001.31  5414.1 1009.23
  5478.8 1014.94  5507.1    1015  5549.5 1020.22  5570.7 1020.39  5592.7 1023.91
#Mann= 8 ,-1 , 0
  4407.8     .16       0  4544.4      .1       0  4997.6     .07       0
  5003.6      .1       0  5006.9     .16       0  5123.1      .1       0
  5255.7     .05       0  5414.1      .1       0
Bank Sta=4964.6,5050.5
XS Rating Curve= 0 ,0
Exp/Cntr=0.3,0.1

Type RM Length L Ch R = 1 ,18241   ,458,458,458
BEGIN DESCRIPTION:
HAMILTON CREEK 41.0
END DESCRIPTION:
XS GIS Cut Line= 4
      2999533.98     10086511.75      2999586.07     10087001.37
      2999830.86     10087319.07      3000334.79     10087511.29
#Sta/Elev= 30
  4312.9    1037  4355.1 1033.03  4381.6 1026.69  4401.5 1023.28  4445.6 1020.74
  4471.4 1016.96    4499  1014.8  4526.1 1009.16  4606.5  998.94  4646.8  990.71
  4727.2  984.16  4851.3  978.96  4877.3   976.8  4972.4  968.23  4991.5  965.01
  4994.2  964.51  4997.5  965.01  5015.3  968.72  5050.6     969  5058.8   969.9
    5086  977.05  5119.3  979.89  5364.3  997.26  5481.3 1008.53  5524.9 1009.72
  5546.9 1012.87  5589.1 1014.78  5656.5 1020.35  5681.2 1025.85  5745.7 1032.17
#Mann= 7 ,-1 , 0
  4312.9      .1       0  4381.6     .16       0  4471.4      .1       0
  4877.3     .05       0  4991.5    .035       0  4997.5     .05       0
  5119.3      .1       0
Bank Sta=4972.4,5015.3
XS Rating Curve= 0 ,0
Exp/Cntr=0.3,0.1

Type RM Length L Ch R = 1 ,17783   ,291,291,291
BEGIN DESCRIPTION:
HAMILTON CREEK 40.0
END DESCRIPTION:
XS GIS Cut Line= 4
      2998961.04      10086980.5      2999226.69     10087251.37
      2999440.24     10087548.24      3000341.29      10087709.7
#Sta/Elev= 30
  4376.4  1021.2  4496.3 1011.21  4532.5 1008.81  4567.8 1003.54  4619.8 1001.18
  4695.1   989.9  4744.6  987.38  4766.1   983.8  4772.3  981.05  4793.7  978.61
  4852.1  971.96  4917.1  961.17    5000  953.02  5002.8  952.52    5006  953.02
 5020.45  961.15  5023.9  963.81  5030.1  964.73  5059.5  966.89  5251.8  973.85
  5442.6  985.09  5521.1  991.75  5566.7  992.86  5647.6 1001.24  5695.1 1004.52
    5780 1010.83  5952.8 1019.54  5976.4 1021.71  6030.2 1030.85  6036.9 1030.38
#Mann= 9 ,-1 , 0
  4376.4      .1       0  4496.3     .16       0  4619.8      .1       0
  4793.7     .16       0    5000     .07       0    5006     .16       0
  5442.6      .1       0  5647.6     .16       0  5695.1      .1       0
Bank Sta=4917.1,5020.45
XS Rating Curve= 0 ,0
Exp/Cntr=0.3,0.1

Type RM Length L Ch R = 1 ,17492   ,566,566,566
BEGIN DESCRIPTION:
HAMILTON CREEK 39.0
END DESCRIPTION:
XS GIS Cut Line= 4
      2998836.07     10087277.42      2998992.32     10087543.03
      2999414.19      10087772.2      3000372.48     10087798.24
#Sta/Elev= 30
  4513.8 1016.92  4601.9 1010.49  4637.1  1005.2  4703.4 1003.11  4730.7  997.74
    4762  996.67  4789.3  991.88  4856.1  989.21  4885.9  981.89  4924.8   977.4
  4959.7  972.06  4981.6  953.28  4988.3  948.32  4994.7   947.6  4997.5   947.1
  5000.7   947.6  5056.6   953.8  5085.2  958.87  5101.3  959.62  5210.6     964
  5336.3  965.21  5538.2  973.75  5566.4  976.72  5677.5  981.38  5706.5  982.66
  5735.4  986.83  5906.1 1002.51  6016.6 1009.96  6196.7 1018.69  6260.7 1027.42
#Mann= 7 ,-1 , 0
  4513.8      .1       0  4924.8     .16       0  4994.7     .07       0
  5000.7     .16       0  5538.2      .1       0  5677.5     .16       0
  5735.4      .1       0
Bank Sta=4981.6,5056.6
XS Rating Curve= 0 ,0
Exp/Cntr=0.3,0.1

Type RM Length L Ch R = 1 ,16926   ,390,390,390
BEGIN DESCRIPTION:
HAMILTON CREEK 38.0
END DESCRIPTION:
XS GIS Cut Line= 4
      2998799.62     10087730.57      2998888.15      10088022.2
      2999283.99     10088308.66      2999553.44     10088738.74
#Sta/Elev= 30
  4545.9  985.09  4570.1  982.07  4611.9  980.05  4627.8  976.39  4731.7  972.45
  4737.3  970.33  4764.6  966.96  4810.5  963.95  4841.8  958.45    4916  954.55
  4966.2  946.86  4980.9  941.11  4992.6  938.81  4995.4  938.31  4998.6  938.81
  5007.7  939.17    5042   941.2  5087.7  946.64  5146.5  953.06  5188.2  962.83
  5217.6  965.91  5238.5   970.1  5259.3  972.41  5288.8  972.99  5344.2  977.04
  5521.5     989  5585.2  995.51    5716 1005.32  5758.4 1010.58  5846.8 1016.06
#Mann= 6 ,-1 , 0
  4545.9     .16       0  4992.6     .07       0  4998.6     .16       0
  5007.7     .05       0    5042     .16       0  5344.2     .05       0
Bank Sta=4966.2,5087.7
XS Rating Curve= 0 ,0
Exp/Cntr=0.3,0.1

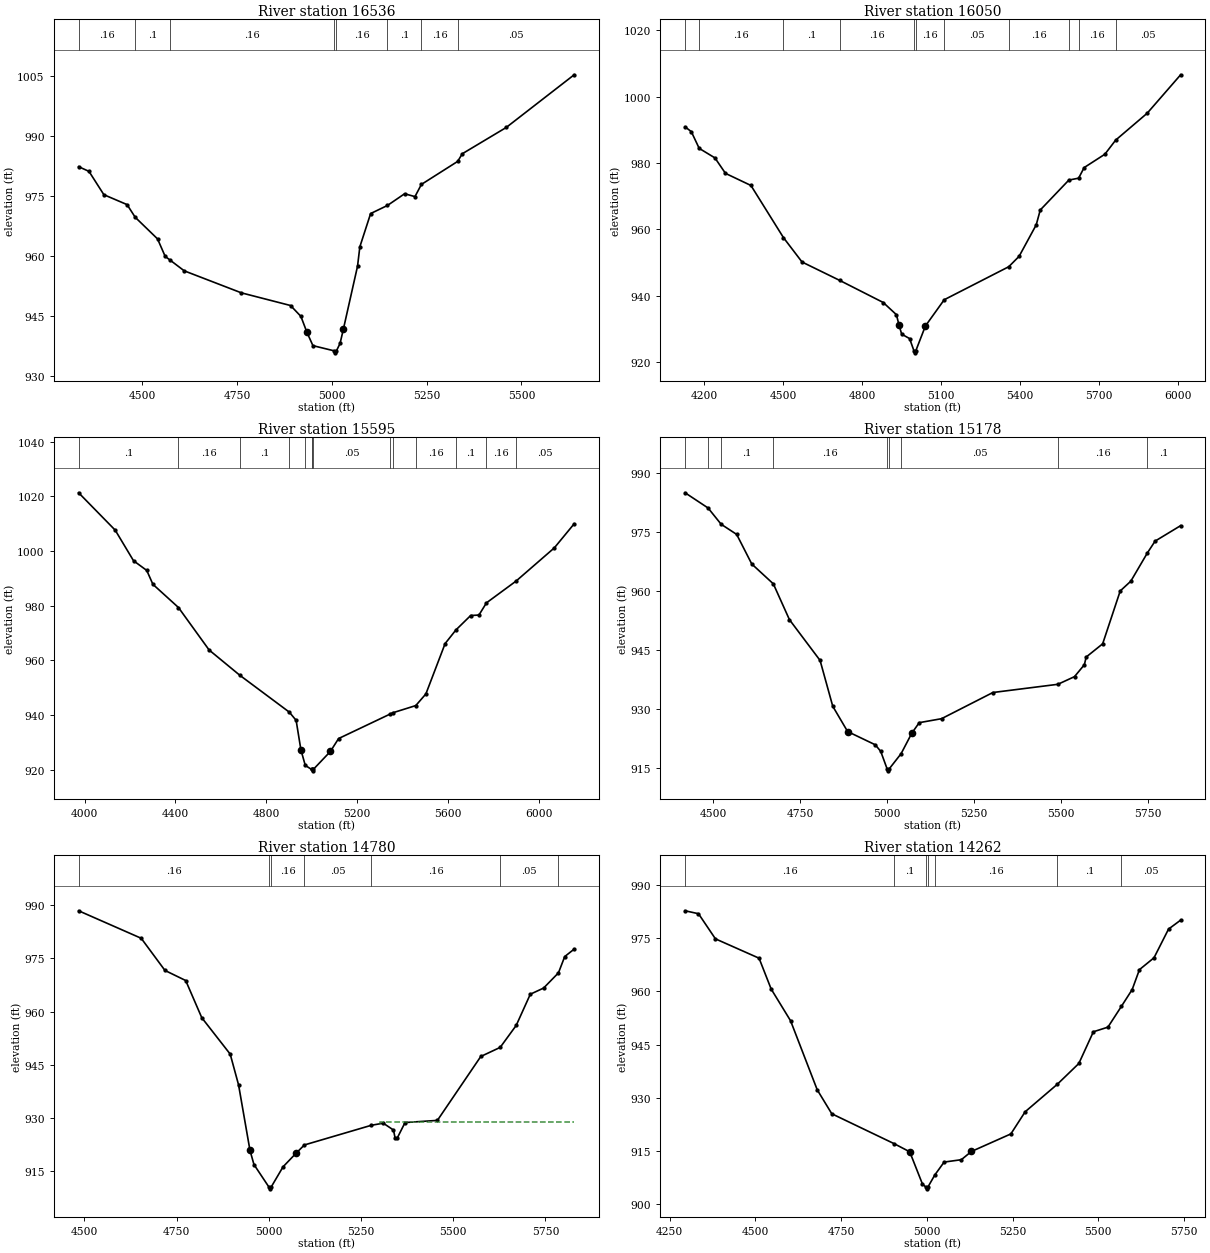
Type RM Length L Ch R = 1 ,16536   ,486,486,486
BEGIN DESCRIPTION:
HAMILTON CREEK 37.0
END DESCRIPTION:
XS GIS Cut Line= 4
      2998700.65     10087756.58      2998653.78     10088214.91
      2998945.44     10088725.32      2999143.34     10088891.97
#Sta/Elev= 30
  4331.8  982.27  4359.1   981.1  4398.4  975.26  4459.6  972.78    4481  969.62
    4540   964.2  4560.1  959.83    4572  958.97  4610.4  956.21  4761.2   950.7
  4890.9  947.53  4918.2  944.81  4934.1  940.82  4949.9  937.49  5005.9  936.19
  5008.7  935.69  5011.9  936.19  5021.5  938.04  5030.5  941.73  5067.6  957.38
  5073.7  962.23  5102.1  970.54  5146.5  972.57  5191.8   975.5  5219.1  974.78
    5236  977.83  5331.7  983.59    5344  985.51  5459.8  992.08  5639.1 1005.27
#Mann= 8 ,-1 , 0
  4331.8     .16       0    4481      .1       0    4572     .16       0
  5005.9     .07       0  5011.9     .16       0  5146.5      .1       0
    5236     .16       0  5331.7     .05       0
Bank Sta=4934.1,5030.5
XS Rating Curve= 0 ,0
Exp/Cntr=0.3,0.1

Type RM Length L Ch R = 1 ,16050   ,455,455,455
BEGIN DESCRIPTION:
HAMILTON CREEK 36.0
END DESCRIPTION:
XS GIS Cut Line= 4
      2998560.04     10087652.38      2998289.19     10088225.32
      2998283.99     10088652.41      2998975.06     10089094.07
#Sta/Elev= 30
  4128.7  990.86  4152.3  989.41  4182.2  984.37    4242  981.49    4282  976.83
  4378.6  973.18  4502.1  957.45  4572.6   950.1  4715.4  944.56  4880.8  937.89
  4930.9  934.21  4940.9  931.01  4950.9  928.34  4980.9  927.01  4997.9  923.21
  5000.6  922.71  5003.9  923.21  5040.9  930.81  5112.3  938.72  5357.3  948.68
  5396.6  951.82  5461.6  961.32  5476.8  965.78  5585.4  974.81  5622.4  975.38
  5643.4  978.57  5722.1   982.6  5763.1  986.86  5882.8  994.97  6009.7 1006.56
#Mann= 11 ,-1 , 0
  4128.7      .1       0  4182.2     .16       0  4502.1      .1       0
  4715.4     .16       0  4997.9     .07       0  5003.9     .16       0
  5112.3     .05       0  5357.3     .16       0  5585.4      .1       0
  5622.4     .16       0  5763.1     .05       0
Bank Sta=4940.9,5040.9
XS Rating Curve= 0 ,0
Exp/Cntr=0.3,0.1

Type RM Length L Ch R = 1 ,15595   ,417,417,417
BEGIN DESCRIPTION:
HAMILTON CREEK 35.0
END DESCRIPTION:
XS GIS Cut Line= 3
      2997076.06     10088112.27      2998339.06     10088936.91
      2998975.29     10089157.64
#Sta/Elev= 30
  3973.7 1021.33  4134.8 1007.64  4215.4  996.45  4273.7   992.9  4300.7  987.82
  4413.2  979.33  4548.2  963.78  4683.6  954.51  4901.1  941.04  4931.3  938.03
  4952.4  927.21  4971.5  921.55  4999.4  920.04  5000.7  920.04  5003.4  919.54
  5006.7  920.04  5082.1  926.63  5118.3  931.36  5343.5  940.26    5356  940.77
  5458.1  943.43  5502.6  947.69  5587.3  966.13  5634.9  971.12  5699.8   976.4
  5736.2  976.57  5769.4  981.04  5899.3  988.98  6068.1 1001.16  6155.5 1009.98
#Mann= 14 ,-1 , 0
  3973.7      .1       0  4413.2     .16       0  4683.6      .1       0
  4901.1     .05       0  4971.5      .1       0  4999.4     .05       0
  5000.7    .035       0  5006.7     .05       0  5343.5      .1       0
    5356     .05       0  5458.1     .16       0  5634.9      .1       0
  5769.4     .16       0  5899.3     .05       0
Bank Sta=4952.4,5082.1
XS Rating Curve= 0 ,0
Exp/Cntr=0.3,0.1

Type RM Length L Ch R = 1 ,15178   ,398,398,398
BEGIN DESCRIPTION:
HAMILTON CREEK 34.0
END DESCRIPTION:
XS GIS Cut Line= 4
      2997226.71     10088600.33      2997554.82     10088808.66
      2997815.24     10089240.95      2998340.15     10089318.91
#Sta/Elev= 30
    4419  985.03  4485.1  981.15  4522.6  977.01  4567.2  974.43  4610.6  966.89
  4672.6  961.83  4718.8  952.72  4806.9  942.33  4843.3  930.66    4886  924.22
  4965.6  920.84  4981.2  919.16  4999.5  914.71  5002.3  914.21  5005.5  914.71
  5039.7  918.58  5070.4  923.79  5091.8  926.48  5155.9  927.49  5303.5  934.16
  5490.2  936.25    5538   938.2  5566.4  941.24  5571.5  943.19  5618.9  946.56
  5669.4  960.03  5699.8  962.51  5747.5  969.72  5769.6  972.72    5843  976.66
#Mann= 9 ,-1 , 0
    4419      .1       0  4485.1     .16       0  4522.6      .1       0
  4672.6     .16       0  4999.5     .07       0  5005.5     .16       0
  5039.7     .05       0  5490.2     .16       0  5747.5      .1       0
Bank Sta=4886,5070.4
XS Rating Curve= 0 ,0
Exp/Cntr=0.3,0.1

Type RM Length L Ch R = 1 ,14780   ,518,518,518
BEGIN DESCRIPTION:
HAMILTON CREEK 33.0
END DESCRIPTION:
XS GIS Cut Line= 3
      2997007.92     10088777.37      2997528.78      10089459.7
      2997757.95     10089886.79
#Sta/Elev= 30
  4484.7  988.47  4654.3   980.7  4718.7  971.61  4774.9  968.76  4818.5  958.25
  4895.5  947.97  4918.2  939.27 4949.09  920.78  4959.9  916.77  5000.5   910.4
  5003.2   909.9  5006.5   910.4  5038.8  916.13  5074.2  919.98  5096.6   922.3
  5278.1  927.86  5310.4  928.45  5338.1  926.51  5342.5  924.22  5348.1  924.22
  5369.4  928.63  5457.1  929.24  5574.7   947.3  5627.3  949.87  5670.7  956.08
  5708.9  964.89  5744.9  966.63  5785.2  970.93  5802.2  975.53  5827.8  977.64
#Mann= 7 ,-1 , 0
  4484.7     .16       0  5000.5     .07       0  5006.5     .16       0
  5096.6     .05       0  5278.1     .16       0  5627.3     .05       0
  5785.2     .16       0
#XS Ineff= 2 , 0
                         5302.73          928.79
Permanent Ineff=
       T       T
Bank Sta=4949.09,5074.2
XS Rating Curve= 0 ,0
Exp/Cntr=0.3,0.1

Type RM Length L Ch R = 1 ,14262   ,433,433,433
BEGIN DESCRIPTION:
HAMILTON CREEK 32.0
END DESCRIPTION:
XS GIS Cut Line= 4
      2996471.48     10089105.53      2996820.44      10089459.7
      2997257.94     10089777.41      2997543.77     10090068.42
#Sta/Elev= 30
  4294.6  982.74  4333.7  981.91  4383.1  974.82  4510.4  969.36  4545.7  960.66
  4602.3  951.71  4680.1  932.22  4722.6  925.46    4905     917    4950  914.73
  4987.1  905.63    4997  904.78  4999.8  904.28    5003  904.78  5023.3  908.21
  5050.3  911.83  5100.5   912.5  5129.9  914.82  5245.1  919.78  5286.8  926.03
  5380.5  933.78  5443.4  939.65  5485.8   948.6  5528.2   949.9  5567.5  955.76
    5599  960.51  5620.2  966.13  5662.7  969.48  5705.1  977.57  5740.4   980.1
#Mann= 7 ,-1 , 0
  4294.6     .16       0    4905      .1       0    4997     .07       0
    5003      .1       0  5023.3     .16       0  5380.5      .1       0
  5567.5     .05       0
Bank Sta=4950,5129.9
XS Rating Curve= 0 ,0
Exp/Cntr=0.3,0.1

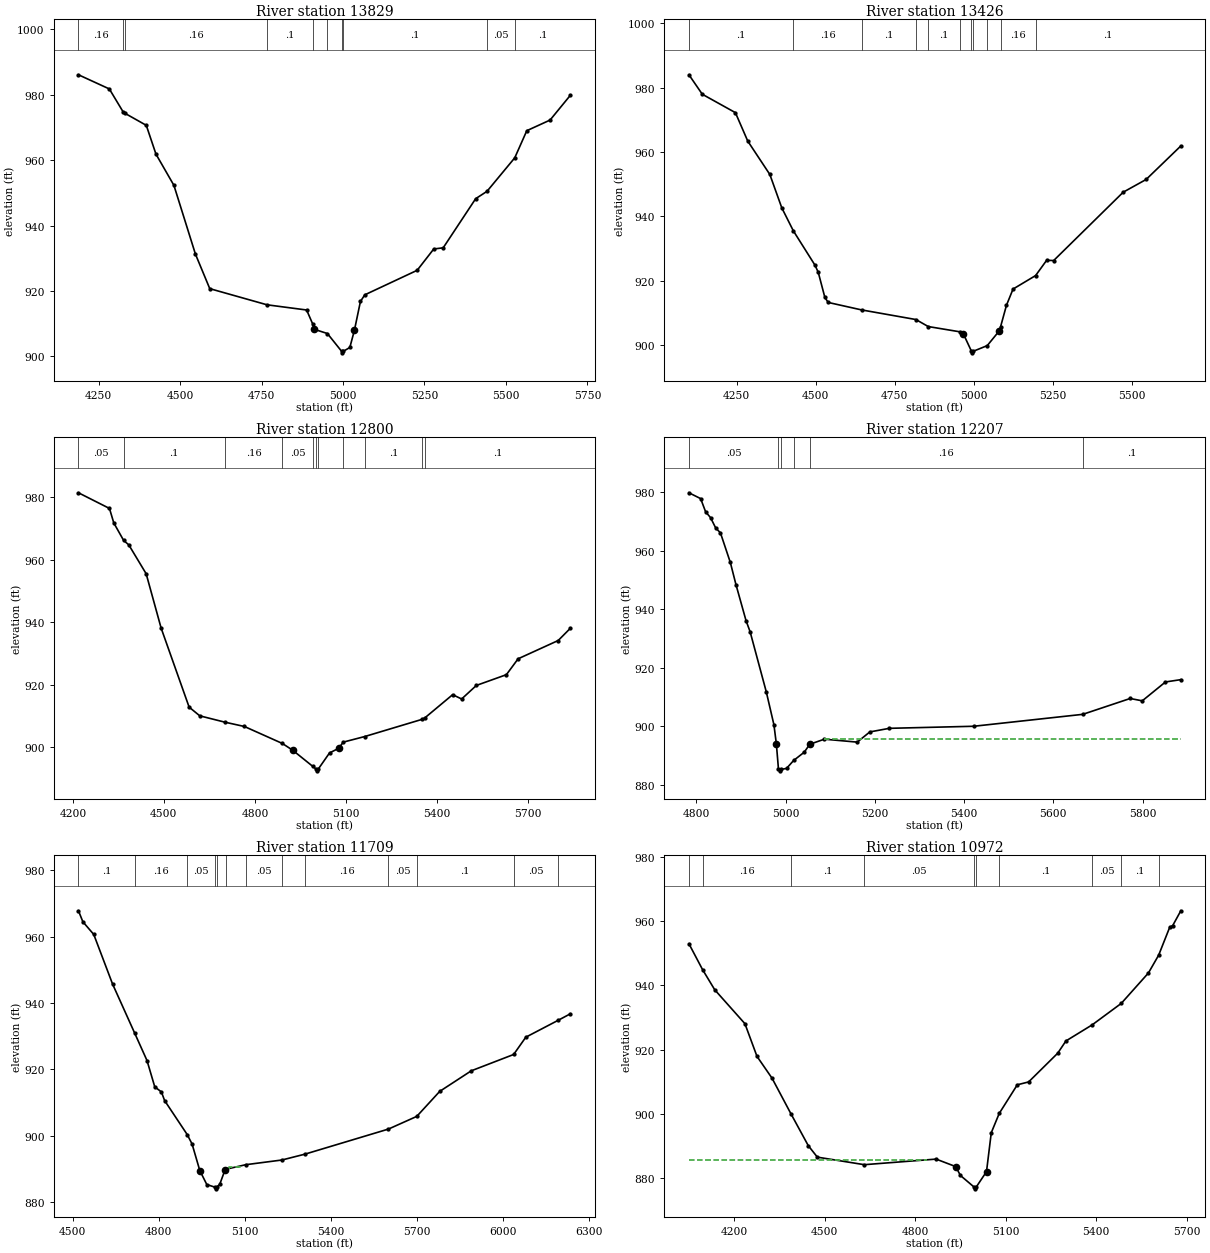
Type RM Length L Ch R = 1 ,13829   ,403,403,403
BEGIN DESCRIPTION:
HAMILTON CREEK 31.0
END DESCRIPTION:
XS GIS Cut Line= 3
      2996367.32     10089157.61      2996820.44     10090141.99
      2997080.14      10090479.6
#Sta/Elev= 30
    4188  986.12  4282.8  981.79  4326.2  974.59  4330.6  974.34  4396.2  970.66
  4425.9  961.85    4481   952.3    4547  931.28    4591  920.71  4766.8  915.77
  4888.3  914.18  4906.4  910.02 4912.27  908.26    4952  906.99  4995.4  901.58
  4998.1  901.08  5001.4  901.58  5020.9  902.72    5035  908.01  5053.4  916.79
  5066.8  918.82  5227.5  926.32  5278.4  932.84  5307.4   933.2  5407.1  948.23
  5441.8  950.47    5527  960.72    5564  969.02  5635.4  972.27  5697.6  979.84
#Mann= 10 ,-1 , 0
    4188     .16       0  4326.2      .1       0  4330.6     .16       0
  4766.8      .1       0  4906.4     .05       0    4952      .1       0
  4995.4     .07       0  5001.4      .1       0  5441.8     .05       0
    5527      .1       0
Bank Sta=4912.27,5035
XS Rating Curve= 0 ,0
Exp/Cntr=0.3,0.1

Type RM Length L Ch R = 1 ,13426   ,626,626,626
BEGIN DESCRIPTION:
HAMILTON CREEK 30.0
END DESCRIPTION:
XS GIS Cut Line= 3
      2995976.69     10089303.43      2996132.94     10089798.24
       2996767.4     10090619.91
#Sta/Elev= 30
  4099.1  983.96  4141.4  977.91  4246.2  972.19  4285.3  963.35  4355.2  952.98
    4393  942.61  4429.6  935.46  4497.9  924.82  4508.4  922.59  4529.4  914.76
  4539.9  913.21  4645.6  910.89  4817.5   907.9  4856.6  905.72    4957  904.08
  4967.4  903.52  4993.4  898.05  4996.2  897.55  4999.4  898.05  5043.3  899.79
  5081.5  904.38  5085.4   905.6  5104.2  912.33    5125  917.37  5196.4  921.56
  5231.4  926.31  5253.6  926.23  5473.7  947.47  5546.2  951.42  5656.1  961.84
#Mann= 11 ,-1 , 0
  4099.1      .1       0  4429.6     .16       0  4645.6      .1       0
  4817.5     .05       0  4856.6      .1       0    4957     .05       0
  4993.4    .035       0  4999.4     .05       0  5043.3      .1       0
  5085.4     .16       0  5196.4      .1       0
Bank Sta=4967.4,5081.5
XS Rating Curve= 0 ,0
Exp/Cntr=0.3,0.1

Type RM Length L Ch R = 1 ,12800   ,593,593,593
BEGIN DESCRIPTION:
HAMILTON CREEK 29.0
END DESCRIPTION:
XS GIS Cut Line= 4
      2995315.23     10089662.82       2995731.9     10090016.99
       2995794.4      10090397.2      2996434.23     10090652.09
#Sta/Elev= 30
  4218.5  981.37  4320.7  976.36    4335  971.71  4367.4  966.13  4384.4   964.7
  4441.6  955.47    4491  938.06  4583.2  912.79  4618.3     910  4700.3  907.99
  4765.4  906.59  4890.2  901.17  4924.2  899.02  4990.5  893.84  5002.3   892.9
    5005   892.4  5008.3   892.9  5045.8  898.12  5076.2  899.62  5090.9  901.58
    5162  903.38    5352  908.91  5360.4  909.38  5451.6  916.77  5481.2  915.39
  5529.8  919.73  5628.7  923.17  5667.3  928.25  5799.4   934.1  5839.4  938.01
#Mann= 11 ,-1 , 0
  4218.5     .05       0  4367.4      .1       0  4700.3     .16       0
  4890.2     .05       0  4990.5      .1       0  5002.3     .07       0
  5008.3      .1       0  5090.9     .16       0    5162      .1       0
    5352     .16       0  5360.4      .1       0
Bank Sta=4924.2,5076.2
XS Rating Curve= 0 ,0
Exp/Cntr=0.3,0.1

Type RM Length L Ch R = 1 ,12207   ,498,498,498
BEGIN DESCRIPTION:
HAMILTON CREEK 27.0
END DESCRIPTION:
XS GIS Cut Line= 3
      2995054.82     10090214.91      2995435.03      10090397.2
      2996013.18     10090756.59
#Sta/Elev= 30
  4783.4  979.72  4809.6  977.73  4820.8  973.22  4831.8  971.25  4843.5  967.67
    4854  966.05  4876.2  955.93  4888.8  948.38  4911.4  936.07  4920.5   932.3
  4956.7  911.82  4973.9  900.54  4979.4  893.93  4984.1  885.33  4986.8  884.83
  4990.1  885.33  5002.1  885.65    5018  888.36  5041.8  891.19  5054.3  893.91
  5086.9  895.63  5160.6  894.63  5188.8  898.11  5232.7  899.34  5421.6  900.04
    5666  904.11  5772.3  909.52  5799.4  908.72  5851.4  915.16  5885.8  915.95
#Mann= 6 ,-1 , 0
  4783.4     .05       0  4984.1    .035       0  4990.1     .05       0
    5018      .1       0  5054.3     .16       0    5666      .1       0
#XS Ineff= 2 , 0
                         5087.15          895.63
Permanent Ineff=
       T       T
Bank Sta=4979.4,5054.3
XS Rating Curve= 0 ,0
Exp/Cntr=0.3,0.1

Type RM Length L Ch R = 1 ,11709   ,737,737,737
BEGIN DESCRIPTION:
HAMILTON CREEK 26.0
END DESCRIPTION:
XS GIS Cut Line= 4
      2994898.57     10090475.32      2994976.69     10090730.53
      2995382.94     10090860.74      2996403.62     10090876.36
#Sta/Elev= 30
  4519.9  967.77  4535.3  964.46  4573.3  960.63  4638.8  945.69  4716.3  930.81
  4758.8  922.63  4785.9  914.69    4809  913.16  4820.2  910.56  4898.8  900.33
  4915.9  897.47  4942.8  889.47  4967.2  885.25  4995.7  884.45  4998.4  883.95
  5001.7  884.45  5012.3   885.3  5030.2  889.54    5033  889.84  5103.3  891.23
    5229  892.64    5309   894.4  5600.4  901.97    5699  905.79    5779  913.33
    5889  919.53  6036.6  924.45    6079  929.66  6192.1  934.77  6234.2  936.71
#Mann= 13 ,-1 , 0
  4519.9      .1       0  4716.3     .16       0  4898.8     .05       0
  4995.7    .035       0  5001.7     .05       0    5033      .1       0
  5103.3     .05       0    5229      .1       0    5309     .16       0
  5600.4     .05       0    5699      .1       0  6036.6     .05       0
  6192.1      .1       0
#XS Ineff= 2 ,-1
 5044.36 5086.84  890.54 5103.84 5154.51  891.13
Permanent Ineff=
       T       T
Bank Sta=4942.8,5030.2
XS Rating Curve= 0 ,0
Exp/Cntr=0.3,0.1

Type RM Length L Ch R = 1 ,10972   ,708,708,708
BEGIN DESCRIPTION:
HAMILTON CREEK 24.0
END DESCRIPTION:
XS GIS Cut Line= 3
       2994794.4     10090548.21      2994778.78     10091100.32
      2995314.36     10092036.28
#Sta/Elev= 30
  4049.7  952.98  4094.8  944.94  4135.3  938.64  4235.3  928.09  4275.3  917.91
  4325.3   911.1  4387.7  900.06  4445.4   890.1  4475.4  886.53  4631.1  884.18
  4869.2  885.92    4934  883.59  4949.8  880.82  4995.7  877.16  4998.5  876.66
  5001.7  877.16  5036.2  882.02    5052  894.13  5078.4  900.15  5138.3  909.06
  5175.8  909.95  5272.2  918.89  5299.5  922.71  5386.6  927.73    5483  934.41
    5573  943.88  5606.9  949.42  5643.5   958.1  5653.6  958.66  5680.4  963.25
#Mann= 10 ,-1 , 0
  4049.7      .1       0  4094.8     .16       0  4387.7      .1       0
  4631.1     .05       0  4995.7    .035       0  5001.7     .05       0
  5078.4      .1       0  5386.6     .05       0    5483      .1       0
  5606.9     .05       0
#XS Ineff= 2 , 0
         4837.32  885.78
Permanent Ineff=
       T       T
Bank Sta=4934,5036.2
XS Rating Curve= 0 ,0
Exp/Cntr=0.3,0.1

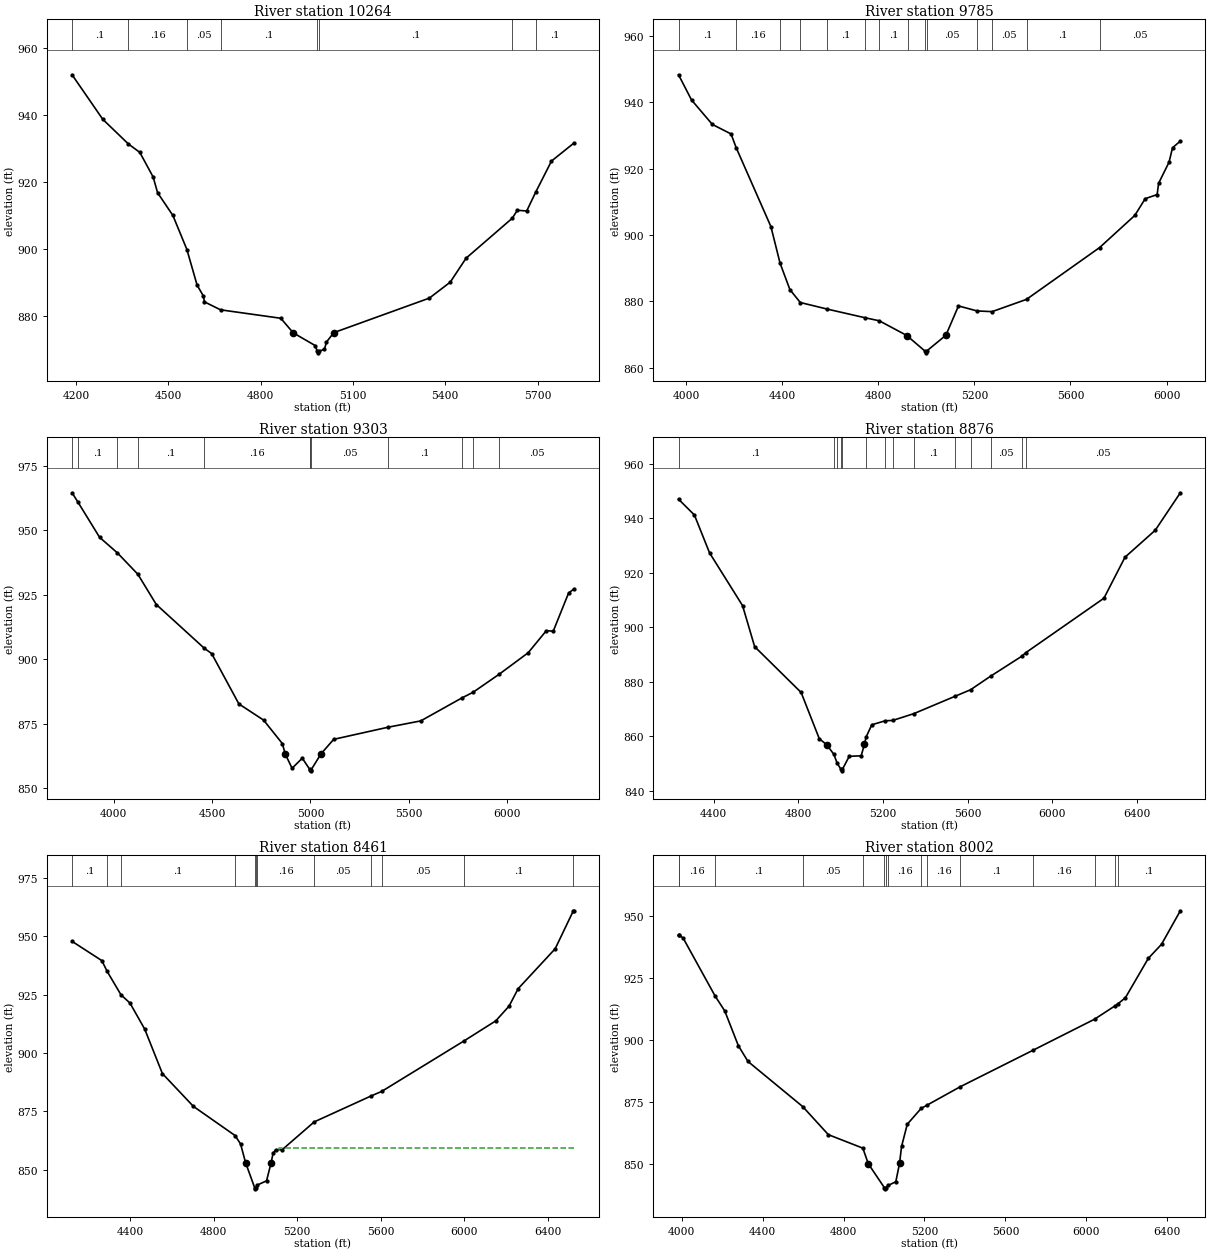
Type RM Length L Ch R = 1 ,10264   ,479,479,479
BEGIN DESCRIPTION:
HAMILTON CREEK 23.0
END DESCRIPTION:
XS GIS Cut Line= 4
      2994695.46     10090480.51      2994429.82     10090819.07
      2994315.24     10091496.16      2994538.95     10091959.19
#Sta/Elev= 30
  4186.7  952.01  4286.6  938.71  4369.9  931.35  4406.9  928.85  4450.3  921.49
  4464.7   916.8  4514.4  910.03    4560  899.85  4593.1  889.24  4613.9  885.92
  4616.8  884.24  4669.4  881.85  4865.2  879.33  4905.7  874.98  4976.7   871.2
  4983.9  869.51  4986.6  869.01  4989.9  869.51  5007.2  870.06  5013.5  872.21
  5037.6  875.04  5348.3  885.35  5416.1  890.11  5467.6  897.26  5617.9   909.2
  5634.2  911.57  5664.7  911.35  5694.1     917  5745.3  926.26    5818  931.61
#Mann= 8 ,-1 , 0
  4186.7      .1       0  4369.9     .16       0    4560     .05       0
  4669.4      .1       0  4983.9     .07       0  4989.9      .1       0
  5617.9     .05       0  5694.1      .1       0
Bank Sta=4905.7,5037.6
XS Rating Curve= 0 ,0
Exp/Cntr=0.3,0.1

Type RM Length L Ch R = 1 ,9785    ,482,482,482
BEGIN DESCRIPTION:
HAMILTON CREEK 22.0
END DESCRIPTION:
XS GIS Cut Line= 4
      2994575.62     10090376.39      2994013.15     10090761.78
       2993856.9     10091266.99      2994403.63     10091954.31
#Sta/Elev= 30
  3968.3  948.24  4022.5  940.64  4109.1  933.28  4186.9  930.42  4208.1   926.3
  4352.8  902.52  4390.9   891.5    4432  883.51  4475.2  879.64  4588.3  877.64
  4744.9  875.05  4804.1  874.13  4919.5  869.67    4923  869.42  4994.6  864.98
  4997.4  864.48  5000.6  864.98  5081.3  869.78  5133.7  878.61  5211.1   877.1
  5273.6  876.89  5416.9  880.59  5721.3   896.2  5867.7  905.87  5910.9  910.91
  5960.6  912.16    5967  915.59  6010.2   921.9  6024.7  926.25  6057.2  928.26
#Mann= 14 ,-1 , 0
  3968.3      .1       0  4208.1     .16       0  4390.9      .1       0
  4475.2     .05       0  4588.3      .1       0  4744.9     .05       0
  4804.1      .1       0    4923     .05       0  4994.6    .035       0
  5000.6     .05       0  5211.1      .1       0  5273.6     .05       0
  5416.9      .1       0  5721.3     .05       0
Bank Sta=4919.5,5081.3
XS Rating Curve= 0 ,0
Exp/Cntr=0.3,0.1

Type RM Length L Ch R = 1 ,9303    ,427,427,427
BEGIN DESCRIPTION:
HAMILTON CREEK 21.0
END DESCRIPTION:
XS GIS Cut Line= 4
      2992513.14      10090339.9      2993330.86     10090641.99
       2993731.9     10091313.87      2994314.35     10091995.12
#Sta/Elev= 30
  3788.3  964.52  3818.3  960.88  3928.2  947.25  4019.1  941.19  4122.7  932.93
  4216.4  921.21  4460.9  904.21  4497.6  902.21  4636.2  882.67  4761.9  876.39
  4857.2  867.29  4871.7  863.27  4906.6  857.72  4958.4  861.64  4995.9  857.34
  4998.2  857.23    5001  856.73  5004.2  857.23  5053.8  863.33    5118  868.94
  5393.9  873.63  5560.7  876.09  5769.3  884.98  5826.7  887.19  5959.4  894.19
  6106.7  902.51  6198.9  911.06    6234  910.87    6312  925.65  6338.8  927.21
#Mann= 12 ,-1 , 0
  3788.3     .05       0  3818.3      .1       0  4019.1     .16       0
  4122.7      .1       0  4460.9     .16       0  4995.9     .05       0
  4998.2    .035       0  5004.2     .05       0  5393.9      .1       0
  5769.3     .05       0  5826.7      .1       0  5959.4     .05       0
Bank Sta=4871.7,5053.8
XS Rating Curve= 0 ,0
Exp/Cntr=0.3,0.1

Type RM Length L Ch R = 1 ,8876    ,415,415,415
BEGIN DESCRIPTION:
HAMILTON CREEK 20.0
END DESCRIPTION:
XS GIS Cut Line= 3
      2992612.07     10090683.62      2993497.53     10091438.87
      2994450.65     10092178.44
#Sta/Elev= 30
  4234.7     947  4309.8  941.19  4381.2   927.3  4537.1  907.94  4594.2  892.88
  4813.8  876.06  4899.4  859.11  4934.6  856.86  4968.4  853.36    4984  850.08
  5002.4  847.79  5005.2  847.29  5008.4  847.79  5041.1  852.63  5097.4   852.8
 5113.07  857.12  5120.8  859.72  5147.6   864.2  5211.4  865.67    5246  865.79
  5345.3  868.26  5538.7  874.59    5614  877.05  5708.3  882.01  5855.8  889.35
  5873.8   890.6    6244  910.65  6343.5   925.7  6486.5  935.61  6604.9  949.36
#Mann= 14 ,-1 , 0
  4234.7      .1       0  4968.4     .05       0    4984      .1       0
  5002.4     .07       0  5008.4      .1       0  5120.8     .05       0
  5211.4      .1       0    5246     .05       0  5345.3      .1       0
  5538.7     .05       0    5614      .1       0  5708.3     .05       0
  5855.8      .1       0  5873.8     .05       0
Bank Sta=4934.6,5113.07
XS Rating Curve= 0 ,0
Exp/Cntr=0.3,0.1

Type RM Length L Ch R = 1 ,8461    ,459,459,459
BEGIN DESCRIPTION:
HAMILTON CREEK 19.0
END DESCRIPTION:
XS GIS Cut Line= 4
      2992414.23     10091006.61      2992846.49     10091475.32
      2993617.32     10091787.82      2994341.29     10092376.38
#Sta/Elev= 30
  4121.8  947.87  4264.5   939.6  4289.2  935.08  4356.3   924.9  4398.8  921.44
  4469.7  910.22  4554.2  891.18  4702.8   877.1  4902.1  864.61  4928.5     861
  4952.6  852.96  4995.9  842.25  4998.7  841.75  5001.9  842.25  5006.8  843.31
  5052.9  845.18  5074.5  852.86  5083.9  856.91    5096  858.48  5128.4  858.58
  5281.2  870.46  5552.8  881.55  5604.6  883.55  6000.6   905.3  6150.4  913.78
  6214.3  920.14  6257.4  927.57  6434.8   944.7  6521.8  960.98  6524.2  960.98
#Mann= 12 ,-1 , 0
  4121.8      .1       0  4289.2     .16       0  4356.3      .1       0
  4902.1     .05       0  4995.9    .035       0  5001.9     .05       0
  5006.8     .16       0  5281.2     .05       0  5552.8      .1       0
  5604.6     .05       0  6000.6      .1       0  6521.8     .16       0
#XS Ineff= 2 , 0
                         5113.36          859.28
Permanent Ineff=
       T       T
Bank Sta=4952.6,5074.5
XS Rating Curve= 0 ,0
Exp/Cntr=0.3,0.1

Type RM Length L Ch R = 1 ,8002    ,626,626,626
BEGIN DESCRIPTION:
HAMILTON CREEK 18.0
END DESCRIPTION:
XS GIS Cut Line= 4
       2992351.7     10091162.84      2992627.74     10091829.49
      2993554.82     10092324.28      2994242.31     10092490.95
#Sta/Elev= 30
  3984.6  942.23  3986.7  942.23  4007.2  941.09  4165.8  917.67  4212.9  911.76
    4280  897.78  4327.8  891.39  4598.5  873.21  4724.9  861.93  4895.4   856.5
  4922.5   850.2  5001.6  840.62  5004.4  840.12  5007.6  840.62  5021.1  841.52
  5058.4  842.98  5076.7  850.36  5086.8  857.18    5115  866.13  5183.5  872.49
  5212.1  873.78  5376.1  881.19  5737.5  895.95  6040.6  908.41  6142.6  913.83
    6155  914.53  6192.9  917.03  6306.1  932.89  6371.5  938.56  6464.4  952.05
#Mann= 15 ,-1 , 0
  3984.6      .1       0  3986.7     .16       0  4165.8      .1       0
  4598.5     .05       0  4895.4      .1       0  5001.6     .07       0
  5007.6      .1       0  5021.1     .16       0  5183.5     .05       0
  5212.1     .16       0  5376.1      .1       0  5737.5     .16       0
  6040.6      .1       0  6142.6     .05       0    6155      .1       0
Bank Sta=4922.5,5076.7
XS Rating Curve= 0 ,0
Exp/Cntr=0.3,0.1