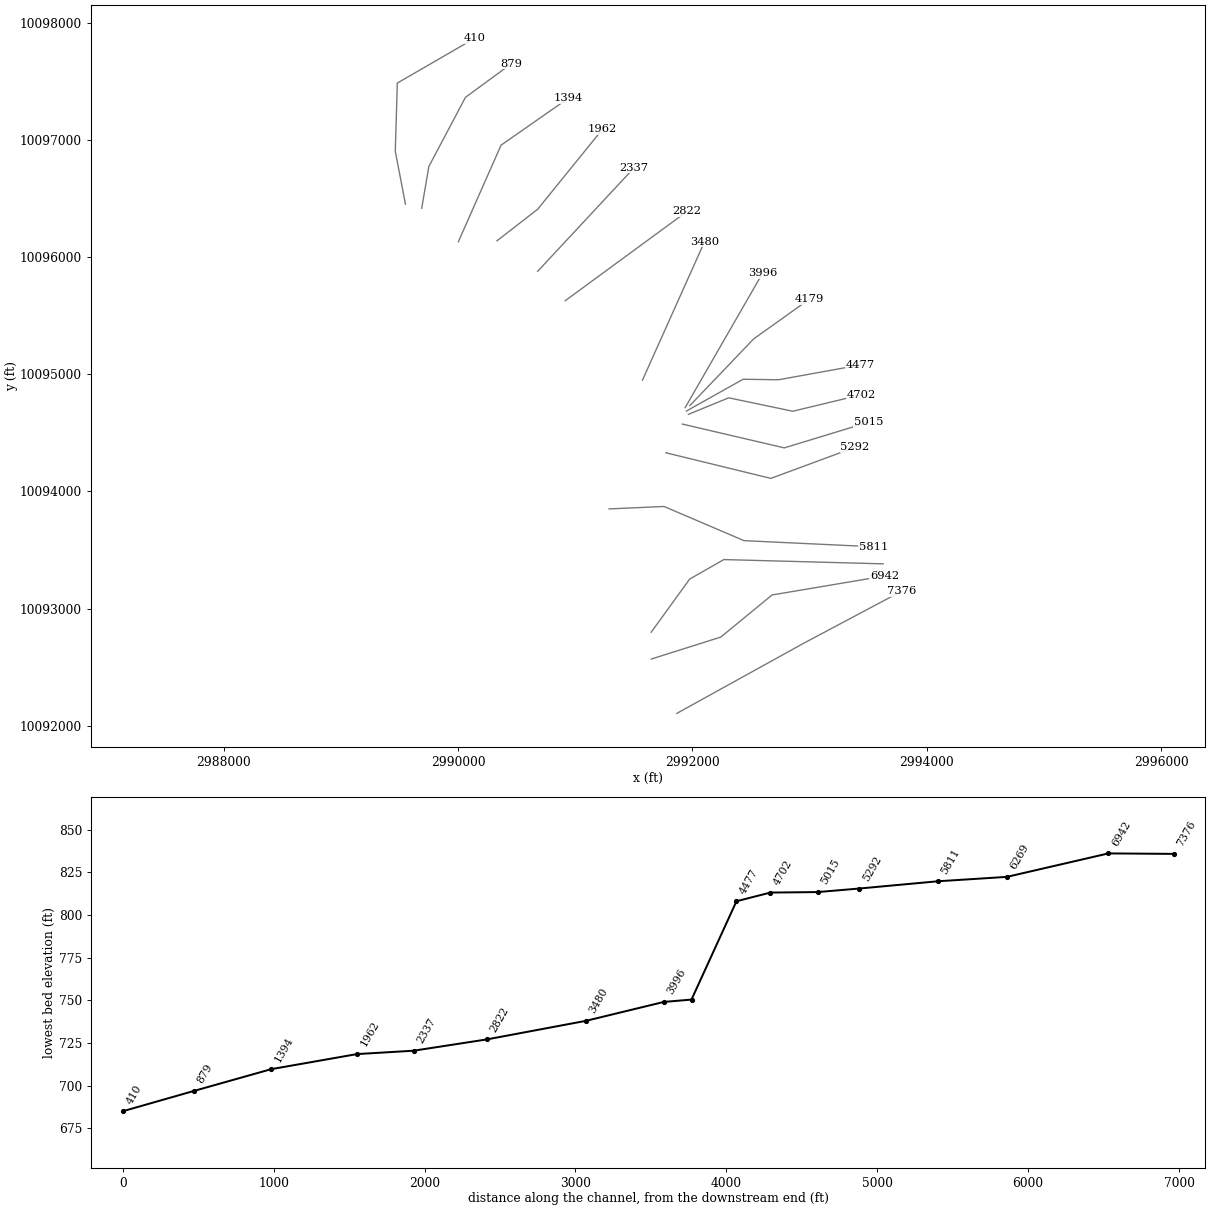
HEC-RAS study HAMILTON CREEK.prj: HAMILTON CREEK Base Level Engineering

--- HAMILTON CREEK.g01 (geometry) --- (continued)

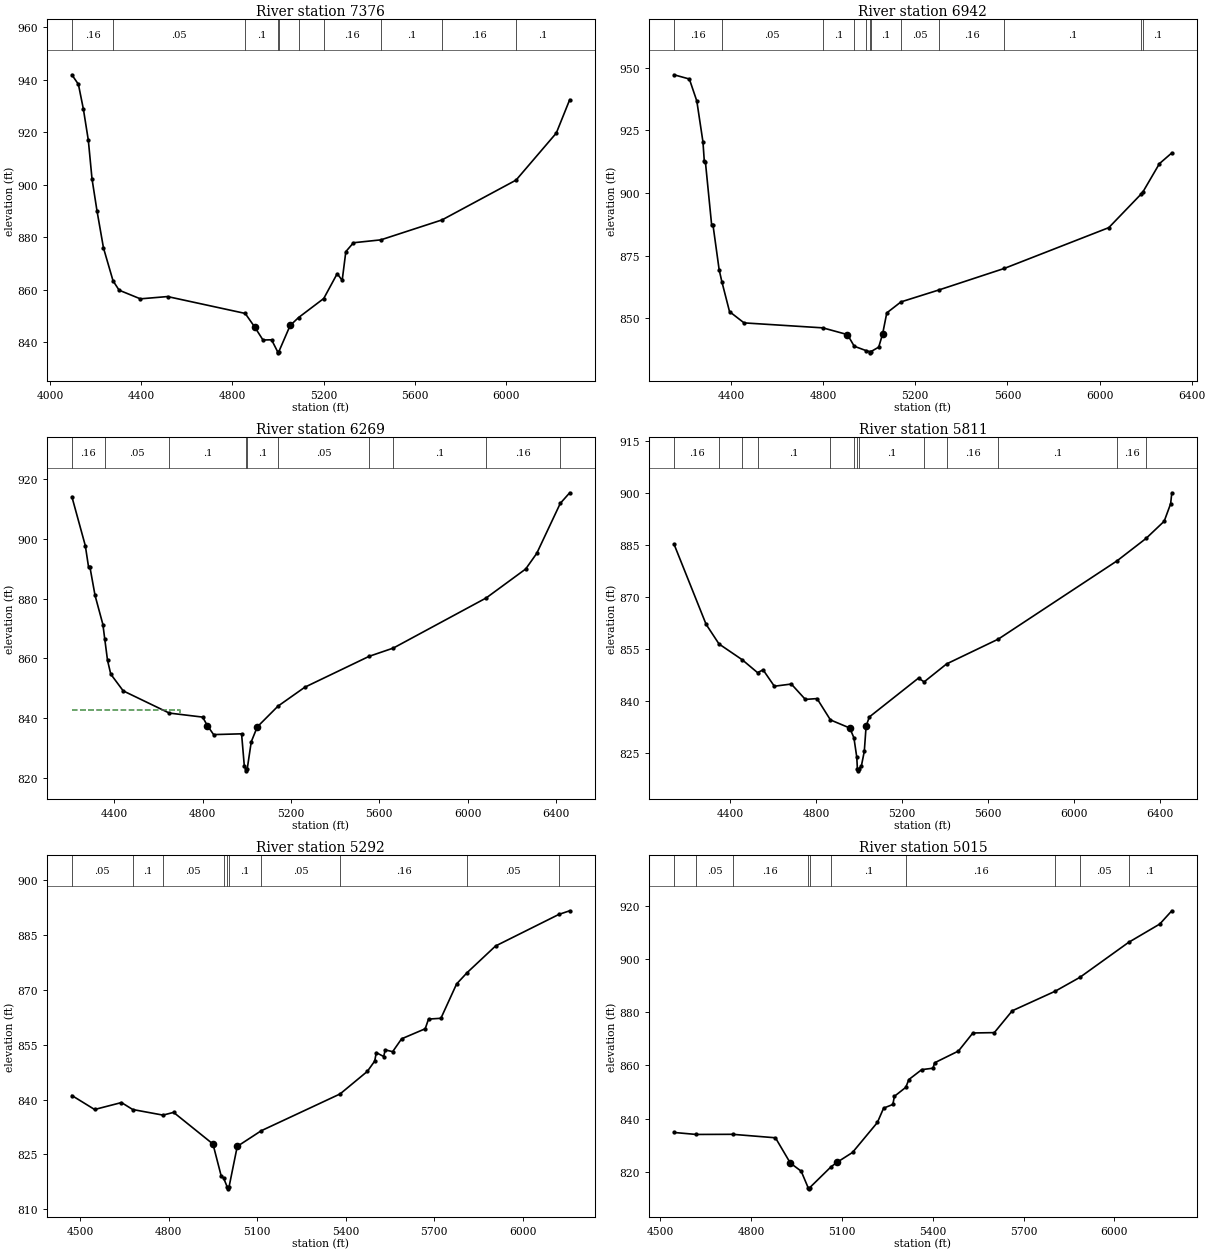
Type RM Length L Ch R = 1 ,7376    ,434,434,434
BEGIN DESCRIPTION:
HAMILTON CREEK 16.0
END DESCRIPTION:
XS GIS Cut Line= 3
      2991867.28     10092105.51      2992950.65     10092704.49
      2993783.76     10093147.08
#Sta/Elev= 30
  4096.2  941.87  4124.8  938.24  4146.6  928.81  4168.3  916.93  4184.4  902.24
  4206.1   890.1  4234.7  875.87  4276.7  863.31  4303.2  859.77  4396.3  856.47
  4515.4  857.34  4855.7  850.91  4897.4  845.72  4933.5  840.79  4971.3  840.85
  4997.3  836.39    5000  835.89  5003.3  836.39  5052.6  846.32  5089.6  849.35
  5199.8   856.6  5258.8  866.07  5280.6  863.51  5296.6  874.47    5330  877.85
  5449.9  878.95  5718.3  886.56  6042.5  901.73  6218.8  919.66  6277.5  932.37
#Mann= 10 ,-1 , 0
  4096.2     .16       0  4276.7     .05       0  4855.7      .1       0
  4997.3     .07       0  5003.3      .1       0  5089.6     .05       0
  5199.8     .16       0  5449.9      .1       0  5718.3     .16       0
  6042.5      .1       0
Bank Sta=4897.4,5052.6
XS Rating Curve= 0 ,0
Exp/Cntr=0.3,0.1

Type RM Length L Ch R = 1 ,6942    ,673,673,673
BEGIN DESCRIPTION:
HAMILTON CREEK 15.0
END DESCRIPTION:
XS GIS Cut Line= 4
      2991648.52     10092569.06      2992242.32     10092756.57
      2992679.82     10093115.95      2993638.14      10093277.4
#Sta/Elev= 30
  4152.9  947.17  4219.6  945.48    4252  936.69  4278.7  920.34  4284.3  912.87
  4289.5  912.18  4316.6  887.01  4321.9  887.39    4349  869.31  4360.6  864.61
    4394  852.62    4457  848.13  4799.1  846.14  4905.8  843.45  4935.2  838.81
  4985.4   837.1  5001.8  836.67  5004.5  836.17  5007.8  836.67  5041.4  838.45
 5058.24  843.65  5076.5  852.11    5138   856.5  5303.7   861.3  5586.3  869.86
  6040.1  886.15  6178.7  899.39  6188.1   900.4  6259.8  911.69  6313.6  915.98
#Mann= 12 ,-1 , 0
  4152.9     .16       0  4360.6     .05       0  4799.1      .1       0
  4935.2     .16       0  4985.4      .1       0  5001.8     .07       0
  5007.8      .1       0    5138     .05       0  5303.7     .16       0
  5586.3      .1       0  6178.7     .16       0  6188.1      .1       0
#XS Ineff= 2 ,-1
 4548.42 4580.37  846.93 4583.12 4645.28  846.79
Permanent Ineff=
       T       T
Bank Sta=4905.8,5058.24
XS Rating Curve= 0 ,0
Exp/Cntr=0.3,0.1

Type RM Length L Ch R = 1 ,6269    ,458,458,458
BEGIN DESCRIPTION:
HAMILTON CREEK 14.0
END DESCRIPTION:
XS GIS Cut Line= 4
      2991648.56     10092798.22      2991976.69     10093251.37
      2992268.36     10093418.03      2993627.77     10093381.57
#Sta/Elev= 30
  4207.6  914.09  4268.5   897.7  4283.2  890.56  4289.4  890.55  4312.6  881.06
  4348.2  871.33  4356.3  866.62  4369.1  859.36  4383.8  854.74  4440.2  849.14
  4648.8  841.72    4800  840.37  4821.6  837.51  4849.7  834.52  4976.4  834.78
  4988.6  824.18  4995.7   822.9  4998.4   822.4  5001.7   822.9  5020.3  832.13
  5047.6   837.1  5141.4  844.04  5263.2  850.38  5554.4   860.7  5663.9  863.46
  6084.6  880.22  6263.5   889.9  6313.5  895.12  6420.3  911.86  6462.9  915.39
#Mann= 10 ,-1 , 0
  4207.6     .16       0  4356.3     .05       0  4648.8      .1       0
  4995.7     .07       0  5001.7      .1       0  5141.4     .05       0
  5554.4     .16       0  5663.9      .1       0  6084.6     .16       0
  6420.3      .1       0
#XS Ineff= 2 , 0
         4696.02  842.78
Permanent Ineff=
       T       T
Bank Sta=4821.6,5047.6
XS Rating Curve= 0 ,0
Exp/Cntr=0.3,0.1

Type RM Length L Ch R = 1 ,5811    ,519,519,519
BEGIN DESCRIPTION:
HAMILTON CREEK 13.0
END DESCRIPTION:
XS GIS Cut Line= 4
      2991289.23     10093850.32      2991757.94     10093871.16
      2992440.24     10093579.49      2993543.91     10093527.43
#Sta/Elev= 30
  4139.6  885.16    4289  862.04  4349.2  856.37  4456.6  851.85  4528.3  848.12
  4554.2  848.92  4606.5   844.2  4685.5  844.83  4750.7   840.4  4805.1  840.64
  4867.5  834.49  4957.4  832.16  4976.8  829.32    4990  823.75    4993  820.32
  4995.7  819.82    4999  820.32  5011.7  821.31    5025  825.43  5033.5  832.73
  5048.6  835.35  5277.3  846.55  5303.3  845.45    5408  850.63  5648.6  857.78
  6200.5  880.31  6335.9  886.79  6420.2  891.74  6450.2  896.78  6455.7  899.94
#Mann= 13 ,-1 , 0
  4139.6     .16       0  4349.2      .1       0  4456.6     .05       0
  4528.3      .1       0  4867.5     .05       0  4976.8      .1       0
    4993     .07       0    4999      .1       0  5303.3     .05       0
    5408     .16       0  5648.6      .1       0  6200.5     .16       0
  6335.9      .1       0
Bank Sta=4957.4,5033.5
XS Rating Curve= 0 ,0
Exp/Cntr=0.3,0.1

Type RM Length L Ch R = 1 ,5292    ,277,277,277
BEGIN DESCRIPTION:
HAMILTON CREEK 12.0
END DESCRIPTION:
XS GIS Cut Line= 3
       2991773.6     10094329.48       2992669.4     10094110.74
      2993388.16     10094376.37
#Sta/Elev= 30
  4471.6  841.13  4548.7   837.3  4639.8   839.2  4678.1  837.29  4780.7  835.76
  4816.7  836.51  4950.1  827.85  4978.2  819.05    4986  818.56  4998.6  816.08
  5001.3  815.58  5004.6  816.08  5032.5   827.2  5113.8  831.48  5381.3  841.56
  5473.6  847.73  5498.7  850.56    5504  852.88  5529.1   851.8  5534.4  853.62
  5559.5  853.13  5589.9  856.65  5669.9   859.4  5681.2  862.05  5723.2  862.27
  5776.5  871.68  5811.9  874.75  5908.5  882.06  6123.4  890.71    6160   891.7
#Mann= 10 ,-1 , 0
  4471.6     .05       0  4678.1      .1       0  4780.7     .05       0
    4986      .1       0  4998.6     .07       0  5004.6      .1       0
  5113.8     .05       0  5381.3     .16       0  5811.9     .05       0
  6123.4      .1       0
Bank Sta=4950.1,5032.5
XS Rating Curve= 0 ,0
Exp/Cntr=0.3,0.1

Type RM Length L Ch R = 1 ,5015    ,313,313,313
BEGIN DESCRIPTION:
HAMILTON CREEK 11.0
END DESCRIPTION:
XS GIS Cut Line= 3
      2991914.21     10094574.28      2992783.99     10094371.16
      2993502.76     10094589.91
#Sta/Elev= 30
  4545.2  834.74  4618.4  833.99    4739  834.04  4880.4  832.73  4929.5  823.22
  4965.4  820.14  4988.1  813.99  4990.9  813.49  4994.1  813.99  5064.2  821.82
  5083.6  823.46  5134.9   827.2  5217.1   838.5  5237.6   843.9  5268.2   845.3
  5273.3  848.36  5310.9  851.74    5321  854.68  5363.5  858.41  5400.9  858.96
    5406  860.99  5484.9  865.43  5532.5  872.23  5603.4  872.37  5662.6   880.6
  5804.4  887.97  5885.9  893.19    6047  906.39    6150   913.3  6189.7  918.29
#Mann= 10 ,-1 , 0
  4545.2      .1       0  4618.4     .05       0    4739     .16       0
  4988.1     .07       0  4994.1     .16       0  5064.2      .1       0
  5310.9     .16       0  5804.4      .1       0  5885.9     .05       0
    6047      .1       0
Bank Sta=4929.5,5083.6
XS Rating Curve= 0 ,0
Exp/Cntr=0.3,0.1

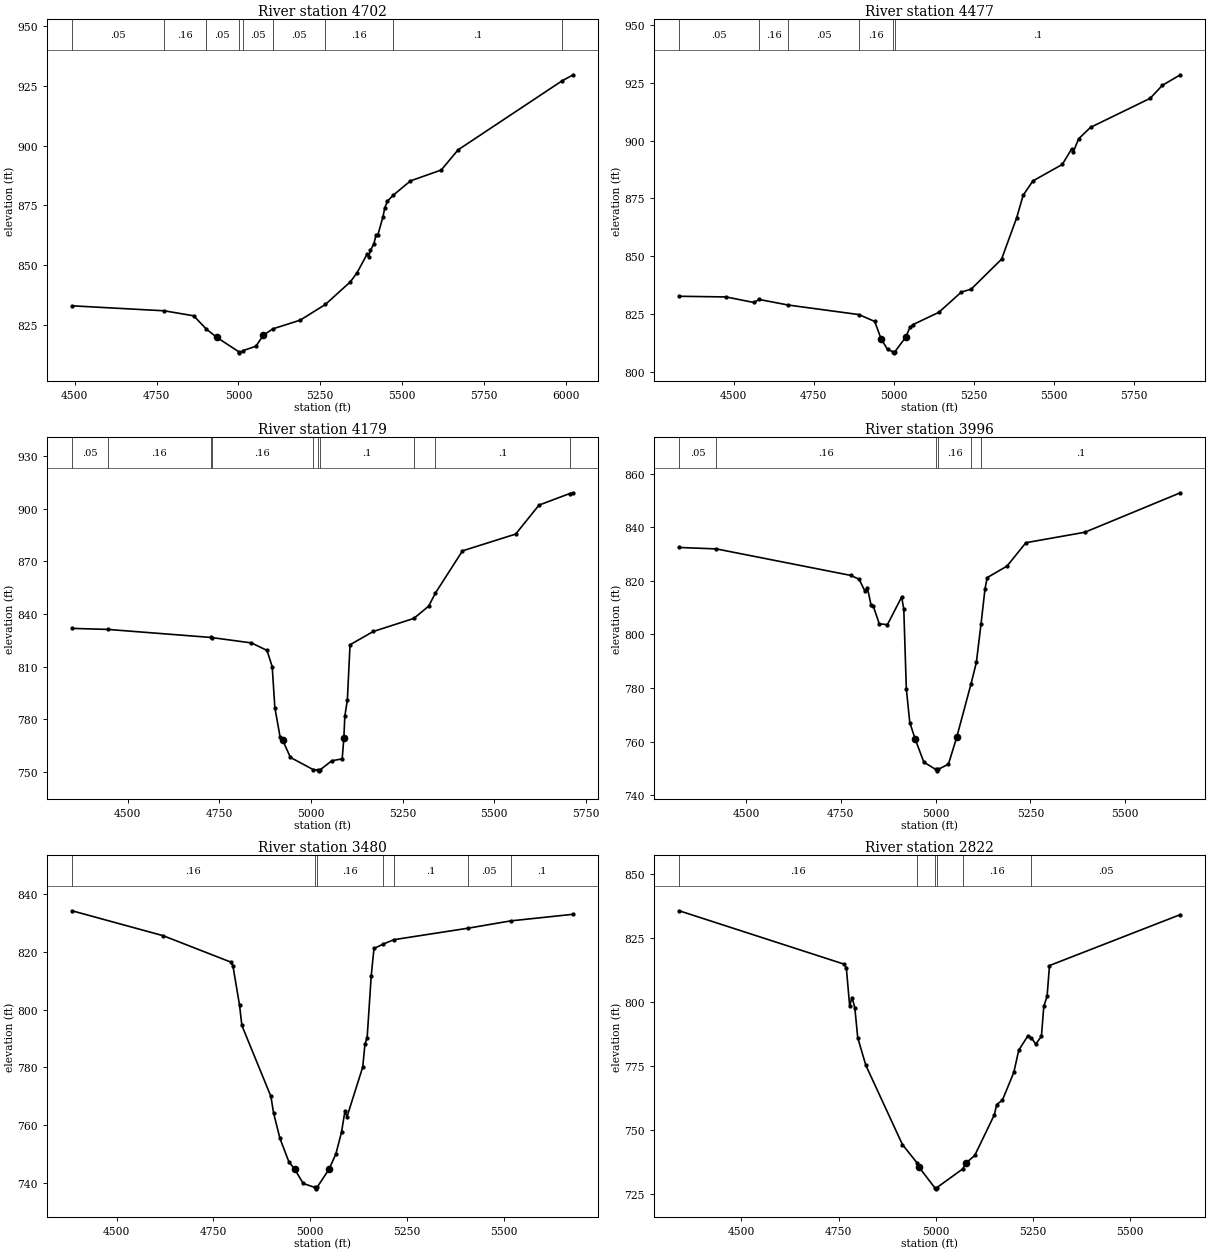
Type RM Length L Ch R = 1 ,4702    ,225,225,225
BEGIN DESCRIPTION:
HAMILTON CREEK 10.0
END DESCRIPTION:
XS GIS Cut Line= 4
      2991966.29     10094657.62      2992310.03     10094798.24
       2992856.9     10094683.66      2993440.25     10094824.29
#Sta/Elev= 30
  4492.1   832.9  4773.5  830.81  4863.5  828.72  4901.6  823.24  4933.4  819.75
  5000.6   813.7  5003.4   813.2  5015.1  814.16  5053.5  815.98  5076.5   820.6
  5105.1  823.24  5188.8  826.89  5265.5  833.45  5342.1  842.97  5362.5  846.78
  5392.8   854.5  5397.9  853.44  5403.4  856.14  5413.6  858.84  5420.5  862.49
  5425.6  862.49  5441.6  870.21  5446.7  873.78  5454.7   876.7  5473.2  879.28
  5525.4  885.23  5619.5   889.8  5670.7  898.21  5987.6  927.08  6022.3  929.68
#Mann= 9 ,-1 , 0
  4492.1     .05       0  4773.5     .16       0  4901.6     .05       0
  5000.6     .07       0  5015.1     .05       0  5105.1     .05       0
  5265.5     .16       0  5473.2      .1       0  5987.6     .05       0
Bank Sta=4933.4,5076.5
XS Rating Curve= 0 ,0
Exp/Cntr=0.3,0.1

Type RM Length L Ch R = 1 ,4477    ,298,298,298
BEGIN DESCRIPTION:
Mapping XS 5e3afcc6
END DESCRIPTION:
XS GIS Cut Line= 4
      2991949.07     10094685.49        2992433.     10094956.75
      2992734.65     10094952.41      2993431.21     10095078.27
#Sta/Elev= 30
  4330.5   832.6  4476.7  832.31  4563.5  829.91  4579.8  831.22  4670.9   828.8
  4891.3  824.68  4940.7  821.71  4960.7  814.15  4980.8  809.58  4997.8  808.62
  5000.5  808.12  5003.8  808.62 5037.61  814.89  5050.8  819.21  5060.8  820.38
  5140.8  825.64  5211.2  834.42  5241.6  835.65  5336.6  848.62  5383.9  866.59
  5404.2  876.34  5434.7  882.53  5526.2  889.64  5555.8  896.43  5560.8   895.1
    5577  900.72  5614.4  905.69  5800.6  918.26  5838.6  923.88  5894.8  928.45
#Mann= 6 ,-1 , 0
  4330.5     .05       0  4579.8     .16       0  4670.9     .05       0
  4891.3     .16       0  4997.8     .07       0  5003.8      .1       0
Bank Sta=4960.7,5037.61
XS Rating Curve= 0 ,0
Exp/Cntr=0.3,0.1

Type RM Length L Ch R = 1 ,4179    ,183,183,183
BEGIN DESCRIPTION:
Mapping XS 6fb98ed7
END DESCRIPTION:
XS GIS Cut Line= 3
        2991978.     10094731.99      2992523.12     10095301.41
      2992994.44     10095637.57
#Sta/Elev= 30
  4348.2  831.76  4445.5  831.18  4726.4   826.6  4729.2  826.52  4837.7  823.47
  4880.1  819.18  4894.3  809.91  4901.5  786.54  4915.7  769.85  4922.6     768
    4944  758.09  5005.7  751.18  5018.7  750.93  5021.4  750.43  5024.7  750.93
  5056.9  756.19  5085.2  757.25  5089.8  769.38  5092.4  781.62  5099.3  790.82
  5106.6  822.42    5170  829.99  5280.7  837.46  5321.2  844.47  5339.6  851.97
  5413.4  876.03  5558.5  885.61  5622.1  902.15  5706.1  908.77  5715.4  909.19
#Mann= 10 ,-1 , 0
  4348.2     .05       0  4445.5     .16       0  4726.4     .05       0
  4729.2     .16       0  5005.7      .1       0  5018.7     .07       0
  5024.7      .1       0  5280.7     .05       0  5339.6      .1       0
  5706.1     .05       0
Bank Sta=4922.6,5089.8
XS Rating Curve= 0 ,0
Exp/Cntr=0.3,0.1

Type RM Length L Ch R = 1 ,3996    ,516,516,516
BEGIN DESCRIPTION:
HAMILTON CREEK 9.0
END DESCRIPTION:
XS GIS Cut Line= 2
       2991938.5     10094714.91      2992597.64     10095859.72
#Sta/Elev= 30
  4324.2  832.43  4422.2  831.89  4776.8  821.99  4798.4  820.55  4814.2  816.01
    4820  817.48    4830  810.89  4835.8  810.55  4851.5  803.93  4873.1  803.63
  4910.5  813.94  4916.2  809.34  4922.9   779.6    4932   767.1  4945.9  761.04
    4969  752.31  5000.6  749.56  5003.4  749.06  5006.6  749.56    5034  751.59
  5055.6  761.55  5093.4  781.51  5107.5  789.52  5119.9  804.01  5130.3  817.05
  5136.1  821.18  5188.3  825.48  5238.1  834.21  5393.3   838.1  5645.2  852.84
#Mann= 6 ,-1 , 0
  4324.2     .05       0  4422.2     .16       0  5000.6     .07       0
  5006.6     .16       0  5093.4     .05       0  5119.9      .1       0
Bank Sta=4945.9,5055.6
XS Rating Curve= 0 ,0
Exp/Cntr=0.3,0.1

Type RM Length L Ch R = 1 ,3480    ,658,658,658
BEGIN DESCRIPTION:
HAMILTON CREEK 8.0
END DESCRIPTION:
XS GIS Cut Line= 2
      2991573.91     10094949.26      2992103.19      10096129.3
#Sta/Elev= 30
    4385  834.18  4620.1  825.56  4794.6  816.43  4800.1  815.21  4817.3  801.47
  4823.3  794.49  4898.3  769.92    4905  764.26  4921.5  755.45  4944.6  747.31
  4959.8   744.7  4981.7  739.82  5011.2  738.47  5013.9  737.97  5017.2  738.47
  5048.3  744.76    5066   750.1  5080.4  757.54  5089.2  764.83  5094.7  762.95
  5135.2  780.13    5141  788.18  5146.5  790.13  5157.1   811.7  5164.2  821.14
  5187.2   822.6  5215.5  824.18  5406.9  828.15  5516.8  830.68  5678.3  832.97
#Mann= 7 ,-1 , 0
    4385     .16       0  5011.2     .07       0  5017.2     .16       0
  5187.2     .05       0  5215.5      .1       0  5406.9     .05       0
  5516.8      .1       0
Bank Sta=4959.8,5048.3
XS Rating Curve= 0 ,0
Exp/Cntr=0.3,0.1

Type RM Length L Ch R = 1 ,2822    ,485,485,485
BEGIN DESCRIPTION:
HAMILTON CREEK 6.0
END DESCRIPTION:
XS GIS Cut Line= 2
      2990914.21     10095626.37      2991953.66     10096388.64
#Sta/Elev= 30
  4339.9  835.63  4763.6  814.81  4769.8  813.26  4778.3  798.56  4784.5  801.74
  4791.6  797.78  4799.1  786.04    4820  775.27  4914.1  744.33  4952.8  736.99
  4955.8   735.7  4996.8  727.56  4999.6  727.06  5002.8  727.56  5069.2  734.84
    5077  737.04  5100.1  740.12  5150.3  755.91  5156.5  759.98  5171.2  761.69
  5200.5  772.52  5213.2  781.18    5236  786.64  5245.7  786.06  5256.8  783.56
  5271.5   786.6  5277.7  798.36  5286.1  802.19  5292.3  814.24  5628.9  834.14
#Mann= 6 ,-1 , 0
  4339.9     .16       0  4952.8     .05       0  4996.8    .035       0
  5002.8     .05       0  5069.2     .16       0  5245.7     .05       0
Bank Sta=4955.8,5077
XS Rating Curve= 0 ,0
Exp/Cntr=0.3,0.1

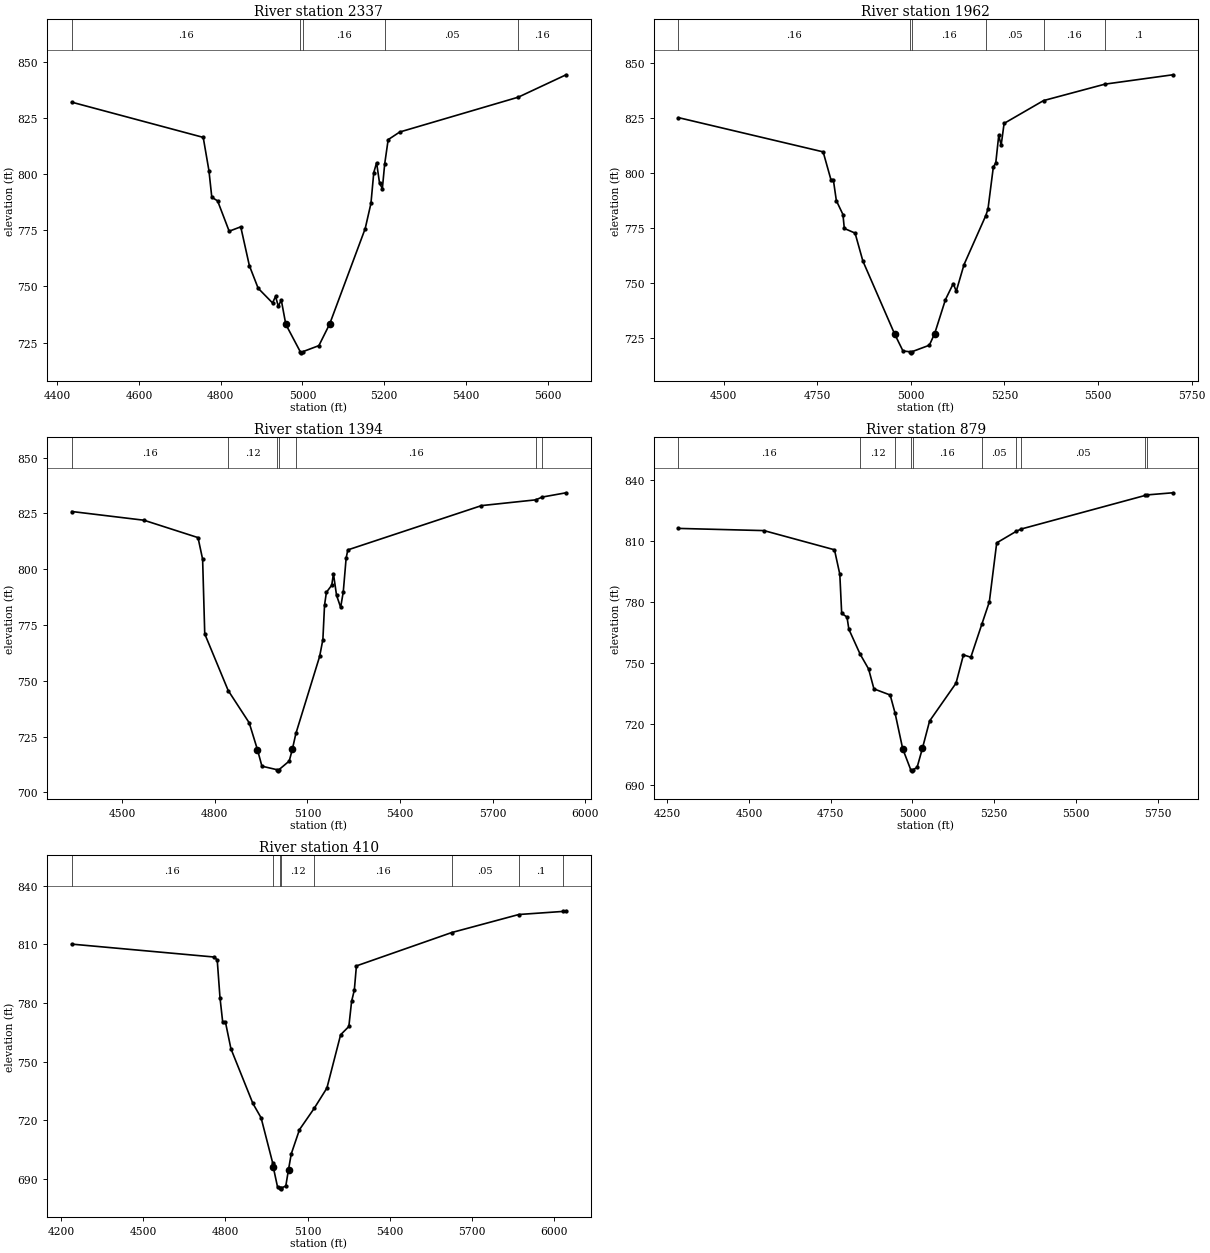
Type RM Length L Ch R = 1 ,2337    ,375,375,375
BEGIN DESCRIPTION:
HAMILTON CREEK 5.0
END DESCRIPTION:
XS GIS Cut Line= 2
      2990679.79     10095878.07      2991503.99       10096763.
#Sta/Elev= 30
  4435.5  832.12  4757.2  816.43  4771.2  801.61  4778.2  789.75  4792.4  788.14
  4820.7  774.63    4849  776.58  4870.1  759.28  4891.6  749.21  4926.7  742.68
  4934.1  745.55  4940.9  741.23  4948.2  743.92  4959.2  733.14  4994.6  720.94
  4997.3  720.44  5000.6  720.94  5040.1  723.65 5066.59  733.32  5153.4  775.79
  5167.5  787.05  5174.4  800.77  5181.3  805.13  5188.6  795.96  5195.4  793.62
  5201.1   804.6  5209.6  815.42  5237.9  818.82  5527.8  834.34  5644.8  844.32
#Mann= 5 ,-1 , 0
  4435.5     .16       0  4994.6     .07       0  5000.6     .16       0
  5201.1     .05       0  5527.8     .16       0
Bank Sta=4959.2,5066.59
XS Rating Curve= 0 ,0
Exp/Cntr=0.3,0.1

Type RM Length L Ch R = 1 ,1962    ,568,568,568
BEGIN DESCRIPTION:
HAMILTON CREEK 4.0
END DESCRIPTION:
XS GIS Cut Line= 3
      2990332.57      10096138.5      2990679.82     10096407.62
      2991234.44     10097092.23
#Sta/Elev= 30
  4379.4  825.09  4765.8  809.57  4786.6  796.96    4793  796.95  4801.1  787.44
  4818.7  781.17  4822.3  774.86  4851.1  772.74  4871.9  760.08  4956.7  727.01
    4979  719.31  4996.8  718.96  4999.5  718.46  5002.8  718.96  5049.4  721.91
  5063.7  727.21  5092.5  742.61  5113.3  749.83  5121.3  746.39  5142.1  758.48
  5200.1  780.65    5206  783.62  5220.4  802.77  5226.8   804.5  5234.8  817.09
  5241.2  812.56  5249.1  822.48  5354.4  832.82  5518.6  840.28  5699.8  844.52
#Mann= 6 ,-1 , 0
  4379.4     .16       0  4996.8     .07       0  5002.8     .16       0
  5200.1     .05       0  5354.4     .16       0  5518.6      .1       0
Bank Sta=4956.7,5063.7
XS Rating Curve= 0 ,0
Exp/Cntr=0.3,0.1

Type RM Length L Ch R = 1 ,1394    ,515,515,515
BEGIN DESCRIPTION:
HAMILTON CREEK 3.0
END DESCRIPTION:
XS GIS Cut Line= 3
      2990002.75     10096129.86      2990367.32     10096954.49
      2990940.26     10097353.81
#Sta/Elev= 30
  4337.2  825.85    4571  821.94    4746  814.15  4760.9  804.46  4767.8  770.99
  4843.7  745.61  4911.6  731.17 4938.41   719.1  4952.8  711.72  5001.8  710.13
  5004.6  709.63  5007.8  710.13  5041.2  714.01  5051.4  719.34  5062.8  726.39
  5139.6   760.9  5150.1  768.46  5155.5  783.93  5161.5  789.63  5178.8  792.83
  5184.3  797.98  5194.3  788.32  5207.6  782.89  5216.1  789.84  5225.4     805
  5230.9  808.65  5663.4  828.49  5838.9  831.07  5859.9  832.32  5937.2  834.24
#Mann= 7 ,-1 , 0
  4337.2     .16       0  4843.7     .12       0  5001.8     .07       0
  5007.8     .12       0  5062.8     .16       0  5838.9     .05       0
  5859.9      .1       0
Bank Sta=4938.41,5051.4
XS Rating Curve= 0 ,0
Exp/Cntr=0.3,0.1

Type RM Length L Ch R = 1 ,879     ,469,469,469
BEGIN DESCRIPTION:
HAMILTON CREEK 2.0
END DESCRIPTION:
XS GIS Cut Line= 4
      2989690.23     10096416.29        2989751.      10096772.2
       2990063.5     10097362.48      2990453.67      10097648.6
#Sta/Elev= 30
    4284  816.27  4545.6  815.19  4761.4  805.73  4777.7  793.68  4783.4  774.41
  4799.7  772.57  4805.4  766.57  4839.8  754.32  4865.8  746.99  4882.1  737.18
  4931.8  734.16  4946.8  725.23  4970.1  707.69  4994.8  697.29  4997.5  696.79
  5000.8  697.29  5014.1  698.44  5030.4  707.84  5052.4  721.34  5133.3  739.99
    5156  753.94  5178.6  752.79  5212.1  768.97  5235.2  780.04  5257.8  809.15
  5317.7  814.84    5333  815.98    5712  832.52  5718.5  832.79  5796.8  833.83
#Mann= 10 ,-1 , 0
    4284     .16       0  4839.8     .12       0  4946.8     .16       0
  4994.8     .07       0  5000.8     .16       0  5212.1     .05       0
  5317.7      .1       0    5333     .05       0    5712      .1       0
  5718.5     .05       0
Bank Sta=4970.1,5030.4
XS Rating Curve= 0 ,0
Exp/Cntr=0.3,0.1

Type RM Length L Ch R = 1 ,410     ,0,0,0
BEGIN DESCRIPTION:
HAMILTON CREEK 1.0
END DESCRIPTION:
XS GIS Cut Line= 4
      2989551.34     10096451.07      2989464.54     10096902.41
       2989481.9       10097484.      2990141.65     10097865.96
#Sta/Elev= 30
  4239.2  810.17  4760.2  803.55  4770.2  801.99  4780.2  782.84  4790.2  770.17
  4800.2  770.23  4820.2   756.6  4900.2  728.66  4930.2   721.3    4973  697.92
 4974.43  696.22  4990.3  685.85  4998.6  685.44  5001.3  684.94  5004.6  685.44
  5020.3  686.37  5030.3  694.82  5040.3  702.85  5070.3  715.24  5123.7  726.07
  5170.3   736.5  5220.4  763.78  5250.4  768.03  5260.4  780.85  5270.4  786.67
    5278  799.02  5625.3  816.07  5870.5  825.32  6032.9  826.91    6043  827.23
#Mann= 8 ,-1 , 0
  4239.2     .16       0    4973     .12       0  4998.6     .07       0
  5004.6     .12       0  5123.7     .16       0  5625.3     .05       0
  5870.5      .1       0  6032.9     .05       0
Bank Sta=4974.43,5030.3
XS Rating Curve= 0 ,0
Exp/Cntr=0.3,0.1

Chan Stop Cuts=-1
Use User Specified Reach Order=0
Composite Channel Slope=5