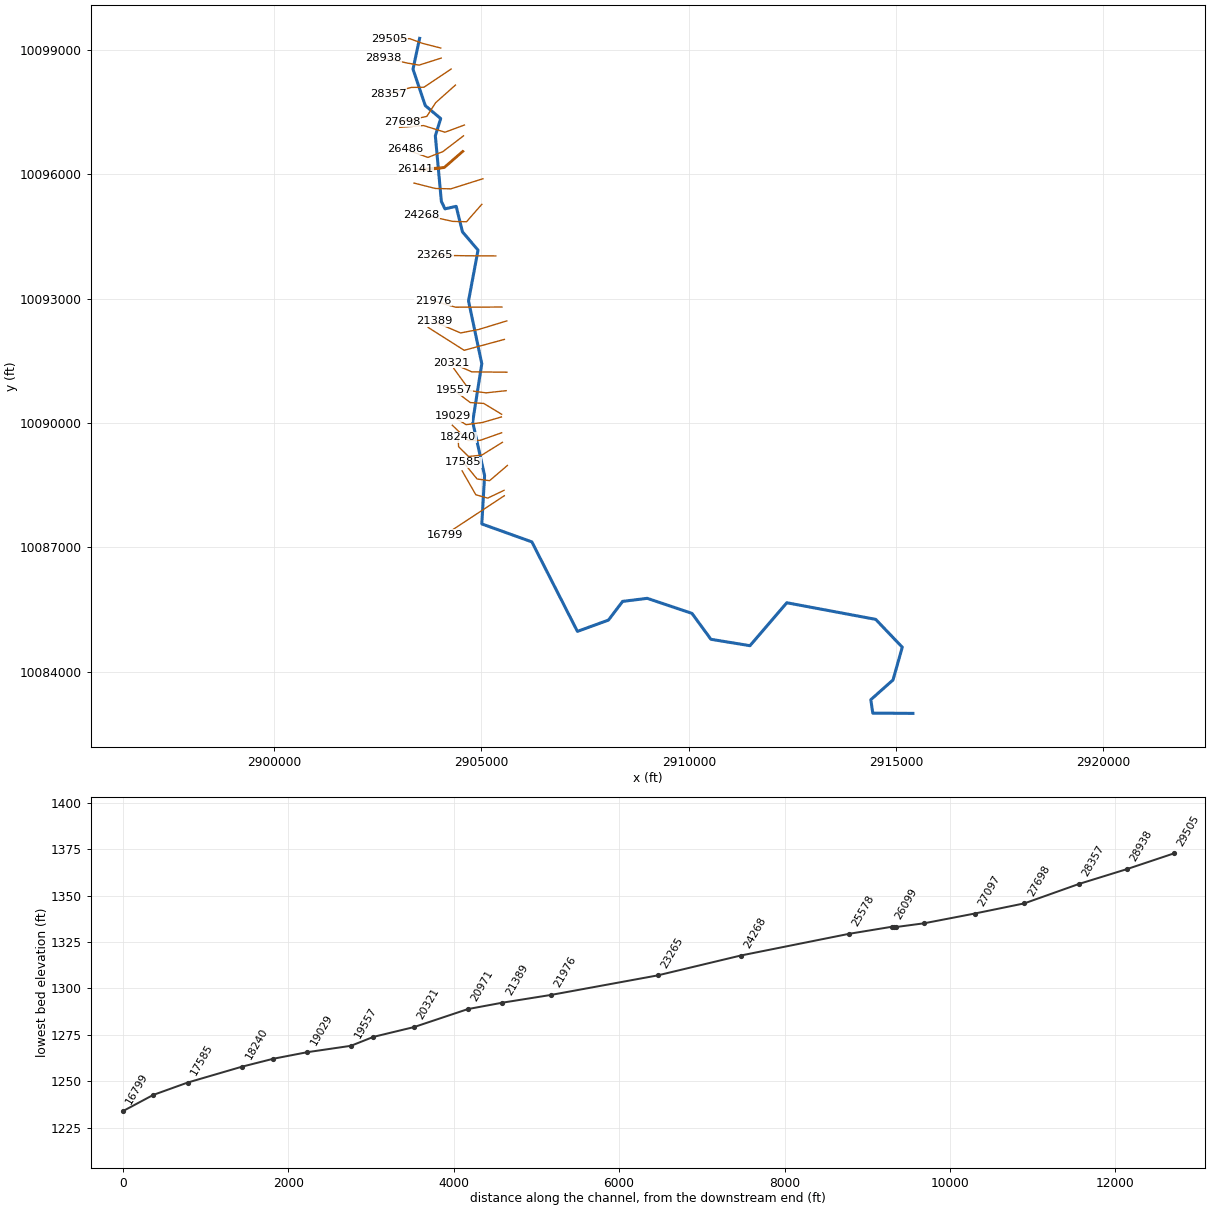
--- HARDIN RUSSELL CREEK.prj (project) ---

Proj Title=HARDIN RUSSELL CREEK Base Level Engineering
Current Plan=p01
Default Exp/Contr=0.3,0.1
English Units
Geom File=g01
Flow File=f01
Plan File=p01
Y Axis Title=Elevation
X Axis Title(PF)=Main Channel Distance
X Axis Title(XS)=Station
BEGIN DESCRIPTION:
HARDIN RUSSELL CREEK
END DESCRIPTION:
DSS Export Rating Curves= 0
DSS Export Rating Curve Sorted= 0
DSS Export Volume Flow Curves= 0
DXF OffsetX= 0
DXF OffsetY= 0
DXF ScaleX= 1
DXF ScaleY= 10

--- HARDIN RUSSELL CREEK.p01 (plan) ---

Plan Title=Multiple Run
Short Identifier=Multiple
Geom File=g01
Flow File=f01
Subcritical Flow
K Sum by GR= 0
Std Step Tol= 0.01
Critical Tol= 0.01
Num of Std Step Trials= 20
Max Error Tol= 0.3
Flow Tol Ratio= 0.001
Split Flow NTrial= 30
Split Flow Tol= 0.02
Split Flow Ratio= 0.02
Log Output Level= 0
Friction Slope Method= 1
Unsteady Friction Slope Method= 2
Unsteady Bridges Friction Slope Method= 1
Parabolic Critical Depth
Global Vel Dist=  1 , 1 , 1
Global Log Level= 0
CheckData=True
Encroach Param= -1, 0, 0, 0
BEGIN DESCRIPTION:
Multiple Run
END DESCRIPTION:

--- HARDIN RUSSELL CREEK.f01 (steady flow) ---

Flow Title=Multiple
Program Version=4.10
Number of Profiles= 7
Profile Names=10-year,25-year,50-year,1pct_min,100-year,1pct_plu,500-year
River Rch & RM=HARDIN RUSSELL C,Reach-1         ,29505
    1252    1850    2378    2235    3023    4088    4906
River Rch & RM=HARDIN RUSSELL C,Reach-1         ,16799
    2225    3376    4417    4216    5702    7711    9551
River Rch & RM=HARDIN RUSSELL C,Reach-1         ,16170
    2225    3376    4417    4216    5702    7711    9551
River Rch & RM=HARDIN RUSSELL C,Reach-1         ,9587
    2269    3439    4497    4290    5801    7846    9703
River Rch & RM=HARDIN RUSSELL C,Reach-1         ,5534
    3122    4798    6334    6094    8242   11146   14025
River Rch & RM=HARDIN RUSSELL C,Reach-1         ,5140
    3122    4798    6334    6094    8242   11146   14025
Boundary for River Rch & Prof#=HARDIN RUSSELL C,Reach-1         , 1
Up Type= 0
Dn Type= 3
Dn Slope=0.015
Boundary for River Rch & Prof#=HARDIN RUSSELL C,Reach-1         , 2
Up Type= 0
Dn Type= 3
Dn Slope=0.015
Boundary for River Rch & Prof#=HARDIN RUSSELL C,Reach-1         , 3
Up Type= 0
Dn Type= 3
Dn Slope=0.015
Boundary for River Rch & Prof#=HARDIN RUSSELL C,Reach-1         , 4
Up Type= 0
Dn Type= 3
Dn Slope=0.015
Boundary for River Rch & Prof#=HARDIN RUSSELL C,Reach-1         , 5
Up Type= 0
Dn Type= 3
Dn Slope=0.015
Boundary for River Rch & Prof#=HARDIN RUSSELL C,Reach-1         , 6
Up Type= 0
Dn Type= 3
Dn Slope=0.015
Boundary for River Rch & Prof#=HARDIN RUSSELL C,Reach-1         , 7
Up Type= 0
Dn Type= 3
Dn Slope=0.015
DSS Import GetInterval= 0
DSS Import GetPeak= 0
DSS Import FillOption= 0

--- HARDIN RUSSELL CREEK.g01 (geometry) ---

Geom Title=Existing Conditions
Program Version=4.10

River Reach=HARDIN RUSSELL C,Reach-1
Reach XY= 30
      2903508.47     10099283.73      2903349.11      10098538.3
      2903645.76     10097660.33      2904016.58     10097347.92
      2903887.97      10096931.4      2904033.17     10095350.24
       2904119.7     10095170.06       2904390.5     10095230.41
      2904541.98     10094614.97      2904917.36     10094173.84
      2904688.34     10092948.68       2905008.4     10091433.63
      2904788.03     10090030.75      2905075.87     10088735.56
      2905008.38      10087568.4      2906215.71     10087135.43
      2907314.46     10084975.92      2908061.88     10085247.79
      2908405.35     10085699.85      2908998.46     10085773.66
      2910077.02     10085410.25      2910534.46     10084785.34
      2911475.34     10084630.83      2912365.03      10085666.8
       2914508.5       10085266.      2915149.41     10084594.12
      2914926.16     10083804.58      2914390.28     10083327.68
      2914438.47     10083003.73      2915405.75     10082997.98

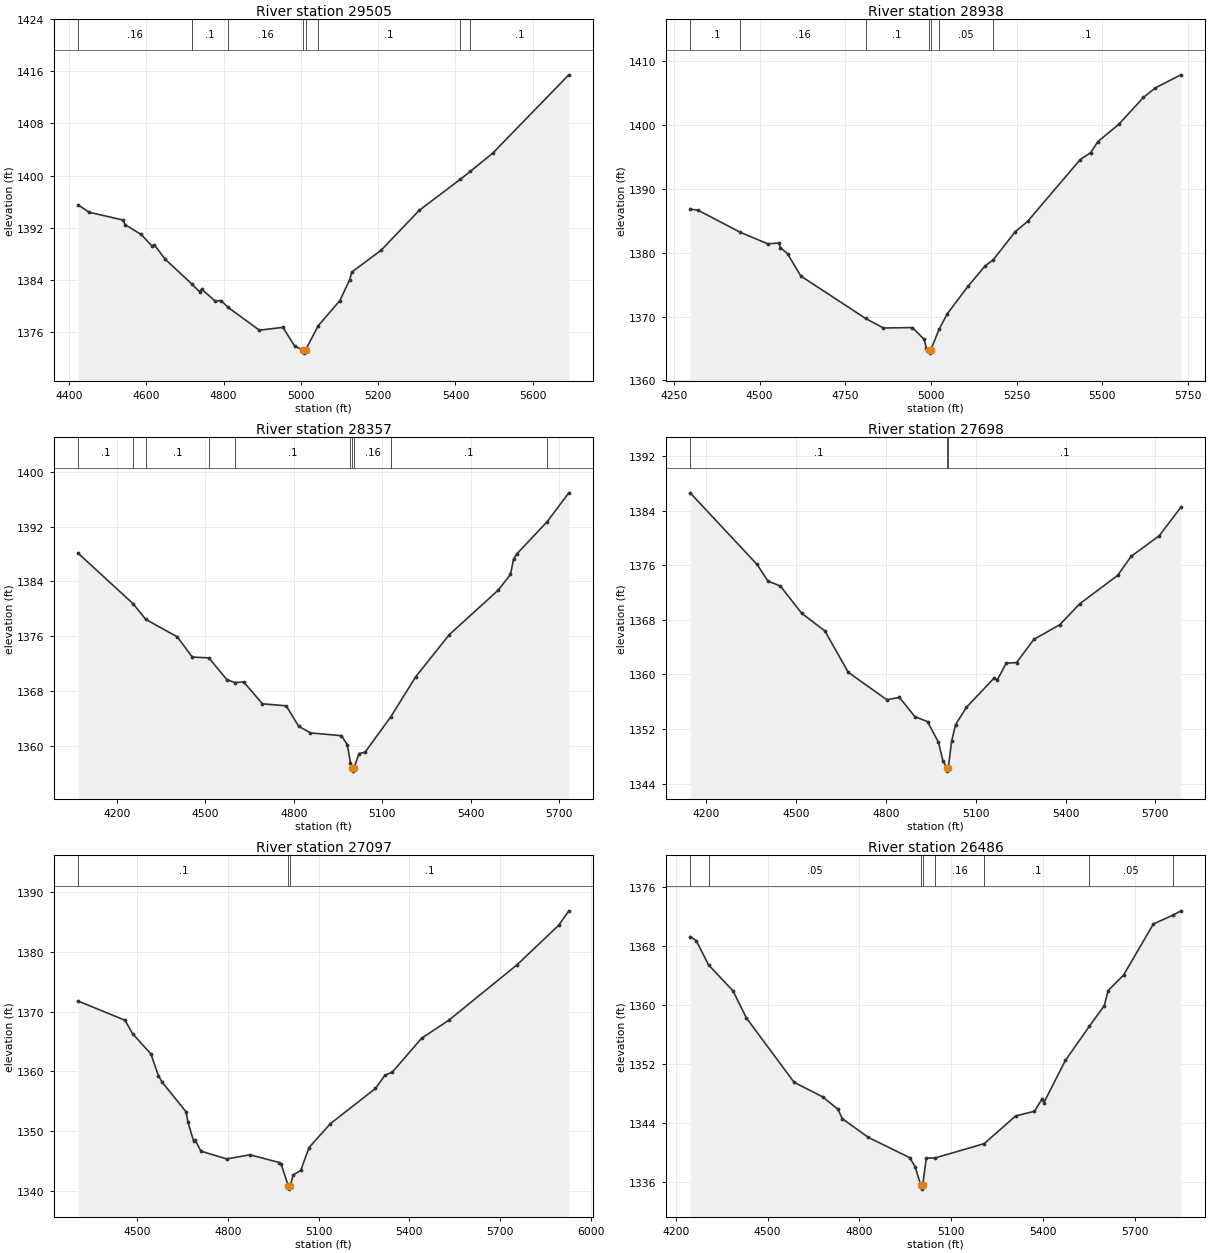
Type RM Length L Ch R = 1 ,29505   ,567,567,567
BEGIN DESCRIPTION:
HARDIN RUSSELL CREEK 60.0
END DESCRIPTION:
XS GIS Cut Line= 4
      2904016.45     10099050.04      2903578.12     10099162.88
      2903269.96     10099275.73      2902781.46     10099275.73
#Sta/Elev= 30
  4423.8 1395.49  4452.7 1394.36  4539.7 1393.17  4545.6 1392.44  4586.9 1390.95
  4615.9 1389.13  4621.1 1389.35  4648.9 1387.17  4718.2 1383.33  4738.1 1382.15
  4743.2 1382.55  4778.8 1380.71  4793.5 1380.81  4810.9  1379.8  4892.7 1376.25
  4953.8 1376.69  4984.3 1373.77  5006.5 1373.23  5009.2 1372.73  5012.5 1373.23
  5044.7 1376.93    5101  1380.8  5126.2 1383.99  5131.6 1385.16  5207.8 1388.54
  5306.1 1394.65  5412.1  1399.4    5438 1400.62  5496.1 1403.42  5693.1 1415.46
#Mann= 8 ,-1 , 0
  4423.8     .16       0  4718.2      .1       0  4810.9     .16       0
  5006.5     .07       0  5012.5     .16       0  5044.7      .1       0
  5412.1     .05       0    5438      .1       0
Bank Sta=5006.5,5012.5
XS Rating Curve= 0 ,0
Exp/Cntr=0.3,0.1

Type RM Length L Ch R = 1 ,28938   ,581,581,581
BEGIN DESCRIPTION:
HARDIN RUSSELL CREEK 59.0
END DESCRIPTION:
XS GIS Cut Line= 4
      2904029.49     10098806.97      2903495.66      10098637.7
      2903196.18     10098689.79      2902642.02     10098815.34
#Sta/Elev= 30
  4297.5 1386.79  4319.5 1386.67  4444.4 1383.17  4523.7 1381.39    4556  1381.5
  4561.2 1380.78  4581.8 1379.83  4620.5 1376.34  4809.8  1369.7  4861.6 1368.21
    4946 1368.28  4980.9 1366.42  4986.6 1365.13  4993.8 1364.78  4996.5 1364.28
  4999.8 1364.78  5024.3 1368.04  5047.5  1370.4  5108.4 1374.73  5158.4 1377.93
  5181.6 1378.85  5246.8  1383.3  5282.2 1384.88    5436 1394.57  5466.8 1395.66
  5487.3 1397.35  5548.8  1400.1  5620.6 1404.29  5655.5 1405.79  5729.7 1407.82
#Mann= 7 ,-1 , 0
  4297.5      .1       0  4444.4     .16       0  4809.8      .1       0
  4993.8     .07       0  4999.8      .1       0  5024.3     .05       0
  5181.6      .1       0
Bank Sta=4993.8,4999.8
XS Rating Curve= 0 ,0
Exp/Cntr=0.3,0.1

Type RM Length L Ch R = 1 ,28357   ,659,659,659
BEGIN DESCRIPTION:
HARDIN RUSSELL CREEK 58.0
END DESCRIPTION:
XS GIS Cut Line= 4
      2904268.25     10098542.23      2903612.85     10098103.85
      2903309.03     10098099.51      2902757.82      10097947.6
#Sta/Elev= 30
  4068.2 1388.11    4255 1380.71  4297.6 1378.44  4404.8 1375.88  4455.6 1372.93
  4511.7 1372.81  4572.7 1369.64  4599.8 1369.21  4629.7  1369.3  4693.5  1366.1
  4773.9 1365.81  4815.9 1362.84  4856.3 1361.85  4961.1 1361.45  4981.1 1360.13
  4991.9  1357.5  4998.1 1356.77  5000.8 1356.27  5004.1 1356.77  5021.1 1358.84
  5041.1 1359.02  5128.9 1364.22    5213 1370.05  5327.1 1376.21  5493.1 1382.71
  5534.5    1385    5545 1387.27  5555.3 1387.96    5659 1392.71  5732.3 1396.92
#Mann= 10 ,-1 , 0
  4068.2      .1       0    4255     .05       0  4297.6      .1       0
  4511.7     .05       0  4599.8      .1       0  4991.9     .16       0
  4998.1     .07       0  5004.1     .16       0  5128.9      .1       0
    5659     .05       0
Bank Sta=4998.1,5004.1
XS Rating Curve= 0 ,0
Exp/Cntr=0.3,0.1

Type RM Length L Ch R = 1 ,27698   ,601,601,601
BEGIN DESCRIPTION:
HARDIN RUSSELL CREEK 57.0
END DESCRIPTION:
XS GIS Cut Line= 4
      2904372.39     10098155.93      2903894.96     10097730.59
      2903682.29     10097400.73      2903087.66     10097274.85
#Sta/Elev= 30
  4145.8 1386.64  4369.6 1376.13  4405.5  1373.7  4447.3 1372.97  4518.4 1368.98
  4596.1 1366.38  4673.9 1360.33  4802.9 1356.29  4845.1 1356.63  4896.6 1353.82
  4938.9 1353.08  4975.2 1350.08  4990.3 1347.37  5002.5 1346.32  5005.3 1345.82
  5008.5 1346.32  5019.4 1350.19  5032.6 1352.63  5068.9 1355.18  5162.6 1359.52
  5171.8 1359.18    5202 1361.65  5236.7 1361.75    5294 1365.14  5380.7 1367.29
  5447.4 1370.36  5574.4 1374.54    5619 1377.31  5713.1 1380.34  5785.5 1384.53
#Mann= 3 ,-1 , 0
  4145.8      .1       0  5002.5     .07       0  5008.5      .1       0
Bank Sta=5002.5,5008.5
XS Rating Curve= 0 ,0
Exp/Cntr=0.3,0.1

Type RM Length L Ch R = 1 ,27097   ,611,611,611
BEGIN DESCRIPTION:
HARDIN RUSSELL CREEK 55.0
END DESCRIPTION:
XS GIS Cut Line= 4
      2904589.43      10097192.4      2904120.66     10097018.78
      2903604.17     10097179.37      2903023.05       10097136.
#Sta/Elev= 30
  4303.8 1371.78  4458.9 1368.57  4483.9 1366.34  4544.7 1362.93  4569.8 1359.27
  4582.1 1358.21    4661 1353.26  4667.4  1351.5    4686 1348.38  4691.4 1348.54
  4710.1 1346.68  4795.4 1345.38  4872.5 1346.07  4970.1 1344.77  4975.4 1344.53
  4999.7 1340.83  5002.4 1340.33  5005.7 1340.83  5015.4 1342.71  5040.4 1343.45
  5067.8 1347.28  5138.1 1351.25  5287.7 1357.17  5319.1 1359.37  5343.5  1359.9
  5440.5 1365.56  5530.8 1368.59  5756.3 1377.85  5893.7 1384.44  5927.3 1386.86
#Mann= 3 ,-1 , 0
  4303.8      .1       0  4999.7     .07       0  5005.7      .1       0
Bank Sta=4999.7,5005.7
XS Rating Curve= 0 ,0
Exp/Cntr=0.3,0.1

Type RM Length L Ch R = 1 ,26486   ,345,345,345
BEGIN DESCRIPTION:
HARDIN RUSSELL CREEK 54.0
END DESCRIPTION:
XS GIS Cut Line= 4
      2904567.67     10096931.95      2904068.58     10096550.03
      2903708.33     10096411.14      2903153.14     10096610.66
#Sta/Elev= 30
  4246.9 1369.33  4266.7 1368.79  4307.1 1365.49  4387.3 1361.95  4430.8  1358.3
  4586.7 1349.58  4680.2  1347.6    4730 1345.92  4744.6 1344.63  4829.8  1342.1
  4964.5 1339.36  4982.6 1338.14  5001.1 1335.59  5003.8 1335.09  5007.1 1335.59
  5019.1 1339.32  5046.3  1339.3  5208.5 1341.26  5311.3 1345.02  5372.7 1345.64
  5398.1 1347.36  5403.5 1346.82  5473.8 1352.54  5551.6 1357.14  5601.3 1359.98
  5613.2    1362    5664 1364.11  5761.5 1371.04  5825.2 1372.23  5851.4 1372.82
#Mann= 8 ,-1 , 0
  4246.9      .1       0  4307.1     .05       0  5001.1    .035       0
  5007.1     .05       0  5046.3     .16       0  5208.5      .1       0
  5551.6     .05       0  5825.2      .1       0
Bank Sta=5001.1,5007.1
XS Rating Curve= 0 ,0
Exp/Cntr=0.3,0.1

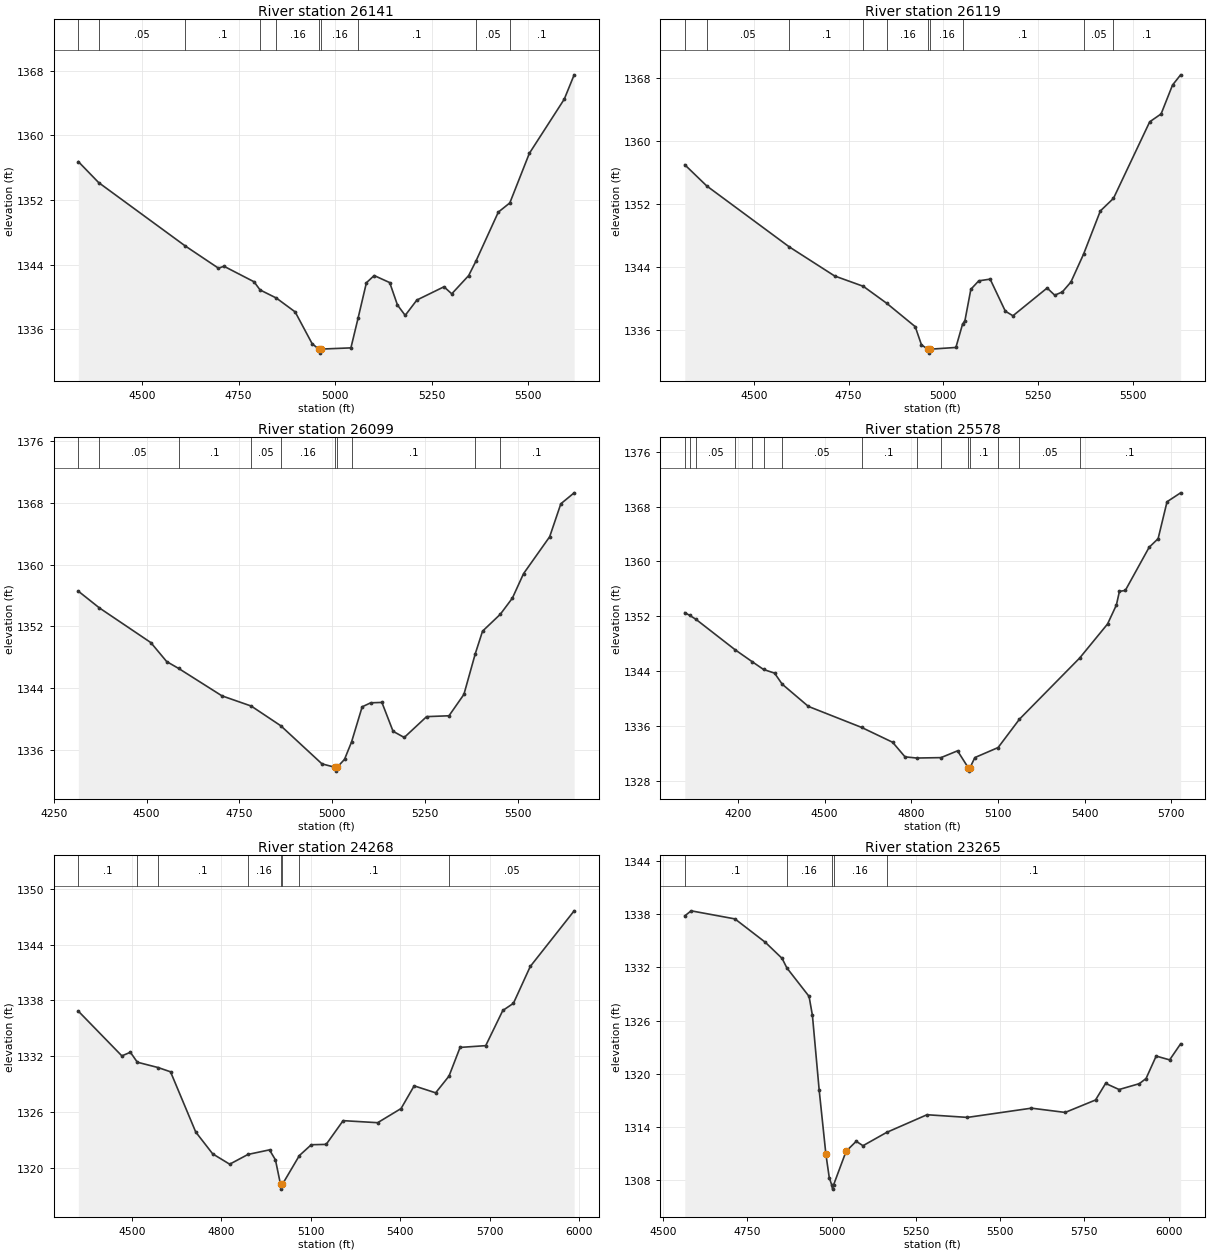
Type RM Length L Ch R = 1 ,26141   ,22,22,22
BEGIN DESCRIPTION:
Mapping XS 0284fab5
END DESCRIPTION:
XS GIS Cut Line= 3
      2904547.75     10096576.08      2904097.22     10096185.45
      2903412.94      10096124.3
#Sta/Elev= 30
  4335.1 1356.74  4387.8 1354.14  4611.6 1346.31  4697.8 1343.55    4712 1343.79
  4789.9 1341.87  4805.5 1340.86  4847.5 1339.86  4896.3 1338.14  4940.2 1334.21
  4957.3 1333.54    4960 1333.04  4963.3 1333.54  5040.6 1333.69    5059 1337.34
  5080.7 1341.75  5100.8 1342.64    5141 1341.77  5161.1 1338.99  5181.1 1337.71
  5211.3 1339.61  5281.5 1341.25  5301.6 1340.38  5345.4 1342.64  5364.3 1344.44
  5422.1 1350.49  5451.9 1351.63  5502.4 1357.76  5592.8 1364.47  5618.4 1367.48
#Mann= 10 ,-1 , 0
  4335.1      .1       0  4387.8     .05       0  4611.6      .1       0
  4805.5     .05       0  4847.5     .16       0  4957.3     .07       0
  4963.3     .16       0    5059      .1       0  5364.3     .05       0
  5451.9      .1       0
Bank Sta=4957.3,4963.3
XS Rating Curve= 0 ,0
Exp/Cntr=0.3,0.1

Type RM Length L Ch R = 1 ,26119   ,20,20,20
BEGIN DESCRIPTION:
Mapping XS 898c15d2
END DESCRIPTION:
XS GIS Cut Line= 4
      2904565.96     10096564.34      2904103.73     10096167.22
      2903974.83     10096150.29      2903407.16     10096106.02
#Sta/Elev= 30
  4317.8 1356.99  4375.8  1354.3  4593.6 1346.57  4713.3 1342.88  4788.9 1341.57
  4850.9 1339.41    4926 1336.45  4942.6 1334.13  4959.8 1333.59  4962.5 1333.09
  4965.8 1333.59  5033.4 1333.81    5051 1336.77  5057.2  1337.2  5072.9 1341.19
  5093.7 1342.26  5123.8 1342.48  5163.9 1338.41    5184 1337.83  5274.2 1341.35
  5294.3 1340.44  5314.3 1340.85    5337 1342.11  5370.5 1345.66  5414.7 1351.13
  5449.4 1352.73    5545 1362.44  5575.1 1363.44  5605.2  1367.1  5626.6  1368.4
#Mann= 10 ,-1 , 0
  4317.8      .1       0  4375.8     .05       0  4593.6      .1       0
  4788.9     .05       0  4850.9     .16       0  4959.8     .07       0
  4965.8     .16       0    5051      .1       0  5370.5     .05       0
  5449.4      .1       0
Bank Sta=4959.8,4965.8
XS Rating Curve= 0 ,0
Exp/Cntr=0.3,0.1

Type RM Length L Ch R = 1 ,26099   ,521,521,521
BEGIN DESCRIPTION:
HARDIN RUSSELL CREEK 53.0
END DESCRIPTION:
XS GIS Cut Line= 4
      2904572.52     10096555.71      2904112.41     10096152.03
      2903975.69     10096130.33      2903392.73     10096073.98
#Sta/Elev= 30
  4315.9 1356.55  4372.7 1354.38  4511.3 1349.89    4554 1347.43  4586.3 1346.54
    4703 1342.99  4781.8 1341.67  4861.4 1339.12  4972.5 1334.18  5007.4 1333.74
  5010.1 1333.24  5013.4 1333.74  5033.2 1334.76  5052.2 1337.02  5080.8 1341.57
  5103.8 1342.09    5134 1342.14  5164.1  1338.4  5194.2  1337.6  5254.5  1340.3
  5314.8 1340.41    5355 1343.18  5385.7 1348.46  5405.2 1351.37  5453.1 1353.56
  5485.6 1355.65  5515.7 1358.82  5586.1  1363.6  5616.2 1367.87  5652.1 1369.29
#Mann= 10 ,-1 , 0
  4315.9      .1       0  4372.7     .05       0  4586.3      .1       0
  4781.8     .05       0  4861.4     .16       0  5007.4     .07       0
  5013.4     .16       0  5052.2      .1       0  5385.7     .05       0
  5453.1      .1       0
Bank Sta=5007.4,5013.4
XS Rating Curve= 0 ,0
Exp/Cntr=0.3,0.1

Type RM Length L Ch R = 1 ,25578   ,1310,1310,1310
BEGIN DESCRIPTION:
HARDIN RUSSELL CREEK 51.0
END DESCRIPTION:
XS GIS Cut Line= 4
      2905034.72     10095895.95      2904262.15      10095652.9
      2903888.89     10095661.58       2903372.9     10095791.66
#Sta/Elev= 30
  4016.6 1352.52  4034.2 1352.11  4054.9 1351.56    4191  1347.1  4249.1 1345.39
  4288.9 1344.24  4327.2  1343.7  4353.4  1342.1  4444.1 1338.85    4628 1335.79
  4735.6 1333.62  4778.5 1331.49    4819 1331.32    4903 1331.38  4960.2 1332.37
  4997.2 1329.91    5000 1329.41  5003.2 1329.91  5020.2 1331.39  5100.6 1332.85
  5174.3 1336.98  5382.8 1345.91  5479.2 1350.87  5509.7 1353.63  5520.3 1355.63
  5540.6 1355.76  5623.1 1362.06  5654.1 1363.31    5685  1368.7    5732    1370
#Mann= 15 ,-1 , 0
  4016.6     .05       0  4034.2      .1       0  4054.9     .05       0
    4191      .1       0  4249.1     .05       0  4288.9      .1       0
  4353.4     .05       0    4628      .1       0    4819     .16       0
    4903      .1       0  4997.2     .07       0  5003.2      .1       0
  5100.6      .1       0  5174.3     .05       0  5382.8      .1       0
Bank Sta=4997.2,5003.2
XS Rating Curve= 0 ,0
Exp/Cntr=0.3,0.1

Type RM Length L Ch R = 1 ,24268   ,1003,1003,1003
BEGIN DESCRIPTION:
HARDIN RUSSELL CREEK 50.0
END DESCRIPTION:
XS GIS Cut Line= 4
       2905008.7     10095279.66      2904639.76     10094858.62
      2904309.89     10094867.31      2903554.69     10095032.24
#Sta/Elev= 30
  4320.2 1336.84  4466.2 1332.03  4494.7 1332.42  4518.1 1331.35  4587.4 1330.78
  4629.4 1330.32  4713.9 1323.85  4770.8  1321.5  4827.8 1320.39  4889.3 1321.44
  4961.3 1321.93  4981.3 1320.85  4998.3 1318.21  5001.1 1317.71  5004.3 1318.21
  5061.5 1321.32  5101.4 1322.48  5151.4 1322.52  5208.2 1325.07    5324 1324.85
  5402.5 1326.37  5446.4 1328.81  5518.5 1328.06  5563.3 1329.86  5600.4 1332.94
  5686.4 1333.13  5743.7 1336.91  5779.3 1337.68  5835.8 1341.64    5983 1347.62
#Mann= 8 ,-1 , 0
  4320.2      .1       0  4518.1     .05       0  4587.4      .1       0
  4889.3     .16       0  4998.3     .07       0  5004.3     .16       0
  5061.5      .1       0  5563.3     .05       0
Bank Sta=4998.3,5004.3
XS Rating Curve= 0 ,0
Exp/Cntr=0.3,0.1

Type RM Length L Ch R = 1 ,23265   ,1289,1289,1289
BEGIN DESCRIPTION:
HARDIN RUSSELL CREEK 48.0
END DESCRIPTION:
XS GIS Cut Line= 3
      2905347.24     10094033.97      2904622.39     10094038.31
      2903875.87     10094051.33
#Sta/Elev= 30
  4564.2  1337.8    4583 1338.37    4713 1337.46    4803 1334.83    4853 1333.01
  4867.1 1331.94    4933 1328.73    4943 1326.58    4963 1318.18    4983 1310.93
    4993  1308.3    5000 1307.52  5002.7 1307.02    5006 1307.52    5043 1311.29
    5073 1312.41    5093 1311.91  5163.2 1313.41    5283  1315.4    5403  1315.1
    5593 1316.14  5693.1 1315.66  5783.1 1317.06  5813.1 1318.93  5853.1 1318.24
  5913.1  1318.9  5933.1 1319.48  5963.1 1322.01  6003.1 1321.58  6035.7 1323.39
#Mann= 5 ,-1 , 0
  4564.2      .1       0  4867.1     .16       0    5000     .07       0
    5006     .16       0  5163.2      .1       0
Bank Sta=4983,5043
XS Rating Curve= 0 ,0
Exp/Cntr=0.3,0.1

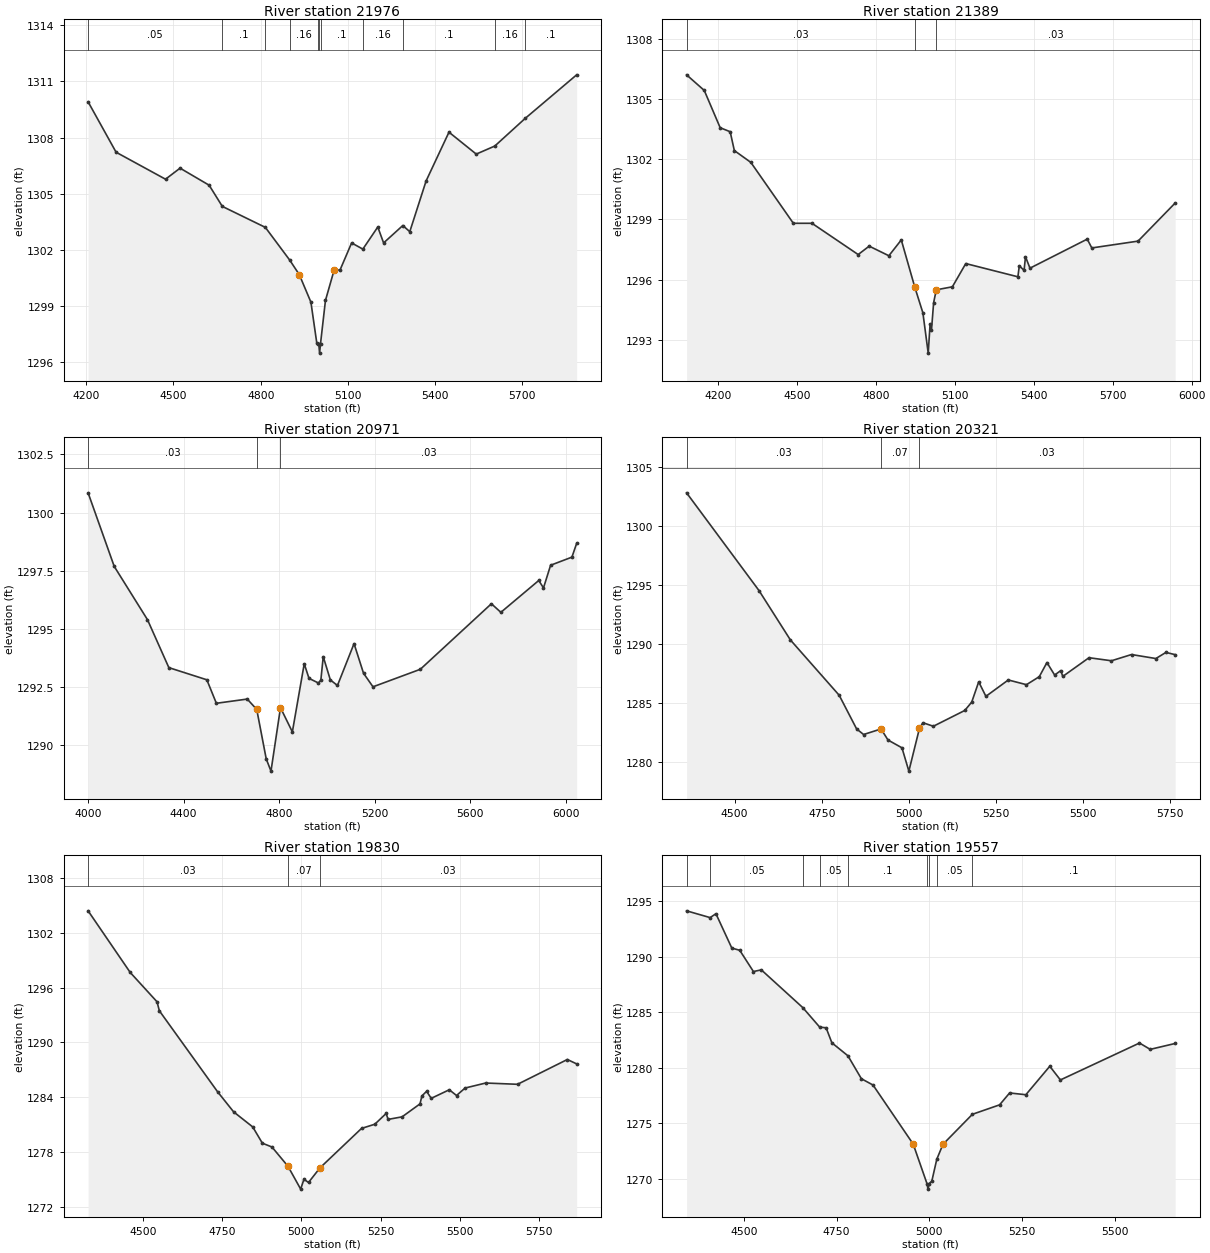
Type RM Length L Ch R = 1 ,21976   ,587,587,587
BEGIN DESCRIPTION:
HARDIN RUSSELL CREEK 47.0
END DESCRIPTION:
XS GIS Cut Line= 3
      2905494.78     10092801.33        2904375.     10092796.99
      2903836.81     10092953.24
#Sta/Elev= 30
  4206.3 1309.91  4302.6 1307.22  4472.6 1305.78  4522.6 1306.37  4622.6 1305.46
  4667.9 1304.33  4815.9 1303.21  4899.9 1301.46  4932.6 1300.69  4972.6 1299.22
  4992.6 1297.06  4998.6 1297.01  4999.6    1297  5002.4  1296.5  5005.6    1297
  5022.6 1299.31  5052.6 1300.94  5072.6 1300.93  5112.6 1302.38  5151.2 1302.05
  5202.6 1303.23  5222.6 1302.38  5288.7 1303.31  5312.6 1302.98  5368.8 1305.69
  5447.4 1308.29  5541.2 1307.12    5605 1307.55  5709.1 1309.02  5886.5 1311.35
#Mann= 11 ,-1 , 0
  4206.3     .05       0  4667.9      .1       0  4815.9     .05       0
  4899.9     .16       0  4998.6      .1       0  4999.6     .07       0
  5005.6      .1       0  5151.2     .16       0  5288.7      .1       0
    5605     .16       0  5709.1      .1       0
Bank Sta=4932.6,5052.6
XS Rating Curve= 0 ,0
Exp/Cntr=0.3,0.1

Type RM Length L Ch R = 1 ,21389   ,418,418,418
BEGIN DESCRIPTION:
HARDIN RUSSELL CREEK 44.0
END DESCRIPTION:
XS GIS Cut Line= 4
      2905612.02     10092467.14      2904930.55      10092258.8
      2904496.53     10092176.33      2903851.69     10092453.31
#Sta/Elev= 30
    4081 1306.22  4148.3 1305.44  4208.7 1303.58  4246.7 1303.38  4262.5 1302.44
  4325.2 1301.85  4486.7 1298.81  4557.5 1298.81    4733 1297.25  4774.9 1297.67
  4849.6 1297.19  4896.8 1297.98  4948.4 1295.61  4978.9 1294.34  4999.1 1292.33
  5006.3 1293.79  5011.4 1293.46  5019.7 1294.85  5029.8 1295.49  5090.9 1295.64
  5141.8  1296.8  5339.8 1296.14  5345.2 1296.69  5363.3 1296.46  5368.7 1297.14
  5385.7 1296.57  5603.3 1298.02  5620.6 1297.58  5796.3 1297.92  5937.2 1299.82
#Mann= 3 , 0 , 0
    4081     .03       0  4948.4     .07       0  5029.8     .03       0
Bank Sta=4948.4,5029.8
XS Rating Curve= 0 ,0
Exp/Cntr=0.3,0.1

Type RM Length L Ch R = 1 ,20971   ,650,650,650
BEGIN DESCRIPTION:
Mapping XS f510242a
END DESCRIPTION:
XS GIS Cut Line= 3
      2905553.72     10092020.38     2904583.623     10091757.35
     2903715.588    10092308.203
#Sta/Elev= 30
    4000 1300.85 4109.441297.683 4248.73 1295.39 4338.271293.326 4497.461292.802
 4537.261291.791  4666.61291.973  4706.41291.527 4746.191289.396 4766.091288.871
 4805.891291.602 4855.631290.559 4905.381293.492 4925.281292.864 4965.071292.663
 4975.021292.793 4984.971293.798 5014.791292.796 5044.551292.557 5113.991294.359
 5153.671293.085 5193.35  1292.5 5391.751293.255 5689.351296.075 5729.031295.706
 5887.751297.077 5907.581296.757 5937.341297.733 6026.621298.082 6046.461298.674
#Mann= 3 , 0 , 0
    4000     .03       0  4706.4     .05       0 4805.89     .03       0
Bank Sta=4706.4,4805.89
XS Rating Curve= 0 ,0
Exp/Cntr=0.3,0.1

Type RM Length L Ch R = 1 ,20321   ,491,491,491
BEGIN DESCRIPTION:
HARDIN RUSSELL CREEK 43.0
END DESCRIPTION:
XS GIS Cut Line= 3
      2905616.28     10091228.63      2904766.42     10091237.58
      2904262.18     10091460.69
#Sta/Elev= 30
  4362.3 1302.82  4570.1 1294.52  4660.1 1290.33  4800.1 1285.63  4850.1 1282.77
  4870.1  1282.3  4920.1 1282.77  4940.1 1281.83  4980.1 1281.17  4999.9 1279.19
  5030.2 1282.81  5040.2  1283.3  5070.2    1283  5160.2 1284.34  5180.2 1285.05
  5200.2 1286.77  5220.9 1285.54  5285.1 1286.93  5337.2 1286.53    5374 1287.21
  5395.9 1288.41    5418 1287.35  5435.8 1287.73  5441.3 1287.23  5516.6 1288.82
    5581 1288.56  5638.5 1289.09  5708.4 1288.75  5737.2 1289.27  5763.6 1289.08
#Mann= 3 , 0 , 0
  4362.3     .03       0  4920.1     .07       0  5030.2     .03       0
Bank Sta=4920.1,5030.2
XS Rating Curve= 0 ,0
Exp/Cntr=0.3,0.1

Type RM Length L Ch R = 1 ,19830   ,273,273,273
BEGIN DESCRIPTION:
HARDIN RUSSELL CREEK 42.0
END DESCRIPTION:
XS GIS Cut Line= 4
      2905594.58      10090783.1      2905112.85     10090731.02
      2904722.22      10090783.1      2904333.44     10091318.76
#Sta/Elev= 30
  4327.6 1304.44  4460.4 1297.68    4545 1294.46  4552.2 1293.48  4735.7  1284.6
  4786.4 1282.39  4846.8 1280.73  4877.1 1278.95  4907.4 1278.53  4957.8 1276.42
  4997.9 1273.91  5008.2 1274.99  5022.6 1274.64  5058.7 1276.24  5189.8 1280.57
  5231.7 1281.03  5267.4 1282.21  5273.6 1281.56  5317.7 1281.84  5374.1 1283.26
  5380.3 1284.14  5394.9 1284.64  5409.6 1283.87  5466.5 1284.81  5489.3 1284.18
  5516.3    1285  5581.3 1285.55  5681.8 1285.41  5838.7 1288.13  5868.1 1287.65
#Mann= 3 , 0 , 0
  4327.6     .03       0  4957.8     .07       0  5058.7     .03       0
Bank Sta=4957.8,5058.7
XS Rating Curve= 0 ,0
Exp/Cntr=0.3,0.1

Type RM Length L Ch R = 1 ,19557   ,528,528,528
BEGIN DESCRIPTION:
HARDIN RUSSELL CREEK 41.0
END DESCRIPTION:
XS GIS Cut Line= 4
       2905486.1     10090214.53      2905056.42     10090474.94
       2904730.9     10090496.65      2904341.84      10090790.6
#Sta/Elev= 30
  4345.8 1294.12  4409.3 1293.51  4424.9 1293.86  4467.7 1290.77  4489.1 1290.57
  4525.9 1288.66  4547.2 1288.81  4659.1 1285.41  4704.5 1283.66  4721.8  1283.6
  4737.3 1282.25  4780.6 1281.08  4816.8 1279.02  4848.2 1278.45  4956.4 1273.14
  4993.5 1269.59  4996.3 1269.09  4999.5 1269.59  5006.5  1269.8    5020 1271.78
  5036.6 1273.12  5115.9 1275.82  5189.2 1276.67  5216.2 1277.74  5259.9 1277.58
  5324.4 1280.14    5353 1278.91  5566.1 1282.23    5595 1281.66  5662.1 1282.19
#Mann= 9 ,-1 , 0
  4345.8      .1       0  4409.3     .05       0  4659.1      .1       0
  4704.5     .05       0  4780.6      .1       0  4993.5     .07       0
  4999.5      .1       0    5020     .05       0  5115.9      .1       0
Bank Sta=4956.4,5036.6
XS Rating Curve= 0 ,0
Exp/Cntr=0.3,0.1

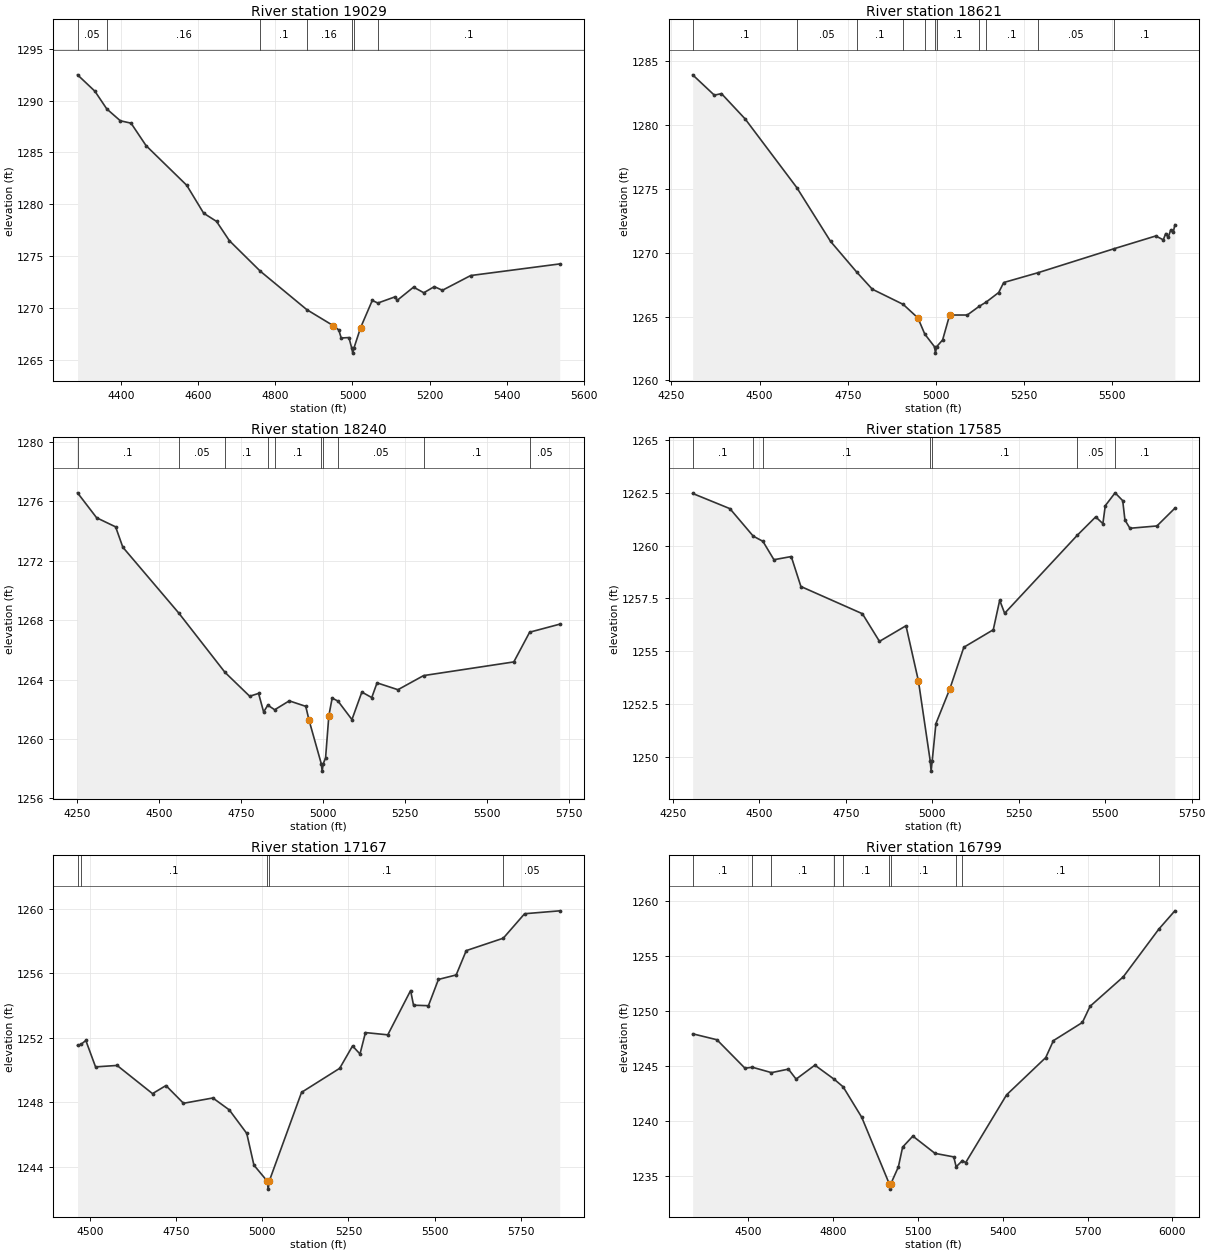
Type RM Length L Ch R = 1 ,19029   ,408,408,408
BEGIN DESCRIPTION:
HARDIN RUSSELL CREEK 40.0
END DESCRIPTION:
XS GIS Cut Line= 4
      2905481.75     10090149.42       2905021.7     10090014.87
      2904631.08     10089962.79      2904309.88     10090162.45
#Sta/Elev= 30
  4286.3 1292.48  4331.4  1290.9  4362.3 1289.19  4397.4 1288.05  4425.2 1287.82
  4464.3 1285.65  4569.8 1281.83  4613.7 1279.14  4647.1 1278.35  4680.5 1276.49
    4761 1273.54  4881.5 1269.84  4950.5 1268.29  4964.5 1267.88  4970.7 1267.11
  4990.8 1267.15  4997.9 1266.15  5000.7 1265.65  5003.9 1266.15  5021.1 1268.11
  5051.4 1270.73  5065.9 1270.48  5110.8 1271.08  5115.8 1270.73  5158.5 1272.01
  5185.2 1271.47  5212.3 1272.06  5233.5 1271.71  5306.8 1273.13  5537.9 1274.25
#Mann= 7 ,-1 , 0
  4286.3     .05       0  4362.3     .16       0    4761      .1       0
  4881.5     .16       0  4997.9     .07       0  5003.9     .16       0
  5065.9      .1       0
Bank Sta=4950.5,5021.1
XS Rating Curve= 0 ,0
Exp/Cntr=0.3,0.1

Type RM Length L Ch R = 1 ,18621   ,381,381,381
BEGIN DESCRIPTION:
HARDIN RUSSELL CREEK 39.0
END DESCRIPTION:
XS GIS Cut Line= 4
      2905486.11     10089767.48      2904969.62     10089585.19
      2904683.16     10089580.85      2904297.43     10089949.24
#Sta/Elev= 30
  4310.2  1283.9  4371.6 1282.31  4391.9 1282.43  4459.1 1280.45  4605.6 1275.08
  4701.2 1270.88  4775.7 1268.47  4819.6 1267.14  4907.4 1265.95  4949.1 1264.89
  4968.5 1263.63  4996.1 1262.64  4998.8 1262.14  5002.1 1262.64  5019.1 1263.17
  5039.1 1265.12  5089.1 1265.12  5122.9  1265.8  5142.6 1266.13  5178.2 1266.88
  5192.4 1267.66    5290 1268.43  5506.1 1270.31  5623.6  1271.3    5645    1271
  5651.9 1271.49  5659.1  1271.2    5666 1271.76  5673.3 1271.58  5677.8 1272.18
#Mann= 11 ,-1 , 0
  4310.2      .1       0  4605.6     .05       0  4775.7      .1       0
  4907.4     .05       0  4968.5      .1       0  4996.1     .07       0
  5002.1      .1       0  5122.9     .05       0  5142.6      .1       0
    5290     .05       0  5506.1      .1       0
Bank Sta=4949.1,5039.1
XS Rating Curve= 0 ,0
Exp/Cntr=0.3,0.1

Type RM Length L Ch R = 1 ,18240   ,655,655,655
BEGIN DESCRIPTION:
HARDIN RUSSELL CREEK 38.0
END DESCRIPTION:
XS GIS Cut Line= 5
      2905505.83      10089537.7      2905010.57     10089230.23
      2904688.38     10089195.25      2904449.04     10089430.91
      2904434.32     10089657.32
#Sta/Elev= 30
  4250.7 1276.57    4309 1274.89  4366.8 1274.28  4388.8 1272.91  4559.3 1268.48
  4700.1 1264.49  4775.5 1262.88  4802.6 1263.07    4818 1261.82  4830.7 1262.28
  4851.7 1261.97  4896.1 1262.57  4946.4  1262.2  4956.5 1261.26  4993.7 1258.34
  4996.4 1257.84  4999.7 1258.34  5006.8 1258.72  5016.8 1261.57  5026.9 1262.76
  5044.8 1262.55  5087.2 1261.31  5117.4 1263.16  5147.6 1262.79  5163.7 1263.78
  5227.4 1263.32  5305.6 1264.27  5580.6 1265.19  5628.9 1267.19  5720.5 1267.73
#Mann= 10 ,-1 , 0
  4250.7      .1       0  4559.3     .05       0  4700.1      .1       0
  4830.7     .05       0  4851.7      .1       0  4993.7     .07       0
  4999.7      .1       0  5044.8     .05       0  5305.6      .1       0
  5628.9     .05       0
Bank Sta=4956.5,5016.8
XS Rating Curve= 0 ,0
Exp/Cntr=0.3,0.1

Type RM Length L Ch R = 1 ,17585   ,418,418,418
BEGIN DESCRIPTION:
HARDIN RUSSELL CREEK 37.0
END DESCRIPTION:
XS GIS Cut Line= 4
      2905625.28      10088978.7      2905195.84     10088611.88
      2904896.14     10088652.14      2904560.82     10089058.99
#Sta/Elev= 30
    4307 1262.47  4414.7 1261.75    4482 1260.45  4510.2  1260.2    4542 1259.33
  4592.1 1259.48    4620 1258.06  4797.8 1256.77  4847.2 1255.46  4923.9  1256.2
  4959.9 1253.58  4993.8 1249.81  4996.6 1249.31  4999.8 1249.81  5010.4 1251.56
  5050.7 1253.21  5091.1 1255.18  5176.3 1256.01  5194.9 1257.41  5209.2 1256.79
  5419.3 1260.49  5472.5 1261.36  5493.3 1261.04  5500.2 1261.89  5528.6  1262.5
  5550.6 1262.13  5557.1 1261.21  5571.5 1260.82  5649.6 1260.93  5701.4 1261.77
#Mann= 7 ,-1 , 0
    4307      .1       0    4482     .05       0  4510.2      .1       0
  4993.8     .07       0  4999.8      .1       0  5419.3     .05       0
  5528.6      .1       0
Bank Sta=4959.9,5050.7
XS Rating Curve= 0 ,0
Exp/Cntr=0.3,0.1

Type RM Length L Ch R = 1 ,17167   ,368,368,368
BEGIN DESCRIPTION:
HARDIN RUSSELL CREEK 36.0
END DESCRIPTION:
XS GIS Cut Line= 4
      2905544.77      10088379.3       2905151.1     10088191.41
      2904864.83     10088271.93      2904533.87     10088848.86
#Sta/Elev= 30
  4464.2 1251.53  4474.9 1251.61  4488.3 1251.84  4516.5  1250.2    4579 1250.29
  4681.7 1248.54  4720.7 1249.04  4771.6 1247.94  4856.8 1248.27  4904.4 1247.53
  4955.1 1246.07  4975.9  1244.1  5014.4 1243.11  5017.2 1242.61  5020.4 1243.11
  5114.1 1248.62  5224.6 1250.11    5262  1251.5  5283.6    1251  5299.4 1252.33
  5364.2 1252.19  5430.4 1254.94  5438.9 1254.03  5482.1    1254  5511.1 1255.63
  5562.6 1255.91  5591.8 1257.42  5699.2 1258.19  5761.1 1259.71  5862.9 1259.89
#Mann= 5 ,-1 , 0
  4464.2     .16       0  4474.9      .1       0  5014.4     .07       0
  5020.4      .1       0  5699.2     .05       0
Bank Sta=5014.4,5020.4
XS Rating Curve= 0 ,0
Exp/Cntr=0.3,0.1

Type RM Length L Ch R = 1 ,16799   ,629,629,629
BEGIN DESCRIPTION:
HARDIN RUSSELL CREEK 35.0
END DESCRIPTION:
XS GIS Cut Line= 2
      2905551.21     10088248.38      2904127.58     10087310.86
#Sta/Elev= 30
  4304.2 1247.97  4389.9 1247.43  4489.2 1244.84  4515.3 1244.93  4582.8 1244.44
  4642.7 1244.76  4669.9 1243.85  4736.2 1245.12  4804.9 1243.83  4836.1 1243.15
  4901.9 1240.38    4999 1234.35  5001.7 1233.85    5005 1234.35  5031.4 1235.87
  5046.4 1237.67  5082.6 1238.67  5160.9  1237.1  5227.2 1236.78  5235.7 1235.88
    5258 1236.45  5269.3 1236.26  5413.9 1242.42  5552.4 1245.81  5579.5 1247.35
  5681.9    1249    5709 1250.47  5826.5 1253.15  5951.9 1257.48  6008.8 1259.15
#Mann= 10 ,-1 , 0
  4304.2      .1       0  4515.3     .05       0  4582.8      .1       0
  4804.9     .05       0  4836.1      .1       0    4999     .07       0
    5005      .1       0  5235.7     .16       0    5258      .1       0
  5951.9     .16       0
#XS Ineff= 2 , 0
                         5086.36         1238.37
Permanent Ineff=
       F       F
Bank Sta=4999,5005
XS Rating Curve= 0 ,0
Exp/Cntr=0.3,0.1