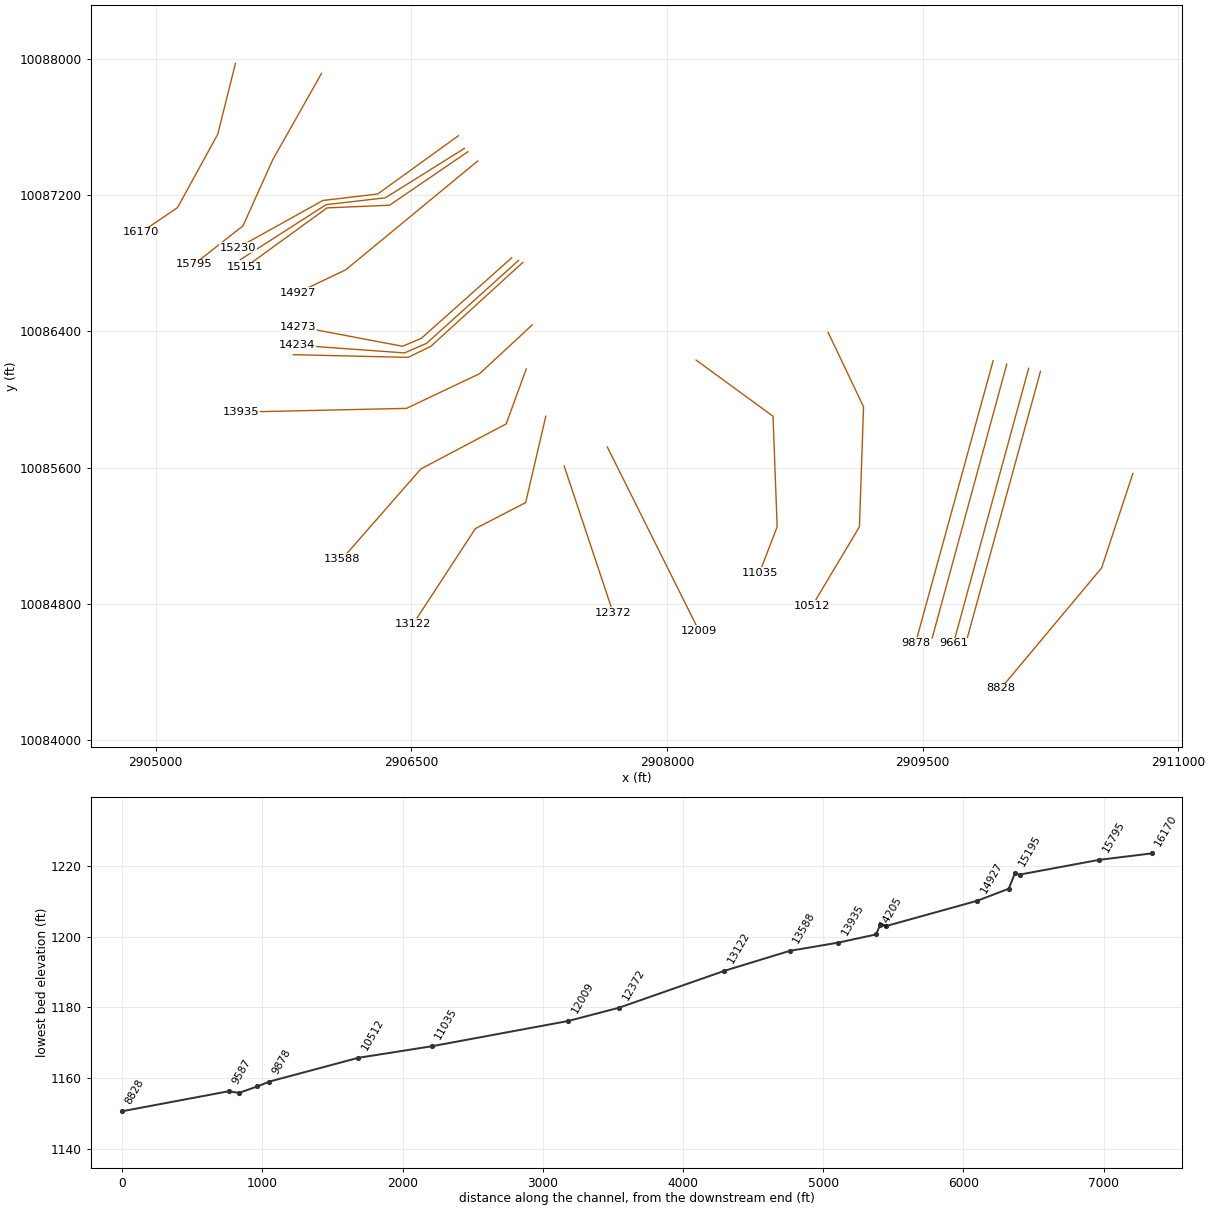
HEC-RAS study HARDIN RUSSELL CREEK.prj: HARDIN RUSSELL CREEK Base Level Engineering

--- HARDIN RUSSELL CREEK.g01 (geometry) --- (continued)

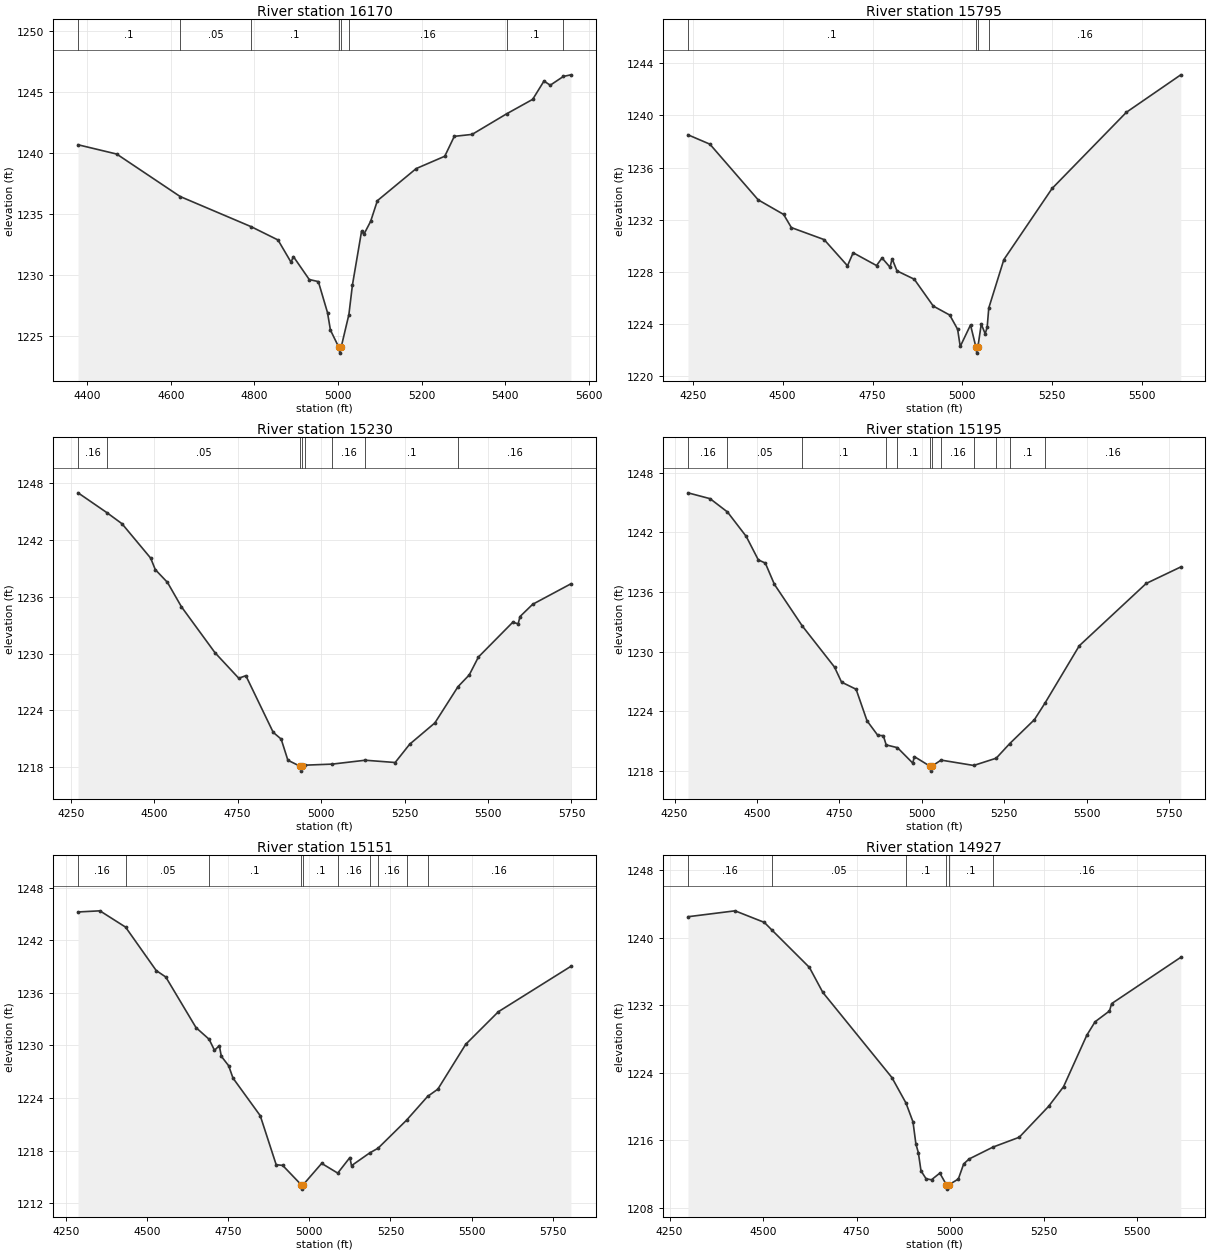
Type RM Length L Ch R = 1 ,16170   ,375,375,375
BEGIN DESCRIPTION:
HARDIN RUSSELL CREEK 34.0
END DESCRIPTION:
XS GIS Cut Line= 4
      2905467.58     10087973.46      2905363.42     10087556.83
      2905127.31     10087126.28      2904912.72      10086980.9
#Sta/Elev= 30
  4377.9 1240.66  4470.4  1239.9  4622.3 1236.42  4792.2 1233.95  4856.5 1232.86
  4887.7 1231.04  4893.4  1231.5  4931.3 1229.62  4953.1 1229.45    4975 1226.91
    4982 1225.48  5001.8 1224.09  5004.5 1223.59  5007.8 1224.09  5026.2 1226.75
  5034.7 1229.18  5056.5 1233.57  5062.2 1233.33  5078.3 1234.39  5094.4 1236.08
  5187.3 1238.71  5255.7 1239.72  5278.5 1241.35  5321.2 1241.51  5403.5 1243.19
  5466.1 1244.38  5493.2 1245.88  5508.2 1245.54  5539.7 1246.26  5557.6 1246.39
#Mann= 8 ,-1 , 0
  4377.9      .1       0  4622.3     .05       0  4792.2      .1       0
  5001.8     .07       0  5007.8      .1       0  5026.2     .16       0
  5403.5      .1       0  5539.7     .16       0
Bank Sta=5001.8,5007.8
XS Rating Curve= 0 ,0
Exp/Cntr=0.3,0.1

Type RM Length L Ch R = 1 ,15795   ,565,565,565
BEGIN DESCRIPTION:
Mapping XS 1b337a95
END DESCRIPTION:
XS GIS Cut Line= 4
       2905972.2     10087914.15      2905685.76     10087406.37
      2905512.15     10087020.08      2905225.69     10086794.38
#Sta/Elev= 30
  4236.4 1238.51  4297.5 1237.79  4431.8 1233.52  4502.6  1232.4  4524.2 1231.39
  4615.3 1230.47  4680.3 1228.46  4696.1 1229.46  4761.1 1228.48  4776.5 1229.06
  4798.7 1228.35  4804.5    1229    4818 1228.07  4866.1 1227.43    4919 1225.37
  4964.8 1224.68  4986.7 1223.59    4994 1222.27  5022.6 1223.92  5037.3 1222.26
  5040.1 1221.76  5043.3 1222.26  5052.5 1223.99  5063.5 1223.24    5069 1223.76
  5073.4 1225.22  5115.3 1228.93  5249.5 1234.39  5456.4 1240.24  5607.6 1243.11
#Mann= 4 ,-1 , 0
  4236.4      .1       0  5037.3     .07       0  5043.3      .1       0
  5073.4     .16       0
Bank Sta=5037.3,5043.3
XS Rating Curve= 0 ,0
Exp/Cntr=0.3,0.1

Type RM Length L Ch R = 1 ,15230   ,35,35,35
BEGIN DESCRIPTION:
Mapping XS 3b95db91
END DESCRIPTION:
XS GIS Cut Line= 4
      2906776.06     10087548.75      2906302.08     10087206.71
       2905980.9     10087168.52      2905484.42      10086892.5
#Sta/Elev= 30
  4272.2 1246.96  4359.3 1244.85  4403.8  1243.7  4489.7 1240.07  4503.5 1238.86
    4540 1237.51  4581.8 1234.94  4682.4 1230.09  4753.5  1227.4  4774.8 1227.67
  4856.7 1221.69  4880.5 1220.98  4900.6 1218.75  4937.9  1218.1  4940.7  1217.6
  4943.9  1218.1  4952.9 1218.23  5033.3 1218.34  5132.2 1218.75  5221.9 1218.51
  5265.4 1220.44  5340.9 1222.69  5410.1 1226.51  5443.8 1227.75  5471.3 1229.64
  5574.2 1233.31  5590.2 1233.14  5595.9 1233.91  5633.7  1235.2  5748.2 1237.36
#Mann= 8 ,-1 , 0
  4272.2     .16       0  4359.3     .05       0  4937.9     .07       0
  4943.9     .05       0  4952.9      .1       0  5033.3     .16       0
  5132.2      .1       0  5410.1     .16       0
Bank Sta=4937.9,4943.9
XS Rating Curve= 0 ,0
Exp/Cntr=0.3,0.1

Type RM Length L Ch R = 1 ,15195   ,44,44,44
BEGIN DESCRIPTION:
Mapping XS 4f83312d
END DESCRIPTION:
XS GIS Cut Line= 4
       2906810.8      10087474.1      2906347.22     10087184.15
        2906000.     10087144.21      2905496.56     10086821.32
#Sta/Elev= 30
  4290.5 1245.97  4357.7 1245.38  4410.4 1244.04  4467.3 1241.58  4503.9 1239.22
  4525.1  1238.9  4552.7 1236.76    4637 1232.58    4735 1228.43  4756.2 1226.92
  4800.4  1226.2  4833.6 1223.02  4866.2 1221.56    4883 1221.53  4891.6  1220.6
  4925.9 1220.32  4972.1 1218.77  4977.1 1219.42  5024.3 1218.46    5027 1217.96
  5030.3 1218.46  5058.1 1219.07    5157 1218.53  5225.2 1219.26  5266.5 1220.74
  5341.1 1223.14  5373.4 1224.82  5477.2 1230.58  5680.1 1236.85  5784.9 1238.51
#Mann= 12 ,-1 , 0
  4290.5     .16       0  4410.4     .05       0    4637      .1       0
  4891.6     .05       0  4925.9      .1       0  5024.3     .07       0
  5030.3      .1       0  5058.1     .16       0    5157      .1       0
  5225.2     .16       0  5266.5      .1       0  5373.4     .16       0
Bank Sta=5024.3,5030.3
XS Rating Curve= 0 ,0
Exp/Cntr=0.3,0.1

Type RM Length L Ch R = 1 ,15151   ,224,224,224
BEGIN DESCRIPTION:
HARDIN RUSSELL CREEK 33.0
END DESCRIPTION:
XS GIS Cut Line= 4
      2906831.57     10087454.96      2906371.53     10087140.74
      2906005.21     10087125.12      2905524.33     10086776.18
#Sta/Elev= 30
  4287.8 1245.25  4355.1 1245.38  4434.1 1243.52  4528.5 1238.56    4558 1237.82
  4651.1 1232.04  4691.4 1230.71    4708 1229.45  4722.9 1229.98    4729 1228.77
  4751.7 1227.68  4764.9 1226.28  4848.9 1221.98    4898 1216.38    4918  1216.3
  4975.1 1214.09  4977.8 1213.59  4981.1 1214.09  5038.1 1216.53  5087.6 1215.42
    5125  1217.2    5130 1216.27  5186.2 1217.73  5211.7 1218.26  5299.4 1221.46
  5364.4 1224.18  5395.9 1225.01  5481.7 1230.13  5582.2 1233.85  5805.7 1239.04
#Mann= 10 ,-1 , 0
  4287.8     .16       0  4434.1     .05       0  4691.4      .1       0
  4975.1     .07       0  4981.1      .1       0  5087.6     .16       0
  5186.2      .1       0  5211.7     .16       0  5299.4      .1       0
  5364.4     .16       0
Bank Sta=4975.1,4981.1
XS Rating Curve= 0 ,0
Exp/Cntr=0.3,0.1

Type RM Length L Ch R = 1 ,14927   ,654,654,654
BEGIN DESCRIPTION:
HARDIN RUSSELL CREEK 32.0
END DESCRIPTION:
XS GIS Cut Line= 3
       2906888.9      10087400.3      2906114.58      10086761.4
      2905831.62     10086626.82
#Sta/Elev= 30
  4299.2 1242.48  4425.1 1243.18  4503.3 1241.81  4523.7  1240.9  4623.9 1236.47
  4659.7 1233.51  4844.3 1223.42  4881.9  1220.4  4900.7 1218.16  4908.5 1215.53
    4915 1214.52  4922.1 1212.36  4935.8 1211.41  4950.2  1211.3  4972.4 1212.09
  4990.2 1210.69  4992.9 1210.19  4996.2 1210.69  5021.9 1211.39  5036.2 1213.18
  5050.5 1213.76  5114.3 1215.17  5184.7 1216.34  5262.9 1219.99  5303.1 1222.33
  5365.2 1228.43  5387.4 1230.03  5425.9 1231.31  5431.6 1232.18  5616.4 1237.67
#Mann= 6 ,-1 , 0
  4299.2     .16       0  4523.7     .05       0  4881.9      .1       0
  4990.2     .07       0  4996.2      .1       0  5114.3     .16       0
Bank Sta=4990.2,4996.2
XS Rating Curve= 0 ,0
Exp/Cntr=0.3,0.1

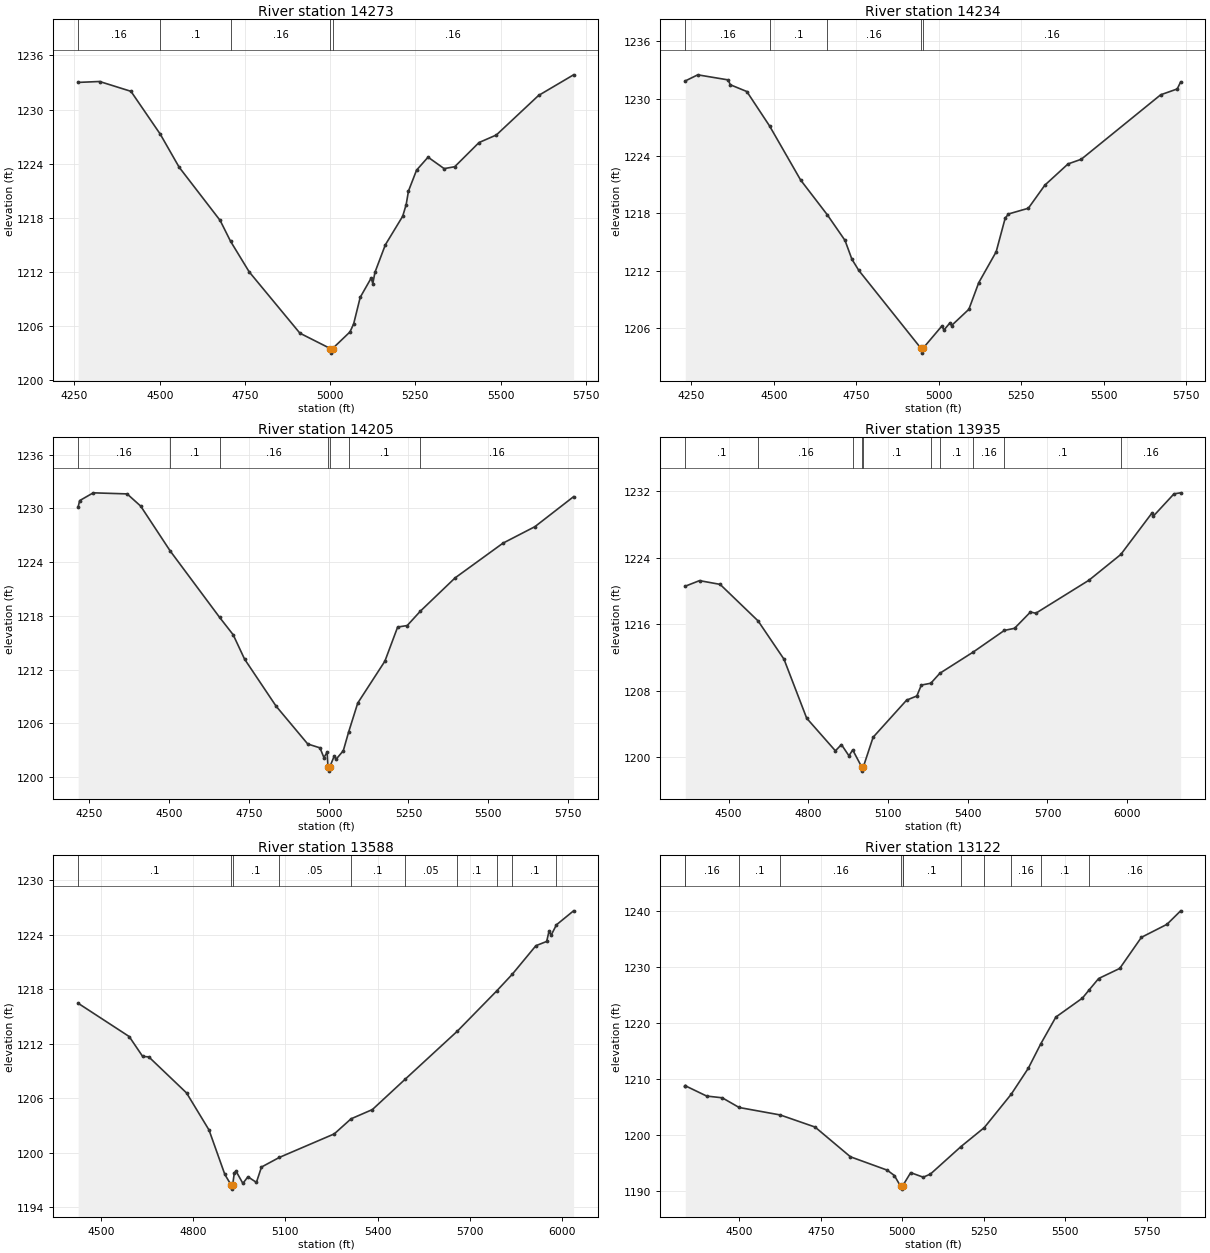
Type RM Length L Ch R = 1 ,14273   ,39,39,39
BEGIN DESCRIPTION:
HARDIN RUSSELL CREEK 31.0
END DESCRIPTION:
XS GIS Cut Line= 4
      2907088.52     10086832.13      2906557.29     10086358.19
      2906447.92     10086312.62       2905835.9     10086428.51
#Sta/Elev= 30
  4260.9 1233.01  4323.7 1233.11  4415.7 1232.02  4501.7 1227.27    4557 1223.61
  4677.4  1217.7  4707.8  1215.4  4762.6    1212  4911.4  1205.2    5001 1203.49
  5003.8 1202.99    5007 1203.49  5058.2 1205.34    5069 1206.23  5088.3 1209.18
  5120.2  1211.3  5125.3 1210.71  5131.5 1211.95    5162    1215  5212.9 1218.17
  5223.1 1219.46  5229.9 1220.97  5253.6 1223.28  5287.3 1224.72  5334.5 1223.45
  5365.5 1223.66  5436.8 1226.34  5487.7 1227.18  5611.4 1231.56  5714.2 1233.85
#Mann= 5 ,-1 , 0
  4260.9     .16       0  4501.7      .1       0  4707.8     .16       0
    5001     .07       0    5007     .16       0
Bank Sta=5001,5007
XS Rating Curve= 0 ,0
Exp/Cntr=0.3,0.1

Type RM Length L Ch R = 1 ,14234   ,29,29,29
BEGIN DESCRIPTION:
HARDIN RUSSELL CREEK 30.0
END DESCRIPTION:
XS GIS Cut Line= 4
      2907128.91     10086816.53      2906588.54     10086329.54
      2906459.63     10086273.56      2905828.15     10086319.13
#Sta/Elev= 30
  4231.9 1231.87  4269.8 1232.51  4361.7 1231.98  4368.5 1231.47  4418.5 1230.76
  4487.3 1227.16  4581.4  1221.5  4662.2 1217.86    4716 1215.17  4736.9  1213.2
  4757.8 1212.03  4946.2 1203.87  4948.9 1203.37  4952.2 1203.87    5010 1206.23
  5015.5 1205.78  5033.5 1206.52  5038.9 1206.26  5091.3 1207.96  5121.1 1210.74
    5174 1213.98  5201.3  1217.5  5211.3 1217.94  5271.5 1218.54  5321.6 1220.96
  5391.8 1223.18  5431.9 1223.67  5672.5 1230.42  5722.6 1231.03    5733 1231.77
#Mann= 5 ,-1 , 0
  4231.9     .16       0  4487.3      .1       0  4662.2     .16       0
  4946.2     .07       0  4952.2     .16       0
Bank Sta=4946.2,4952.2
XS Rating Curve= 0 ,0
Exp/Cntr=0.3,0.1

Type RM Length L Ch R = 1 ,14205   ,270,270,270
BEGIN DESCRIPTION:
HARDIN RUSSELL CREEK 29.0
END DESCRIPTION:
XS GIS Cut Line= 4
      2907153.64      10086804.8      2906614.58     10086312.62
      2906480.47     10086247.51      2905807.29     10086263.14
#Sta/Elev= 30
  4214.9 1230.18  4219.5 1230.87  4262.1 1231.74  4368.2 1231.62  4410.7 1230.26
  4503.2 1225.25  4658.1 1217.83  4700.6 1215.89  4736.3 1213.17    4835 1207.92
  4934.3 1203.69  4972.5 1203.26    4985 1202.17  4995.1 1202.79  4997.6 1201.16
  5000.4 1200.66  5003.6 1201.16  5017.6 1202.37  5023.2 1201.99  5045.7 1202.94
    5062 1204.98  5090.9 1208.26    5176 1212.94    5216 1216.75    5246 1216.92
  5287.6 1218.54    5396 1222.24  5546.1 1226.12  5646.1 1227.96  5767.3 1231.31
#Mann= 7 ,-1 , 0
  4214.9     .16       0  4503.2      .1       0  4658.1     .16       0
  4997.6     .07       0  5003.6     .16       0    5062      .1       0
  5287.6     .16       0
Bank Sta=4997.6,5003.6
XS Rating Curve= 0 ,0
Exp/Cntr=0.3,0.1

Type RM Length L Ch R = 1 ,13935   ,347,347,347
BEGIN DESCRIPTION:
Mapping XS d879a835
END DESCRIPTION:
XS GIS Cut Line= 4
      2907209.17     10086438.46      2906901.04     10086152.03
      2906471.35     10085948.03      2905503.45     10085926.33
#Sta/Elev= 30
  4336.7 1220.56  4390.3 1221.23  4467.9 1220.78  4610.8 1216.39  4708.3 1211.79
  4793.7  1204.7  4901.8 1200.78  4924.5 1201.53  4952.8 1200.18  4966.9 1200.89
  5000.8 1198.84  5003.5 1198.34  5006.8 1198.84  5043.7 1202.41  5169.8 1206.87
  5208.3 1207.37  5225.2 1208.68  5260.9  1208.9    5295  1210.1  5420.1 1212.64
  5537.8 1215.25    5576  1215.5    5636 1217.46    5656 1217.31  5856.1 1221.28
  5975.9 1224.37  6092.7 1229.33  6097.7 1228.95  6176.2 1231.66  6201.2 1231.78
#Mann= 10 ,-1 , 0
  4336.7      .1       0  4610.8     .16       0  4966.9      .1       0
  5000.8     .07       0  5006.8      .1       0  5260.9     .05       0
    5295      .1       0  5420.1     .16       0  5537.8      .1       0
  5975.9     .16       0
Bank Sta=5000.8,5006.8
XS Rating Curve= 0 ,0
Exp/Cntr=0.3,0.1

Type RM Length L Ch R = 1 ,13588   ,466,466,466
BEGIN DESCRIPTION:
HARDIN RUSSELL CREEK 28.0
END DESCRIPTION:
XS GIS Cut Line= 4
      2907174.03     10086179.45      2907055.99     10085856.56
      2906555.99     10085592.67      2906094.21     10085064.93
#Sta/Elev= 30
  4426.8 1216.46  4592.6  1212.8  4636.4 1210.61  4656.3 1210.56  4779.1 1206.59
  4852.1 1202.51  4903.5 1197.62  4923.1  1196.5  4925.8    1196  4929.1  1196.5
  4934.5 1197.82  4940.2 1197.96  4962.2 1196.63  4978.6 1197.36  5006.2 1196.74
  5022.6 1198.43  5080.7 1199.49  5259.2 1202.08  5313.8 1203.74  5383.2 1204.76
  5489.4 1208.09  5659.3 1213.39  5786.7  1217.8    5838 1219.66  5914.7  1222.8
  5949.8 1223.27  5957.4  1224.4  5964.1 1223.95  5981.5  1225.1  6037.2 1226.64
#Mann= 10 ,-1 , 0
  4426.8      .1       0  4923.1     .07       0  4929.1      .1       0
  5080.7     .05       0  5313.8      .1       0  5489.4     .05       0
  5659.3      .1       0  5786.7     .05       0    5838      .1       0
  5981.5     .16       0
Bank Sta=4923.1,4929.1
XS Rating Curve= 0 ,0
Exp/Cntr=0.3,0.1

Type RM Length L Ch R = 1 ,13122   ,750,750,750
BEGIN DESCRIPTION:
HARDIN RUSSELL CREEK 27.0
END DESCRIPTION:
XS GIS Cut Line= 4
      2907288.62     10085901.69      2907170.57     10085394.76
      2906875.43     10085241.98      2906510.87     10084682.99
#Sta/Elev= 30
  4333.6  1208.8    4334 1208.78  4399.3 1206.95  4447.1 1206.64    4499 1204.91
  4624.9 1203.58  4731.9 1201.42  4840.5 1196.11  4953.2 1193.73  4975.3 1192.77
  4994.5 1190.84  4997.2 1190.34  5000.5 1190.84  5001.7 1191.02  5025.4 1193.28
  5063.9 1192.47    5086 1193.03  5179.8 1197.94  5251.2 1201.32  5333.9 1207.28
  5386.4 1211.92  5423.9  1216.2  5470.9 1221.05  5552.3 1224.43  5573.5 1225.93
  5602.2 1227.93  5666.9 1229.73  5733.4 1235.28  5811.8  1237.6  5853.8 1240.01
#Mann= 12 ,-1 , 0
  4333.6      .1       0    4334     .16       0    4499      .1       0
  4624.9     .16       0  4994.5     .07       0  5000.5     .16       0
  5001.7      .1       0  5179.8     .16       0  5251.2      .1       0
  5333.9     .16       0  5423.9      .1       0  5573.5     .16       0
Bank Sta=4994.5,5000.5
XS Rating Curve= 0 ,0
Exp/Cntr=0.3,0.1

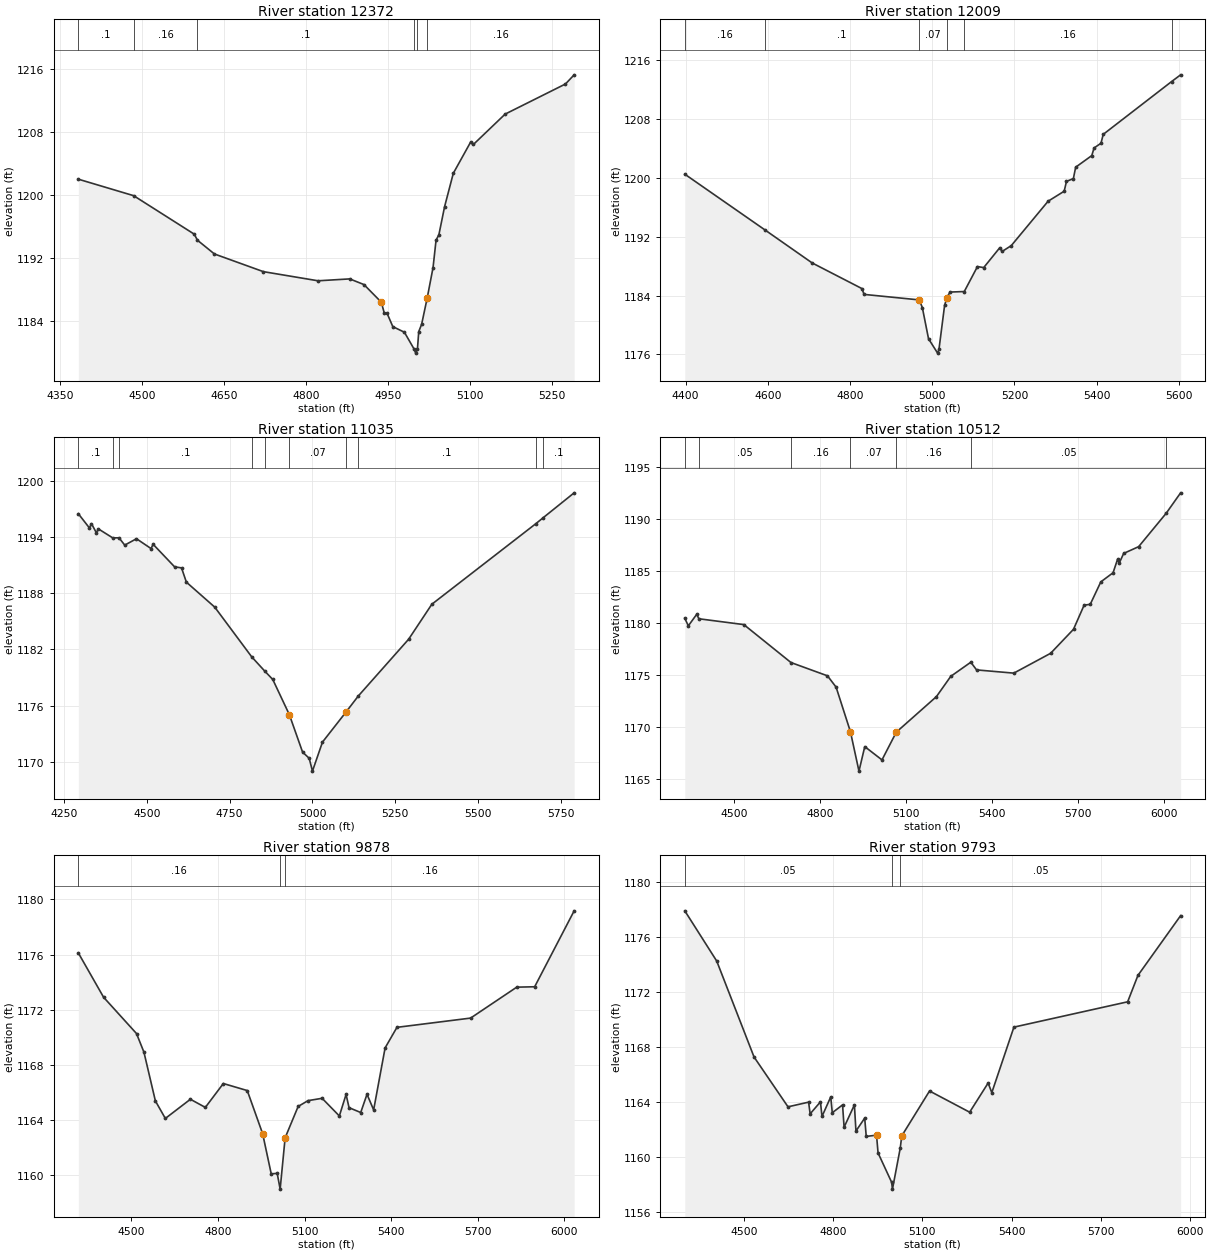
Type RM Length L Ch R = 1 ,12372   ,363,363,363
BEGIN DESCRIPTION:
HARDIN RUSSELL CREEK 26.0
END DESCRIPTION:
XS GIS Cut Line= 2
      2907396.27     10085610.03       2907683.4     10084748.63
#Sta/Elev= 30
  4383.1 1201.97  4484.4 1199.88  4595.4    1195  4601.3 1194.23  4632.3 1192.49
  4721.9 1190.25  4822.1 1189.09  4880.1 1189.33  4906.2 1188.61  4937.9 1186.38
  4943.3 1185.02  4948.6 1184.95    4959 1183.28  4980.2 1182.57  4998.1 1180.42
  5000.9 1179.92  5004.1 1180.42  5006.5 1182.65  5011.8 1183.58  5021.9 1186.88
  5032.7 1190.77  5038.2 1194.24  5043.4 1194.93  5053.8 1198.48  5069.8 1202.72
  5101.4 1206.66  5106.7 1206.38  5164.7 1210.22  5275.2 1214.04  5291.1  1215.2
#Mann= 6 ,-1 , 0
  4383.1      .1       0  4484.4     .16       0  4601.3      .1       0
  4998.1     .07       0  5004.1      .1       0  5021.9     .16       0
Bank Sta=4937.9,5021.9
XS Rating Curve= 0 ,0
Exp/Cntr=0.3,0.1

Type RM Length L Ch R = 1 ,12009   ,974,974,974
BEGIN DESCRIPTION:
HARDIN RUSSELL CREEK 25.0
END DESCRIPTION:
XS GIS Cut Line= 2
      2907649.73     10085721.17      2908187.94     10084641.26
#Sta/Elev= 30
  4397.9 1200.51  4592.3 1192.95  4707.9 1188.43  4828.7 1184.95  4834.3 1184.15
  4968.6  1183.4    4976 1182.35    4991 1178.12  5013.1 1176.16  5016.4 1176.66
  5030.2 1182.69  5035.7 1183.66  5043.1 1184.47    5078 1184.54  5110.1 1187.94
  5125.3  1187.8  5164.5 1190.51    5170 1189.99  5192.4 1190.79    5282 1196.83
  5321.1 1198.19  5326.7 1199.53  5343.5 1199.91  5349.1 1201.46  5388.3 1203.04
  5393.9 1204.08  5410.7 1204.72  5416.2 1205.93  5582.7 1213.12  5604.5 1214.03
#Mann= 6 ,-1 , 0
  4397.9     .16       0  4592.3      .1       0  4968.6     .07       0
  5035.7      .1       0    5078     .16       0  5582.7      .1       0
Bank Sta=4968.6,5035.7
XS Rating Curve= 0 ,0
Exp/Cntr=0.3,0.1

Type RM Length L Ch R = 1 ,11035   ,523,523,523
BEGIN DESCRIPTION:
HARDIN RUSSELL CREEK 23.0
END DESCRIPTION:
XS GIS Cut Line= 4
      2908170.57     10086231.57      2908621.96      10085901.7
      2908646.27      10085252.4      2908542.79     10084983.35
#Sta/Elev= 30
  4293.1 1196.47  4326.6 1194.95  4332.8 1195.41  4347.5 1194.44  4353.7 1194.85
    4397 1193.89  4415.9  1193.9  4433.2 1193.12  4468.7  1193.8  4512.7 1192.75
  4518.9 1193.21  4583.8  1190.8  4604.7 1190.69  4619.3 1189.17    4705  1186.5
  4816.5  1181.2  4855.3  1179.7  4880.2 1178.78  4930.2 1175.03  4970.2 1171.03
  4990.2 1170.37    5000    1169  5030.3  1172.1  5100.3 1175.26  5138.5 1177.02
  5290.5 1183.08  5360.5 1186.81  5673.9 1195.39  5696.2 1196.03  5790.2  1198.7
#Mann= 10 ,-1 , 0
  4293.1      .1       0    4397     .05       0  4415.9      .1       0
  4816.5     .05       0  4855.3      .1       0  4930.2     .07       0
  5100.3     .16       0  5138.5      .1       0  5673.9     .16       0
  5696.2      .1       0
Bank Sta=4930.2,5100.3
XS Rating Curve= 0 ,0
Exp/Cntr=0.3,0.1

Type RM Length L Ch R = 1 ,10512   ,634,634,634
BEGIN DESCRIPTION:
HARDIN RUSSELL CREEK 22.0
END DESCRIPTION:
XS GIS Cut Line= 4
      2908944.86      10086394.8      2909153.21     10085957.26
       2909128.9      10085252.4      2908851.63     10084787.96
#Sta/Elev= 30
  4328.4 1180.45  4340.7 1179.72    4370 1180.83  4377.7  1180.4  4534.5 1179.84
    4699 1176.19  4826.5 1174.91  4856.6 1173.82  4906.6 1169.53  4936.4 1165.74
  4956.6  1168.1  5016.7 1166.82  5066.7 1169.49  5206.8 1172.91  5256.8 1174.86
  5326.8 1176.22  5346.9 1175.48  5476.9 1175.17  5605.5 1177.08  5685.3 1179.39
  5722.3 1181.71  5743.7 1181.79  5780.6 1183.95  5823.4 1184.83    5839 1186.12
  5844.8 1185.75  5860.4 1186.69  5912.7 1187.34  6008.7 1190.55  6059.2 1192.52
#Mann= 7 ,-1 , 0
  4328.4      .1       0  4377.7     .05       0    4699     .16       0
  4906.6     .07       0  5066.7     .16       0  5326.8     .05       0
  6008.7      .1       0
Bank Sta=4906.6,5066.7
XS Rating Curve= 0 ,0
Exp/Cntr=0.3,0.1

Type RM Length L Ch R = 1 ,9878    ,85,85,85
BEGIN DESCRIPTION:
HARDIN RUSSELL CREEK 21.0
END DESCRIPTION:
XS GIS Cut Line= 2
      2909913.62     10086228.07      2909458.75      10084571.8
#Sta/Elev= 30
  4315.9 1176.12  4403.4 1172.91  4517.4 1170.28  4543.2 1168.93  4582.8  1165.4
  4617.3 1164.13  4704.1 1165.52  4755.9 1164.93  4818.2 1166.66  4901.1 1166.15
  4954.3 1163.03  4984.1 1160.12  5004.8 1160.15    5015 1159.01  5032.3 1162.73
  5077.4    1165  5111.6 1165.42  5160.4 1165.59  5220.1 1164.31  5243.4 1165.87
  5253.7 1164.91  5294.1 1164.56  5315.9 1165.88  5338.9 1164.75  5378.6 1169.24
  5419.6 1170.73  5674.8  1171.4  5834.5 1173.64  5896.7 1173.67  6033.5 1179.17
#Mann= 3 ,-1 , 0
  4315.9     .16       0    5015     .07       0  5032.3     .16       0
Bank Sta=4954.3,5032.3
XS Rating Curve= 0 ,0
Exp/Cntr=0.3,0.1

Type RM Length L Ch R = 1 ,9793    ,132,132,132
BEGIN DESCRIPTION:
HARDIN RUSSELL CREEK 20.0
END DESCRIPTION:
XS GIS Cut Line= 2
      2909993.49     10086207.27      2909555.99     10084599.64
#Sta/Elev= 30
  4302.1 1177.87  4409.4 1174.22  4534.8 1167.25  4648.9 1163.63  4718.1 1163.97
  4723.3 1163.12  4757.9 1163.99  4763.1 1162.93  4792.5 1164.35  4797.7  1163.2
  4832.2 1163.77  4837.4 1162.15    4872 1163.77  4877.2 1161.87  4906.6 1162.81
  4911.8 1161.48  4946.4 1161.57  4951.5 1160.28  4997.1 1158.15  4999.9 1157.65
  5025.9 1160.61  5031.2 1161.52  5124.5 1164.78  5259.3 1163.24  5321.4 1165.36
  5333.7 1164.66    5408 1169.42  5790.2 1171.26  5824.8 1173.18  5968.2 1177.52
#Mann= 3 ,-1 , 0
  4302.1     .05       0  4997.1     .07       0  5025.9     .05       0
Bank Sta=4946.4,5031.2
XS Rating Curve= 0 ,0
Exp/Cntr=0.3,0.1

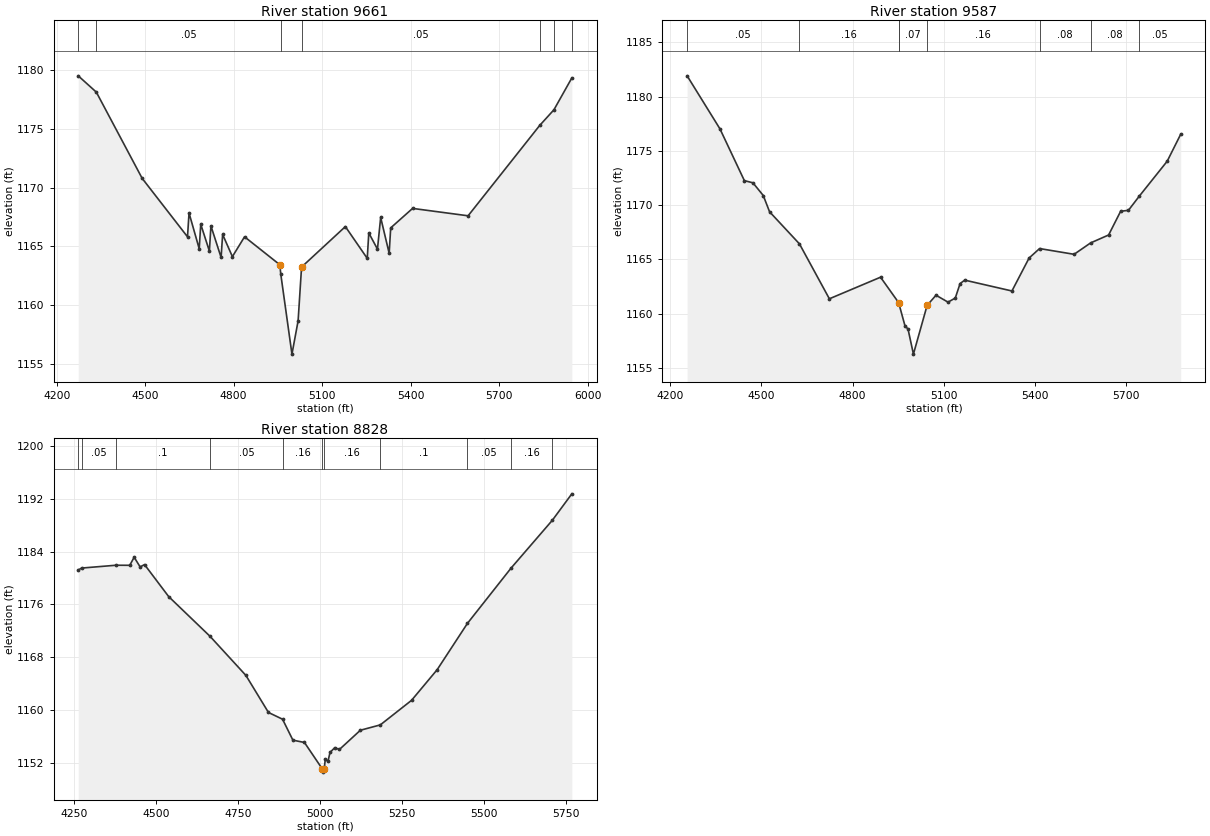
Type RM Length L Ch R = 1 ,9661    ,74,74,74
BEGIN DESCRIPTION:
HARDIN RUSSELL CREEK 19.0
END DESCRIPTION:
XS GIS Cut Line= 2
      2910121.96     10086182.94      2909681.04     10084568.57
#Sta/Elev= 30
    4273 1179.53  4334.4 1178.14  4489.8 1170.79  4643.5 1165.81  4648.7 1167.84
  4683.2 1164.79  4688.4 1166.88  4717.7 1164.59  4722.9 1166.74  4757.4 1164.05
  4762.6 1166.01  4795.7 1164.12  4836.9 1165.81  4956.4 1163.43 4959.82 1162.61
  4997.6 1155.81  5018.5 1158.65  5030.2 1163.23  5178.7 1166.68  5252.9 1163.97
  5258.1 1166.14  5287.5 1164.76  5298.4 1167.46  5327.2  1164.4  5332.4 1166.57
  5406.6 1168.23  5594.8  1167.6  5837.5  1175.3  5885.9 1176.64  5946.5 1179.35
#Mann= 7 ,-1 , 0
    4273     .16       0  4334.4     .05       0 4959.82     .07       0
  5030.2     .05       0  5837.5     .08       0  5885.9     .05       0
  5946.5     .08       0
Bank Sta=4956.4,5030.2
XS Rating Curve= 0 ,0
Exp/Cntr=0.3,0.1

Type RM Length L Ch R = 1 ,9587    ,759,759,759
BEGIN DESCRIPTION:
HARDIN RUSSELL CREEK 18.0
END DESCRIPTION:
XS GIS Cut Line= 2
      2910191.41     10086165.62      2909761.21     10084597.46
#Sta/Elev= 30
    4255 1181.92  4363.2 1177.03  4443.6 1172.26  4471.8 1172.06  4505.8 1170.89
  4526.6 1169.39  4625.1 1166.43  4723.6 1161.37  4892.2 1163.36  4951.7 1161.02
  4972.5  1158.9  4982.8 1158.57  5000.5 1156.27  5045.6 1160.76  5074.9  1161.7
  5114.5 1161.06  5138.4 1161.44  5154.2 1162.77  5169.5 1163.09    5325 1162.09
  5381.6 1165.13  5416.1    1166  5529.8 1165.47  5584.2 1166.52  5643.5 1167.25
  5683.2 1169.44  5708.7 1169.52    5744 1170.81  5836.5 1174.05  5881.1 1176.54
#Mann= 8 ,-1 , 0
    4255     .05       0  4625.1     .16       0  4951.7     .05       0
  4951.7     .07       0  5045.6     .16       0  5416.1     .08       0
  5584.2     .08       0    5744     .05       0
Bank Sta=4951.7,5045.6
XS Rating Curve= 0 ,0
Exp/Cntr=0.3,0.1

Type RM Length L Ch R = 1 ,8828    ,575,575,575
BEGIN DESCRIPTION:
Mapping XS de018b57
END DESCRIPTION:
XS GIS Cut Line= 3
       2910733.5     10085565.69      2910550.11     10085011.05
      2909959.67     10084304.31
#Sta/Elev= 30
  4263.1 1181.21  4273.2 1181.51  4378.3 1181.94  4420.2 1181.93  4433.7 1183.15
  4451.9 1181.68  4465.3 1182.04    4539 1177.19  4665.2 1171.17  4774.4 1165.26
  4843.2 1159.65  4886.1 1158.63  4917.7 1155.46  4952.9 1155.11  5007.1 1151.12
  5009.9 1150.62  5013.1 1151.12  5016.6 1152.63  5024.4 1152.23    5031 1153.61
  5045.3 1154.32  5059.6 1154.05  5123.4 1156.96  5184.2 1157.77  5279.5 1161.49
  5357.6 1166.13  5449.9 1173.14  5582.8  1181.5  5708.8 1188.75  5768.2 1192.75
#Mann= 11 ,-1 , 0
  4263.1      .1       0  4273.2     .05       0  4378.3      .1       0
  4665.2     .05       0  4886.1     .16       0  5007.1     .07       0
  5013.1     .16       0  5184.2      .1       0  5449.9     .05       0
  5582.8     .16       0  5708.8      .1       0
Bank Sta=5007.1,5013.1
XS Rating Curve= 0 ,0
Exp/Cntr=0.3,0.1