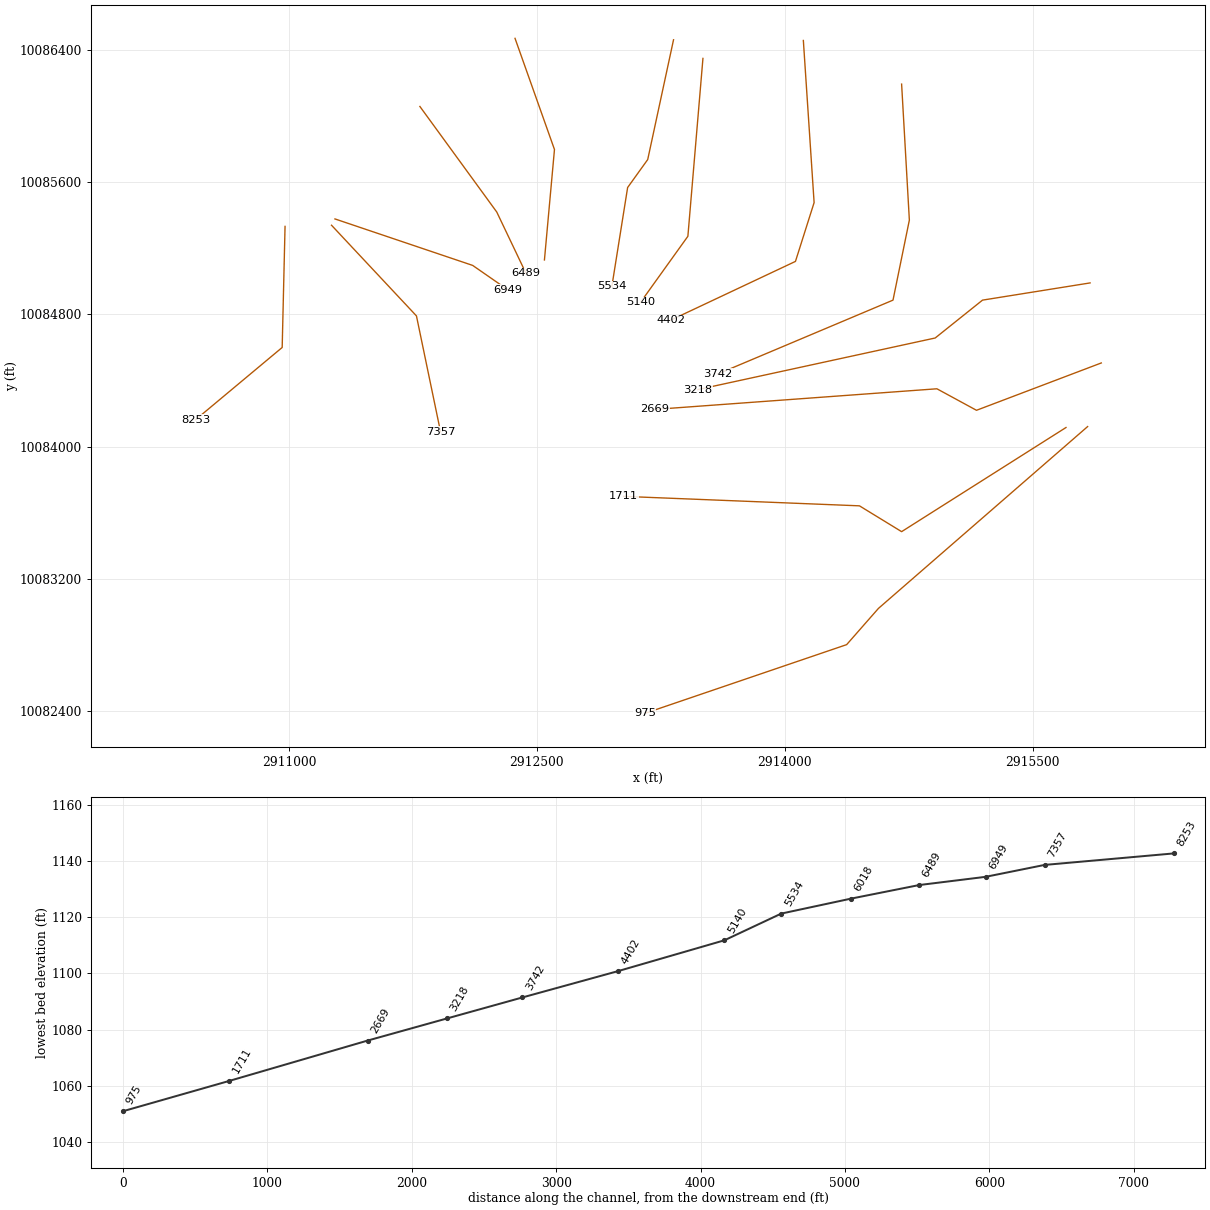
HEC-RAS study HARDIN RUSSELL CREEK.prj: HARDIN RUSSELL CREEK Base Level Engineering

--- HARDIN RUSSELL CREEK.g01 (geometry) --- (continued)

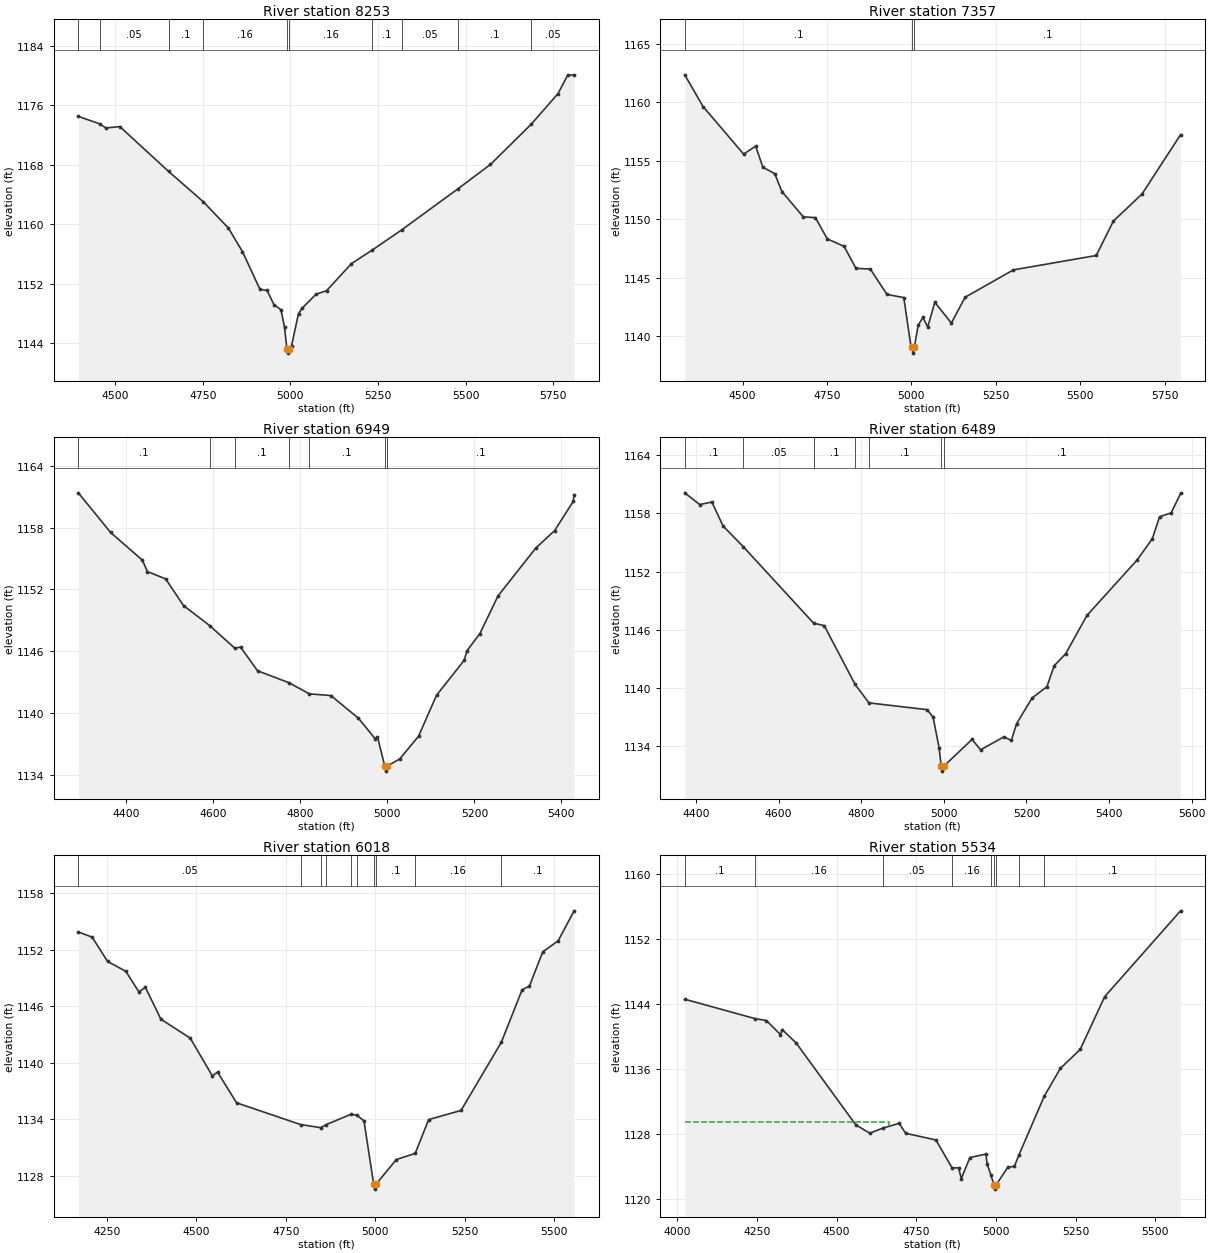
Type RM Length L Ch R = 1 ,8253    ,896,896,896
BEGIN DESCRIPTION:
HARDIN RUSSELL CREEK 17.0
END DESCRIPTION:
XS GIS Cut Line= 3
      2910976.13     10085332.22      2910958.77     10084599.62
      2910434.44      10084162.1
#Sta/Elev= 30
  4394.4 1174.52  4455.2 1173.53  4472.9 1172.97  4512.9 1173.15  4652.1 1167.12
  4750.6 1163.06    4823 1159.49    4863 1156.33    4913 1151.25  4933.4 1151.09
    4953 1149.19    4973  1148.5  4983.1 1146.16  4990.1 1143.16  4992.8 1142.66
  4996.1 1143.16  5003.1 1143.64  5023.1 1147.98  5033.1 1148.69  5073.1 1150.59
  5103.1 1151.06  5174.3 1154.71  5232.3 1156.49  5317.2 1159.23    5479  1164.8
  5571.3 1168.06  5687.6 1173.47  5763.9 1177.58  5791.8 1180.08  5810.1 1180.12
#Mann= 10 ,-1 , 0
  4394.4      .1       0  4455.2     .05       0  4652.1      .1       0
  4750.6     .16       0  4990.1     .07       0  4996.1     .16       0
  5232.3      .1       0  5317.2     .05       0    5479      .1       0
  5687.6     .05       0
Bank Sta=4990.1,4996.1
XS Rating Curve= 0 ,0
Exp/Cntr=0.3,0.1

Type RM Length L Ch R = 1 ,7357    ,408,408,408
BEGIN DESCRIPTION:
HARDIN RUSSELL CREEK 15.0
END DESCRIPTION:
XS GIS Cut Line= 3
      2911257.36     10085339.22      2911771.27     10084790.59
       2911917.1     10084089.21
#Sta/Elev= 30
  4328.8 1162.36  4382.9 1159.65  4503.1 1155.58  4538.8 1156.26  4559.8 1154.47
  4595.4  1153.9  4616.4 1152.38  4679.9 1150.21  4715.6 1150.15  4750.8 1148.33
  4800.6 1147.69  4835.8 1145.81  4878.2 1145.75  4927.6 1143.58  4977.4 1143.31
  4998.4 1139.17  5002.7 1139.06  5005.5 1138.56  5008.7 1139.06  5019.9 1140.95
  5034.1 1141.61  5048.2 1140.79  5069.2 1142.91  5118.2 1141.13    5159 1143.34
    5302 1145.68  5547.2 1146.91  5598.2 1149.86  5682.9 1152.17  5796.9 1157.24
#Mann= 3 ,-1 , 0
  4328.8      .1       0  5002.7     .07       0  5008.7      .1       0
Bank Sta=5002.7,5008.7
XS Rating Curve= 0 ,0
Exp/Cntr=0.3,0.1

Type RM Length L Ch R = 1 ,6949    ,460,460,460
BEGIN DESCRIPTION:
HARDIN RUSSELL CREEK 14.0
END DESCRIPTION:
XS GIS Cut Line= 3
      2911278.23     10085377.39      2912111.54     10085096.15
      2912325.44      10084947.8
#Sta/Elev= 30
  4289.4 1161.39  4363.5 1157.54  4436.8 1154.84    4448 1153.74  4490.2 1153.02
  4531.2 1150.43  4591.4 1148.48  4648.9 1146.29  4662.4 1146.39  4701.3 1144.09
  4773.3 1142.93  4820.8 1141.84  4870.1 1141.68  4933.4 1139.47  4971.8 1137.48
  4977.1 1137.67  4993.8 1134.83  4996.5 1134.33  4999.8 1134.83  5028.4 1135.52
  5071.5 1137.72  5112.9 1141.71  5176.6 1145.11  5182.6 1146.02  5212.4 1147.69
  5254.3 1151.37  5340.7    1156  5384.2 1157.71  5427.2 1160.56  5429.2 1161.21
#Mann= 7 ,-1 , 0
  4289.4      .1       0  4591.4     .16       0  4648.9      .1       0
  4773.3     .16       0  4820.8      .1       0  4993.8     .07       0
  4999.8      .1       0
Bank Sta=4993.8,4999.8
XS Rating Curve= 0 ,0
Exp/Cntr=0.3,0.1

Type RM Length L Ch R = 1 ,6489    ,471,471,471
BEGIN DESCRIPTION:
HARDIN RUSSELL CREEK 13.0
END DESCRIPTION:
XS GIS Cut Line= 3
      2911792.09     10086057.97      2912257.38     10085419.06
      2912433.66     10085049.21
#Sta/Elev= 30
  4373.1 1160.12  4409.3 1158.91  4438.7 1159.17  4465.8  1156.7  4514.8 1154.56
  4685.1 1146.67  4710.7 1146.42  4785.5 1140.35    4819 1138.45  4959.8 1137.75
  4974.2 1136.98  4988.8 1133.81  4993.9 1131.91  4996.6 1131.41  4999.9 1131.91
  5068.4 1134.68  5089.3 1133.61  5145.7 1134.95  5163.5 1134.57  5176.3  1136.3
  5213.7 1138.95  5249.9 1140.13  5267.1 1142.27  5295.3 1143.53  5346.6 1147.47
  5468.5 1153.21  5505.1  1155.4  5522.3 1157.65  5550.5 1158.05  5573.2 1160.06
#Mann= 7 ,-1 , 0
  4373.1      .1       0  4514.8     .05       0  4685.1      .1       0
  4785.5     .05       0    4819      .1       0  4993.9     .07       0
  4999.9      .1       0
Bank Sta=4993.9,4999.9
XS Rating Curve= 0 ,0
Exp/Cntr=0.3,0.1

Type RM Length L Ch R = 1 ,6018    ,484,484,484
BEGIN DESCRIPTION:
HARDIN RUSSELL CREEK 12.0
END DESCRIPTION:
XS GIS Cut Line= 3
      2912367.79     10086470.29      2912606.51     10085797.54
      2912545.75     10085129.15
#Sta/Elev= 30
  4170.6 1153.88  4209.4 1153.32  4252.3 1150.75  4303.4  1149.7  4339.6 1147.52
  4357.9    1148  4401.3 1144.62  4483.3 1142.61    4545  1138.6  4559.6    1139
  4612.6 1135.75  4791.6 1133.44  4847.8 1133.11  4863.2 1133.44  4931.4 1134.52
  4948.2 1134.45  4968.6 1133.83  4995.7 1127.09  4998.5 1126.59  5001.7 1127.09
    5059 1129.73  5111.6 1130.38  5149.3 1133.97  5239.7 1134.94  5352.2 1142.17
  5410.4 1147.75  5430.5 1148.12    5468 1151.77  5510.8 1152.93  5555.6 1156.12
#Mann= 10 ,-1 , 0
  4170.6     .05       0  4791.6      .1       0  4847.8     .05       0
  4863.2     .16       0  4931.4     .05       0  4948.2      .1       0
  4995.7     .07       0  5001.7      .1       0  5111.6     .16       0
  5352.2      .1       0
Bank Sta=4995.7,5001.7
XS Rating Curve= 0 ,0
Exp/Cntr=0.3,0.1

Type RM Length L Ch R = 1 ,5534    ,394,394,394
BEGIN DESCRIPTION:
HARDIN RUSSELL CREEK 11.0
END DESCRIPTION:
XS GIS Cut Line= 4
      2913326.99     10086461.58      2913170.75     10085736.77
      2913049.22      10085567.5      2912953.74      10084968.6
#Sta/Elev= 30
  4023.2 1144.59  4242.7 1142.22  4279.5 1141.97  4323.7 1140.25  4328.8 1140.87
    4373 1139.21    4560 1129.16  4604.1 1128.13  4644.1 1128.75  4696.2 1129.34
  4716.6 1128.12  4811.5  1127.3  4862.2 1123.88  4882.7 1123.87  4891.3 1122.56
  4918.3 1125.14  4968.6 1125.56  4972.3 1124.35  4984.3 1122.98  4994.1 1121.76
  4996.9 1121.26  5000.1 1121.76  5037.6 1123.97  5057.9 1124.05  5071.9 1125.44
  5151.8 1132.69  5202.4  1136.1  5264.5 1138.42  5341.4 1144.91  5579.5 1155.45
#Mann= 9 ,-1 , 0
  4023.2      .1       0  4242.7     .16       0  4644.1     .05       0
  4862.2     .16       0  4984.3      .1       0  4994.1     .07       0
  5000.1      .1       0  5071.9     .16       0  5151.8      .1       0
#XS Ineff= 2 , 0
         4664.55 1129.51
Permanent Ineff=
       F       F
Bank Sta=4994.1,5000.1
XS Rating Curve= 0 ,0
Exp/Cntr=0.3,0.1

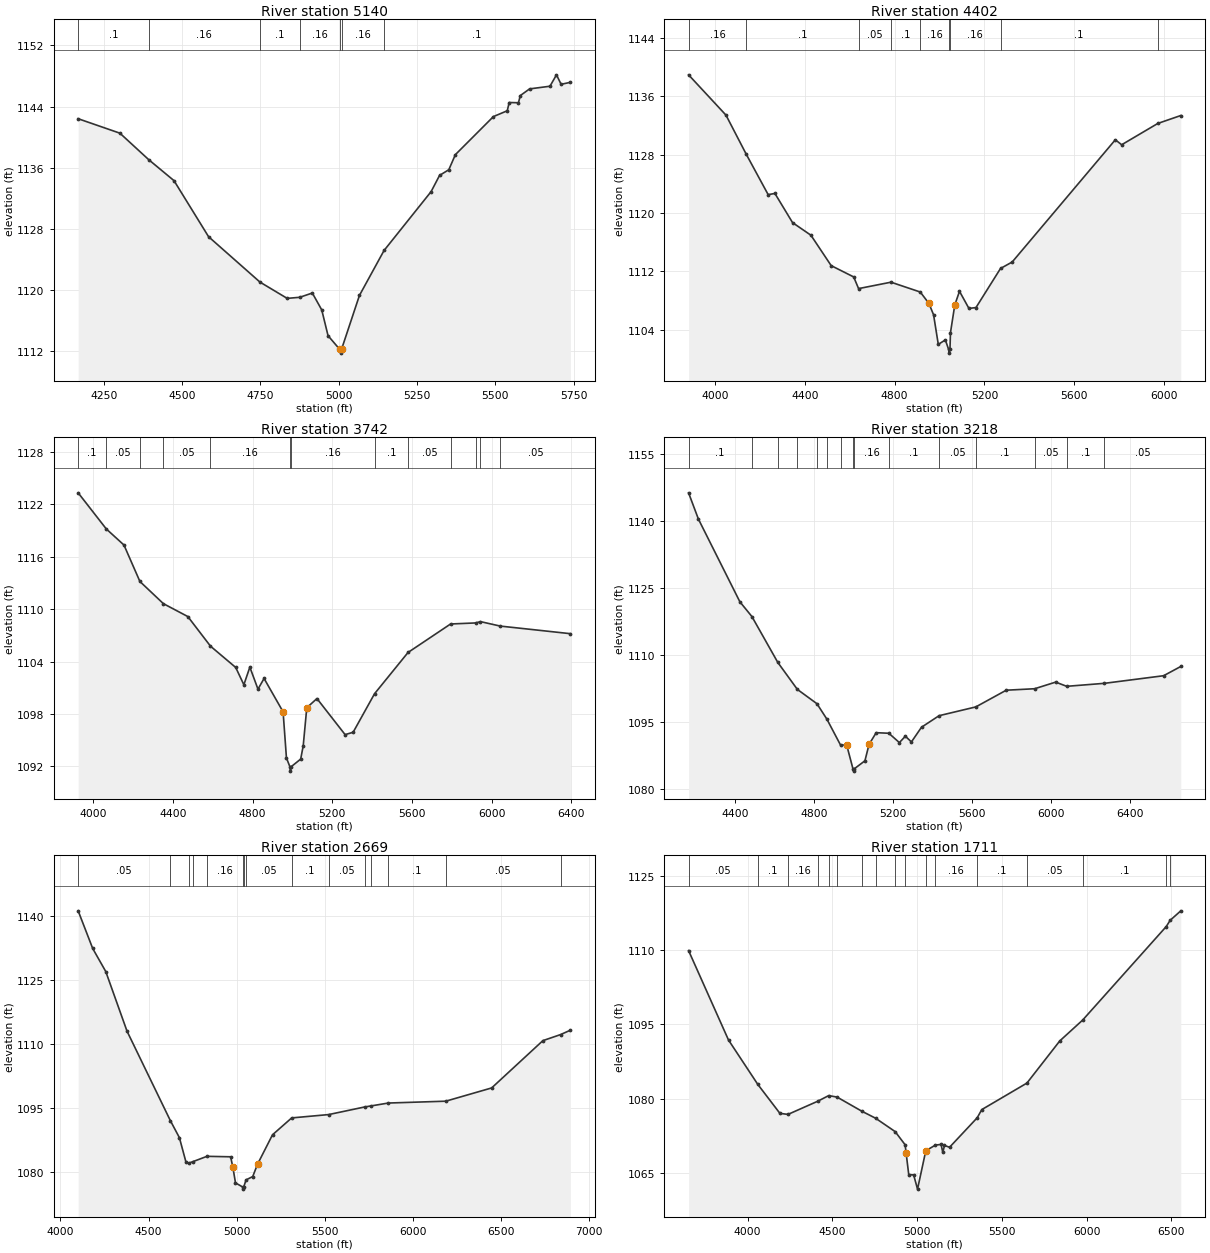
Type RM Length L Ch R = 1 ,5140    ,738,738,738
BEGIN DESCRIPTION:
HARDIN RUSSELL CREEK 10.0
END DESCRIPTION:
XS GIS Cut Line= 3
      2913504.95     10086348.78       2913413.8     10085272.36
      2913127.34     10084873.05
#Sta/Elev= 30
  4167.8 1142.41  4301.1 1140.52  4393.3 1137.05  4473.9 1134.31  4584.3 1126.98
  4748.3 1121.05  4835.2 1118.92  4875.3 1119.06  4915.5 1119.62  4945.6 1117.41
  4965.7 1114.04  5002.8 1112.26  5005.6 1111.76  5008.8 1112.26    5066 1119.31
  5144.5 1125.18  5294.8 1132.88  5321.8    1135  5351.3 1135.74  5372.2 1137.71
  5493.7 1142.69  5537.9 1143.45  5544.1 1144.53  5573.6  1144.5  5579.7 1145.44
  5609.2 1146.31  5674.3 1146.66  5695.1 1148.15  5709.9 1146.91  5739.5 1147.17
#Mann= 7 ,-1 , 0
  4167.8      .1       0  4393.3     .16       0  4748.3      .1       0
  4875.3     .16       0  5002.8     .07       0  5008.8     .16       0
  5144.5      .1       0
Bank Sta=5002.8,5008.8
XS Rating Curve= 0 ,0
Exp/Cntr=0.3,0.1

Type RM Length L Ch R = 1 ,4402    ,660,660,660
BEGIN DESCRIPTION:
HARDIN RUSSELL CREEK 8.0
END DESCRIPTION:
XS GIS Cut Line= 4
      2914112.59     10086457.24      2914177.69     10085476.35
      2914064.84     10085120.45      2913309.62     10084764.54
#Sta/Elev= 30
    3883 1138.95  4049.6 1133.42  4140.1 1128.04  4237.3 1122.52  4267.4 1122.68
  4345.9 1118.68  4427.7 1116.95  4517.9 1112.78  4618.1 1111.23  4639.8 1109.63
  4784.1 1110.51  4914.5 1109.16  4952.7 1107.61  4973.7 1106.04  4994.7 1101.98
  5026.2 1102.59  5040.7 1101.28  5043.4 1100.78  5046.7 1101.28  5048.9 1103.58
  5068.1 1107.38  5089.1 1109.26  5131.1 1106.91  5162.5 1107.03  5271.7 1112.39
  5323.8 1113.28  5782.8 1130.04  5811.1 1129.36  5971.8 1132.28  6074.3 1133.37
#Mann= 9 ,-1 , 0
    3883     .16       0  4140.1      .1       0  4639.8     .05       0
  4784.1      .1       0  4914.5     .16       0  5040.7     .07       0
  5046.7     .16       0  5271.7      .1       0  5971.8     .16       0
Bank Sta=4952.7,5068.1
XS Rating Curve= 0 ,0
Exp/Cntr=0.3,0.1

Type RM Length L Ch R = 1 ,3742    ,524,524,524
BEGIN DESCRIPTION:
HARDIN RUSSELL CREEK 7.0
END DESCRIPTION:
XS GIS Cut Line= 4
      2914707.21     10086193.33      2914754.08     10085370.45
      2914655.12     10084886.08      2913593.68     10084438.61
#Sta/Elev= 30
  3924.3 1123.32  4065.7 1119.18  4154.3 1117.34  4234.2 1113.17    4352 1110.63
  4474.8 1109.15  4588.5 1105.76  4715.2 1103.32    4756 1101.34    4786 1103.36
  4826.8 1100.84  4857.4 1102.06  4952.9 1098.24  4969.7 1092.96  4987.1 1091.95
  4989.9 1091.45  4993.1 1091.95  5041.2 1092.83  5053.9 1094.35  5071.8 1098.71
  5122.8 1099.76  5264.1 1095.63  5304.4  1095.9  5412.1 1100.32    5580 1105.04
  5793.5  1108.3  5919.2 1108.42  5943.6 1108.57  6042.8 1108.06  6394.8 1107.19
#Mann= 13 ,-1 , 0
  3924.3      .1       0  4065.7     .05       0  4234.2      .1       0
    4352     .05       0  4588.5     .16       0  4987.1     .07       0
  4993.1     .16       0  5412.1      .1       0    5580     .05       0
  5793.5      .1       0  5919.2     .05       0  5943.6      .1       0
  6042.8     .05       0
Bank Sta=4952.9,5071.8
XS Rating Curve= 0 ,0
Exp/Cntr=0.3,0.1

Type RM Length L Ch R = 1 ,3218    ,549,549,549
BEGIN DESCRIPTION:
HARDIN RUSSELL CREEK 6.0
END DESCRIPTION:
XS GIS Cut Line= 4
      2915847.82     10084990.24      2915196.79     10084886.08
      2914910.33     10084656.91      2913473.16     10084344.48
#Sta/Elev= 30
  4162.2 1146.21  4212.2 1140.33  4422.4 1121.84  4483.4 1118.54  4614.9 1108.27
  4714.1 1102.24  4813.4 1099.04  4863.8 1095.59  4933.7 1089.74    4964 1089.84
  4996.2 1084.46    4999 1083.96  5002.2 1084.46  5056.8 1086.27  5077.6 1089.93
  5113.9 1092.56  5178.1 1092.43  5231.6 1090.34  5261.9 1091.77  5292.6 1090.49
  5343.8 1093.78    5433 1096.36  5619.1 1098.32  5773.6 1102.06  5917.8 1102.39
  6024.3 1103.87  6080.4 1102.93  6271.7  1103.6  6571.8  1105.3  6659.1 1107.37
#Mann= 15 ,-1 , 0
  4162.2      .1       0  4483.4     .16       0  4614.9      .1       0
  4714.1     .05       0  4813.4     .16       0  4863.8      .1       0
  4933.7     .16       0  4996.2     .07       0  5002.2     .16       0
  5178.1      .1       0    5433     .05       0  5619.1      .1       0
  5917.8     .05       0  6080.4      .1       0  6271.7     .05       0
Bank Sta=4964,5077.6
XS Rating Curve= 0 ,0
Exp/Cntr=0.3,0.1

Type RM Length L Ch R = 1 ,2669    ,958,958,958
BEGIN DESCRIPTION:
HARDIN RUSSELL CREEK 5.0
END DESCRIPTION:
XS GIS Cut Line= 4
      2915915.56     10084505.88      2915160.33     10084219.41
      2914920.75     10084349.62      2913212.93     10084224.66
#Sta/Elev= 30
  4100.8 1141.17  4183.3 1132.37  4257.4 1126.98  4377.9 1113.05    4624 1092.11
  4675.2 1088.14  4712.9 1082.36  4727.8 1082.17  4749.6 1082.49  4831.7 1083.77
  4965.9 1083.66  4978.9 1081.16  4993.5 1077.56  5034.2  1076.6  5036.9  1076.1
  5040.2  1076.6  5053.4 1078.26  5091.3 1079.04  5118.9 1081.95  5203.6 1088.81
  5312.3 1092.75  5521.8 1093.53  5727.5 1095.32    5762 1095.55  5860.7 1096.23
  6186.3 1096.66  6446.9 1099.76  6737.6 1110.82  6837.6 1112.23  6893.6 1113.26
#Mann= 15 ,-1 , 0
  4100.8     .05       0    4624      .1       0  4727.8     .16       0
  4749.6      .1       0  4831.7     .16       0  5034.2     .07       0
  5040.2     .16       0  5053.4     .05       0  5312.3      .1       0
  5521.8     .05       0  5727.5      .1       0    5762     .05       0
  5860.7      .1       0  6186.3     .05       0  6837.6      .1       0
Bank Sta=4978.9,5118.9
XS Rating Curve= 0 ,0
Exp/Cntr=0.3,0.1

Type RM Length L Ch R = 1 ,1711    ,736,736,736
BEGIN DESCRIPTION:
HARDIN RUSSELL CREEK 3.0
END DESCRIPTION:
XS GIS Cut Line= 4
      2915701.97     10084115.23       2914707.2     10083485.04
        2914452.     10083641.29      2913024.87     10083698.58
#Sta/Elev= 30
  3651.2  1109.9  3886.9 1091.85  4059.9 1082.89  4190.3 1077.05    4238 1076.84
  4413.7  1079.5    4478 1080.63  4527.4 1080.34    4675 1077.46  4754.9 1076.07
  4870.4 1073.37  4929.3 1070.71  4935.2 1069.05  4950.6  1064.7  4979.7 1064.62
  5002.5 1061.76  5051.2 1069.49    5108 1070.65  5141.6 1070.78  5151.6 1069.16
  5161.6 1070.57  5191.6 1070.21  5354.7 1076.16  5381.8 1077.81  5648.1 1083.16
  5842.1 1091.67  5977.2 1095.88  6470.4 1114.75  6493.6 1116.01  6556.3 1117.92
#Mann= 17 ,-1 , 0
  3651.2     .05       0  4059.9      .1       0    4238     .16       0
  4413.7      .1       0    4478     .05       0  4527.4      .1       0
    4675     .05       0  4754.9      .1       0  4870.4     .16       0
  4929.3     .07       0  5051.2      .1       0    5108     .16       0
  5354.7      .1       0  5648.1     .05       0  5977.2      .1       0
  6470.4     .05       0  6493.6      .1       0
Bank Sta=4935.2,5051.2
XS Rating Curve= 0 ,0
Exp/Cntr=0.3,0.1

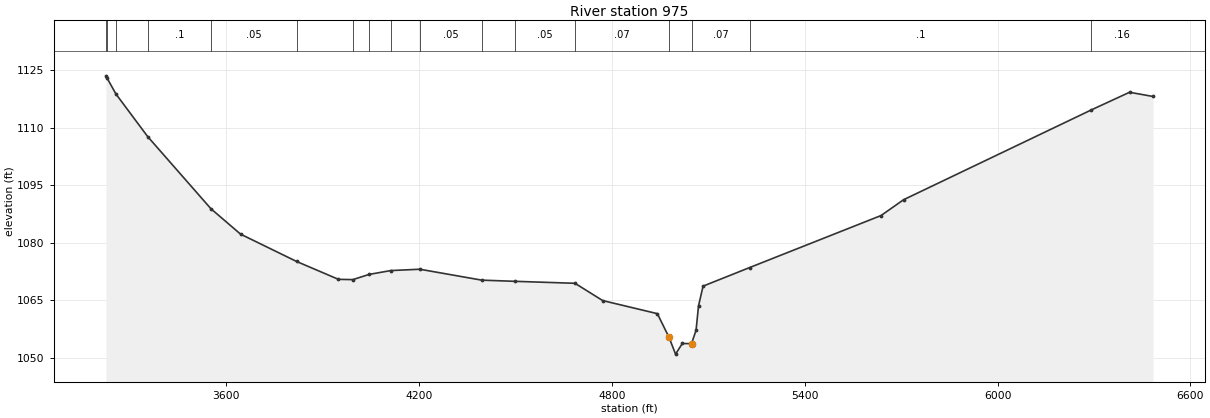
Type RM Length L Ch R = 1 ,975     ,0,0,0
BEGIN DESCRIPTION:
HARDIN RUSSELL CREEK 1.0
END DESCRIPTION:
XS GIS Cut Line= 4
      2915832.79     10084120.87      2914566.94     10083020.53
       2914374.6     10082801.35      2913153.46     10082385.35
#Sta/Elev= 30
  3225.1 1123.59  3229.1 1122.95  3256.4 1118.84  3355.2 1107.73    3552 1088.91
  3644.1 1082.29  3818.7 1075.15  3948.9 1070.49  3993.7 1070.42  4044.4 1071.78
  4111.6 1072.78    4202 1073.13  4394.9 1070.28  4497.1 1069.98    4685 1069.46
  4771.2 1064.95  4941.3 1061.54  4977.3 1055.42    4998 1050.98  5019.1 1053.76
  5047.6 1053.71  5061.8 1057.21  5069.4 1063.57  5083.6 1068.72  5228.3 1073.56
  5637.5 1087.14  5707.5 1091.26  6291.7 1114.69  6410.8  1119.3    6484  1118.2
#Mann= 17 ,-1 , 0
  3225.1     .16       0  3229.1      .1       0  3256.4     .16       0
  3355.2      .1       0    3552     .05       0  3818.7      .1       0
  3993.7     .16       0  4044.4     .05       0  4111.6      .1       0
    4202     .05       0  4394.9      .1       0  4497.1     .05       0
    4685     .07       0  4977.3     .05       0  5047.6     .07       0
  5228.3      .1       0  6291.7     .16       0
Bank Sta=4977.3,5047.6
XS Rating Curve= 0 ,0
Exp/Cntr=0.3,0.1

Chan Stop Cuts=-1
Use User Specified Reach Order=0
Composite Channel Slope=5