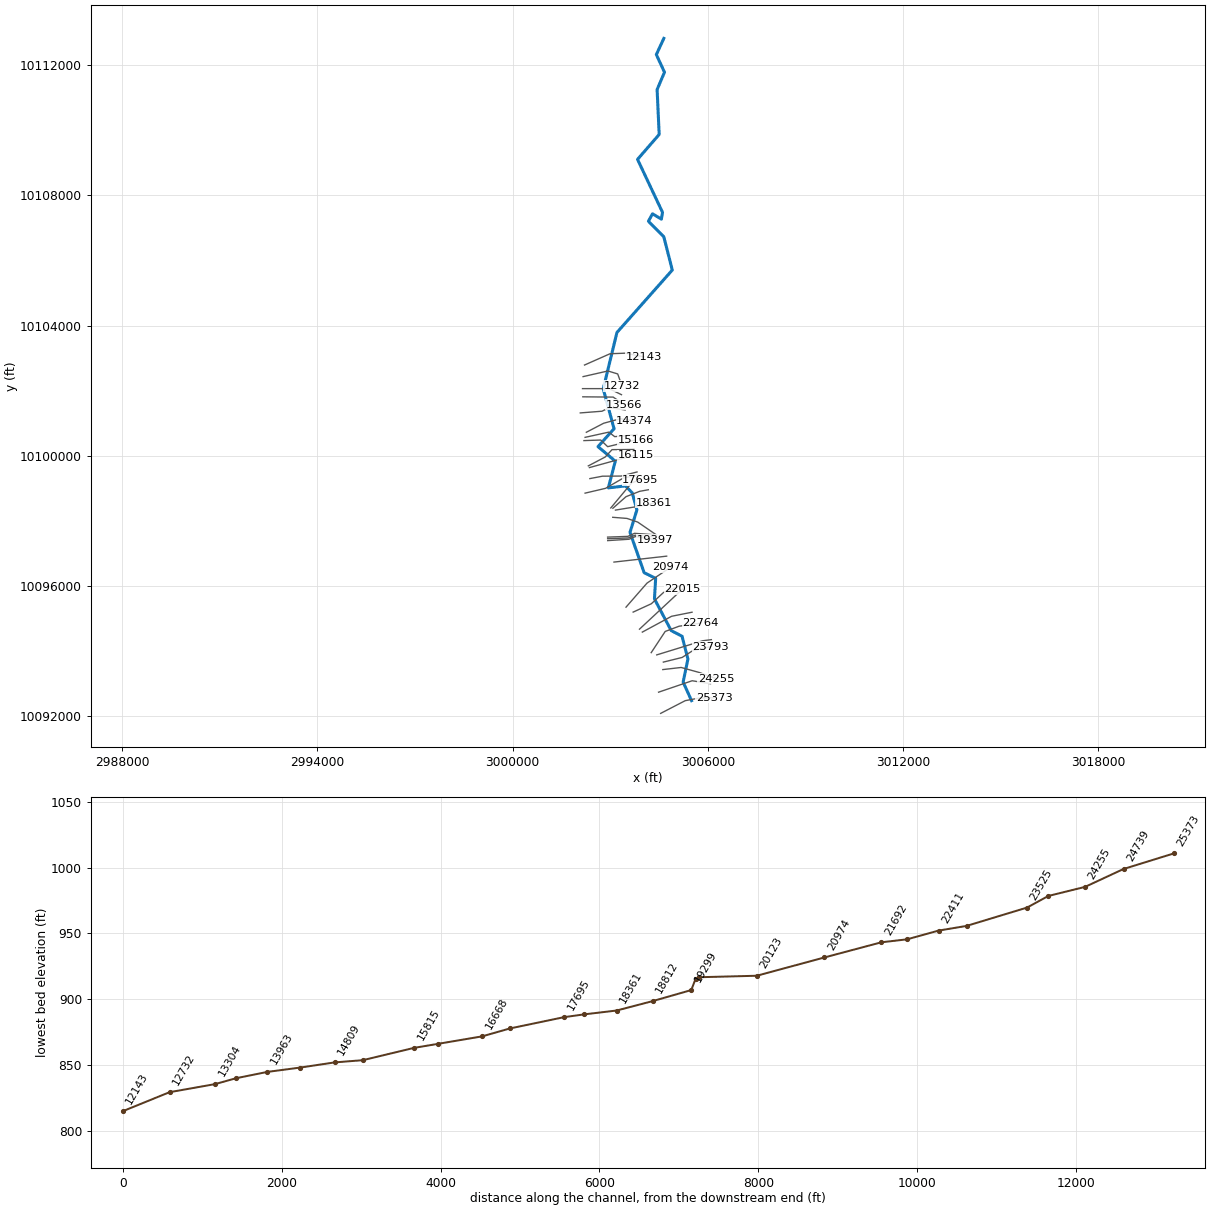
--- LICK CREEK.prj (project) ---

Proj Title=LICK CREEK Base Level Engineering
Current Plan=p01
Default Exp/Contr=0.3,0.1
English Units
Geom File=g01
Flow File=f01
Plan File=p01
Y Axis Title=Elevation
X Axis Title(PF)=Main Channel Distance
X Axis Title(XS)=Station
BEGIN DESCRIPTION:
LICK CREEK
END DESCRIPTION:
DSS Export Rating Curves= 0
DSS Export Rating Curve Sorted= 0
DSS Export Volume Flow Curves= 0
DXF OffsetX= 0
DXF OffsetY= 0
DXF ScaleX= 1
DXF ScaleY= 10

--- LICK CREEK.p01 (plan) ---

Plan Title=Multiple Run
Short Identifier=Multiple
Geom File=g01
Flow File=f01
Subcritical Flow
K Sum by GR= 0
Std Step Tol= 0.01
Critical Tol= 0.01
Num of Std Step Trials= 20
Max Error Tol= 0.3
Flow Tol Ratio= 0.001
Split Flow NTrial= 30
Split Flow Tol= 0.02
Split Flow Ratio= 0.02
Log Output Level= 0
Friction Slope Method= 1
Unsteady Friction Slope Method= 2
Unsteady Bridges Friction Slope Method= 1
Parabolic Critical Depth
Global Vel Dist=  1 , 1 , 1
Global Log Level= 0
CheckData=True
Encroach Param= -1, 0, 0, 0
BEGIN DESCRIPTION:
Multiple Run
END DESCRIPTION:

--- LICK CREEK.f01 (steady flow) ---

Flow Title=Multiple
Program Version=4.10
Number of Profiles= 7
Profile Names=10-year,25-year,50-year,1pct_min,100-year,1pct_plu,500-year
River Rch & RM=LICK CREEK,Reach-1         ,25373
     891    1293    1643    1530    2070    2799    3293
River Rch & RM=LICK CREEK,Reach-1         ,22764
    1474    2192    2831    2673    3614    4888    5916
River Rch & RM=LICK CREEK,Reach-1         ,12143
    1900    2860    3722    3538    4785    6471    7942
River Rch & RM=LICK CREEK,Reach-1         ,9314
    2619    4002    5263    5049    6829    9235   11550
River Rch & RM=LICK CREEK,Reach-1         ,8935
    2619    4002    5263    5049    6829    9235   11550
River Rch & RM=LICK CREEK,Reach-1         ,2935
    3201    4924    6504    6263    8470   11454   14431
Boundary for River Rch & Prof#=LICK CREEK,Reach-1         , 1
Up Type= 0
Dn Type= 3
Dn Slope=0.005
Boundary for River Rch & Prof#=LICK CREEK,Reach-1         , 2
Up Type= 0
Dn Type= 3
Dn Slope=0.005
Boundary for River Rch & Prof#=LICK CREEK,Reach-1         , 3
Up Type= 0
Dn Type= 3
Dn Slope=0.005
Boundary for River Rch & Prof#=LICK CREEK,Reach-1         , 4
Up Type= 0
Dn Type= 3
Dn Slope=0.005
Boundary for River Rch & Prof#=LICK CREEK,Reach-1         , 5
Up Type= 0
Dn Type= 3
Dn Slope=0.005
Boundary for River Rch & Prof#=LICK CREEK,Reach-1         , 6
Up Type= 0
Dn Type= 3
Dn Slope=0.005
Boundary for River Rch & Prof#=LICK CREEK,Reach-1         , 7
Up Type= 0
Dn Type= 3
Dn Slope=0.005
DSS Import GetInterval= 0
DSS Import GetPeak= 0
DSS Import FillOption= 0

--- LICK CREEK.g01 (geometry) ---

Geom Title=Existing Conditions
Program Version=4.10

River Reach=LICK CREEK      ,Reach-1
Reach XY= 30
      3005497.98     10092474.21      3005239.46     10093044.22
      3005386.95     10093753.42      3005206.05      10094452.8
      3004872.44     10094627.12      3004358.42     10095599.05
      3004394.91     10096232.25      3004041.89     10096405.68
      3003606.17     10097643.44      3003818.28     10098333.92
      3003676.17     10098857.42      3003468.37     10099072.46
      3002940.91     10099012.15      3003154.72      10099832.4
      3002623.13     10100278.85      3003116.77     10100829.55
      3002784.04     10102053.77       3003205.3     10103786.72
      3004906.46     10105705.22      3004645.43     10106728.14
      3004172.02     10107205.34      3004298.93     10107433.38
      3004571.27     10107269.09      3004606.12     10107478.09
      3003838.24      10109106.5      3004503.52     10109871.94
      3004439.93     10111251.18      3004666.91     10111783.44
      3004415.89     10112325.58      3004646.64     10112825.67

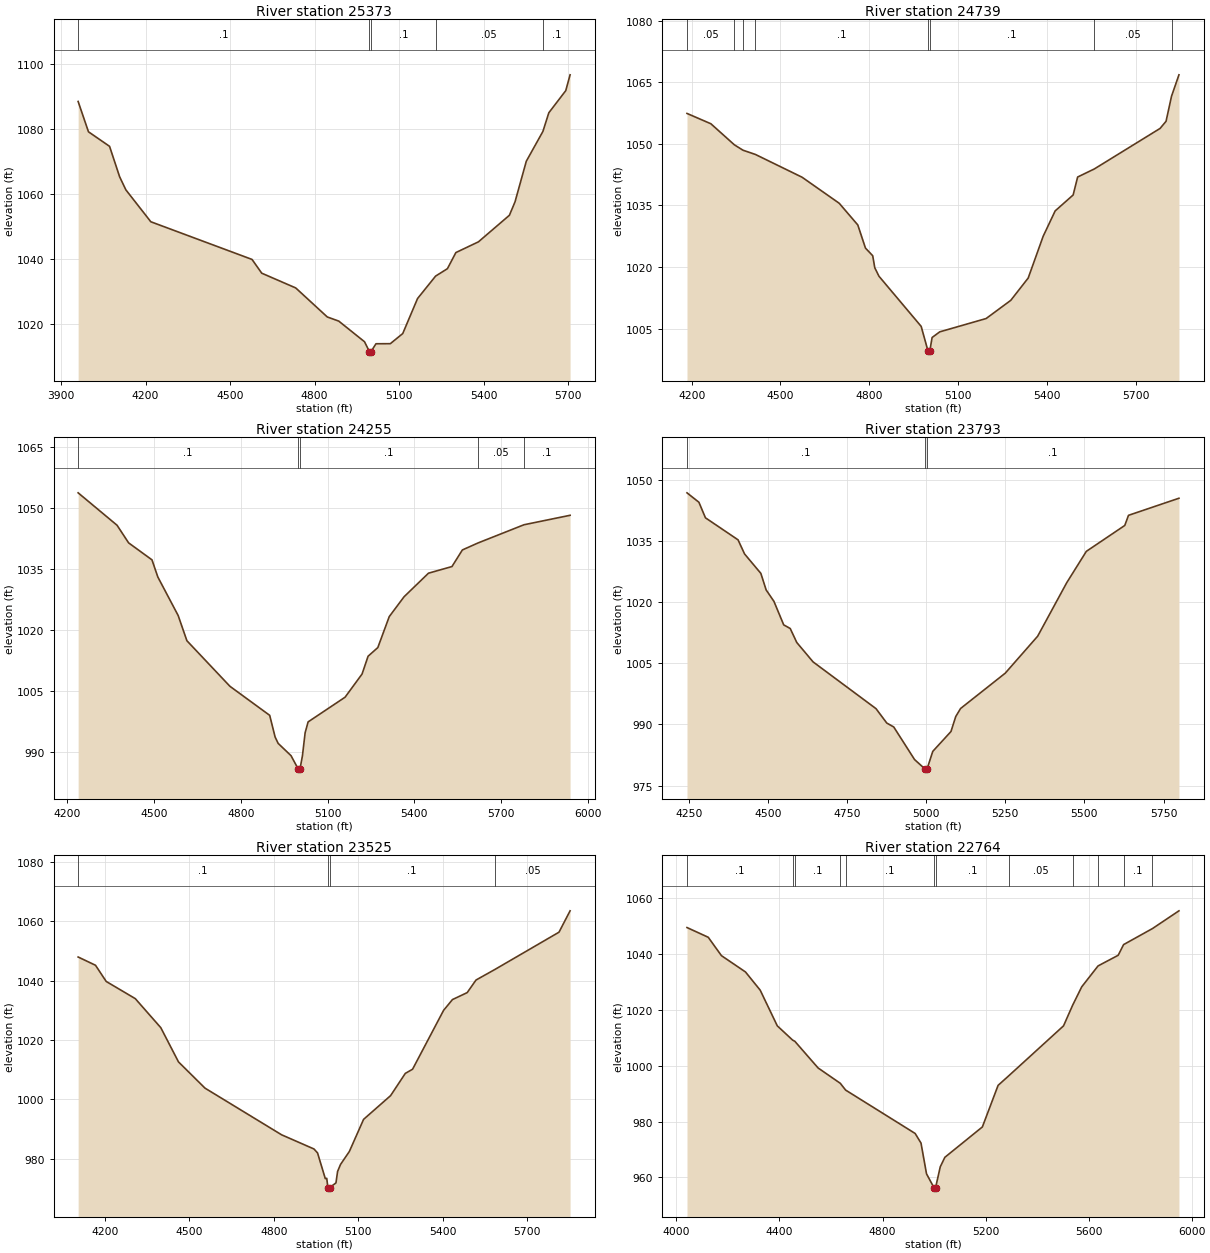
Type RM Length L Ch R = 1 ,25373   ,634,634,634
BEGIN DESCRIPTION:
LICK CREEK 56.0
END DESCRIPTION:
XS GIS Cut Line= 4
      3004549.38     10092082.67       3005304.6      10092473.3
      3005721.27     10092551.42       3006193.9     10092564.43
#Sta/Elev= 30
  3960.4  1088.5  3997.1 1079.15    4072 1074.67  4107.8 1065.27  4129.9 1061.25
  4218.5 1051.41    4578 1039.79  4612.4 1035.55    4733 1031.01  4845.2 1022.05
  4885.8 1020.78  4977.4 1014.41  4994.7  1011.4  4997.5  1010.9  5000.7  1011.4
  5018.1 1013.79    5069 1013.81  5113.1 1016.93  5165.7 1027.73  5229.8 1034.65
  5271.8 1036.94  5301.8 1041.91  5381.8 1045.21  5491.9 1053.41  5511.9 1057.56
  5551.9 1070.07  5610.9 1079.27  5631.9 1085.02    5692 1091.84  5707.4 1096.72
#Mann= 5 ,-1 , 0
  3960.4      .1       0  4994.7     .07       0  5000.7      .1       0
  5229.8     .05       0  5610.9      .1       0
Bank Sta=4994.7,5000.7
XS Rating Curve= 0 ,0
Exp/Cntr=0.3,0.1

Type RM Length L Ch R = 1 ,24739   ,484,484,484
BEGIN DESCRIPTION:
LICK CREEK 55.0
END DESCRIPTION:
XS GIS Cut Line= 3
      3004484.27     10092733.71      3005517.27     10093085.28
      3006081.47     10092994.14
#Sta/Elev= 30
  4184.1 1057.39  4264.8 1054.88  4344.2 1049.75  4373.3 1048.44  4415.2 1047.41
  4573.1 1041.86  4698.6 1035.52  4761.3 1030.25  4787.4  1024.6  4811.8 1022.75
  4818.8 1019.82  4832.9 1017.76  4975.6 1005.55  4998.7  999.54  5001.4  999.04
  5004.7  999.54  5012.5 1002.84  5038.3 1004.22  5195.1 1007.46  5278.4 1011.89
  5337.3 1017.32  5387.9 1027.49  5428.4 1033.66  5489.2 1037.54  5504.4 1041.91
  5560.9 1043.88    5783 1053.74  5803.2 1055.48  5821.8  1061.6  5846.8 1066.79
#Mann= 8 ,-1 , 0
  4184.1     .05       0  4344.2      .1       0  4373.3     .05       0
  4415.2      .1       0  4998.7     .07       0  5004.7      .1       0
  5560.9     .05       0  5821.8      .1       0
Bank Sta=4998.7,5004.7
XS Rating Curve= 0 ,0
Exp/Cntr=0.3,0.1

Type RM Length L Ch R = 1 ,24255   ,462,462,462
BEGIN DESCRIPTION:
LICK CREEK 54.0
END DESCRIPTION:
XS GIS Cut Line= 4
      3004614.54     10093428.16      3005178.73     10093493.26
      3005742.97     10093337.01      3006259.48     10093150.37
#Sta/Elev= 30
  4236.9 1053.68  4371.7 1045.72  4411.6 1041.41  4492.5 1037.24  4512.6 1033.06
  4583.1 1023.59  4613.3 1017.41  4762.3 1006.23  4899.9  999.11  4918.7  993.78
  4929.1  992.24  4973.7  989.22  4998.7  985.93  5001.5  985.43  5004.7  985.93
  5013.2   989.2  5022.5  994.84  5032.8   997.5  5160.8 1003.56  5219.6 1009.25
  5240.4 1013.61  5274.1 1015.73  5313.6 1023.32  5364.9 1028.19  5449.4 1033.97
  5530.7  1035.6  5566.7 1039.67  5621.4  1041.4    5780 1045.85  5939.5 1048.17
#Mann= 5 ,-1 , 0
  4236.9      .1       0  4998.7     .07       0  5004.7      .1       0
  5621.4     .05       0    5780      .1       0
Bank Sta=4998.7,5004.7
XS Rating Curve= 0 ,0
Exp/Cntr=0.3,0.1

Type RM Length L Ch R = 1 ,23793   ,268,268,268
BEGIN DESCRIPTION:
LICK CREEK 53.0
END DESCRIPTION:
XS GIS Cut Line= 4
      3004631.89      10093658.2      3005209.11     10093801.42
      3005534.64     10094009.76      3006093.97      10094135.5
#Sta/Elev= 30
  4244.3 1046.93    4282 1044.61  4302.6 1040.79  4405.6 1035.38  4426.2 1031.91
  4477.7 1027.13  4494.4 1023.07    4519 1020.26  4549.9 1014.48  4570.5 1013.59
  4591.1 1010.16  4642.6 1005.39  4841.6  993.89  4875.5  990.36  4897.6  989.39
  4963.4  981.38  4996.8  979.04  4999.5  978.54  5002.8  979.04  5020.9  983.39
  5078.4  988.27  5093.6  991.97  5108.8  993.93  5249.9 1002.61  5352.4  1011.7
  5444.2 1024.84  5506.2 1032.55  5627.6 1038.91  5639.4  1041.4  5798.8  1045.6
#Mann= 3 ,-1 , 0
  4244.3      .1       0  4996.8     .07       0  5002.8      .1       0
Bank Sta=4996.8,5002.8
XS Rating Curve= 0 ,0
Exp/Cntr=0.3,0.1

Type RM Length L Ch R = 1 ,23525   ,761,761,761
BEGIN DESCRIPTION:
LICK CREEK 52.0
END DESCRIPTION:
XS GIS Cut Line= 3
      3004427.84     10093879.54      3005838.45     10094313.58
      3006107.55      10094348.3
#Sta/Elev= 30
  4104.9 1048.02  4166.6 1045.23  4204.6 1039.77  4307.9 1033.97  4398.5 1024.17
  4461.3 1012.63  4555.4 1003.78  4827.5  988.03  4942.6  983.24  4955.2  981.91
  4982.7  973.24  4987.9  973.34  4991.9   970.2  4994.6   969.7  4997.9   970.2
  5020.6   971.8  5026.3  975.65  5036.7  978.01  5068.1  982.39  5118.7  993.24
  5214.6 1001.24  5266.9 1008.75  5292.7 1010.16  5402.9 1030.03  5434.3 1033.65
  5486.6    1036    5518 1040.25  5583.9 1043.75  5812.7 1056.39  5852.1  1063.6
#Mann= 4 ,-1 , 0
  4104.9      .1       0  4991.9     .07       0  4997.9      .1       0
  5583.9     .05       0
Bank Sta=4991.9,4997.9
XS Rating Curve= 0 ,0
Exp/Cntr=0.3,0.1

Type RM Length L Ch R = 1 ,22764   ,353,353,353
BEGIN DESCRIPTION:
LICK CREEK 51.0
END DESCRIPTION:
XS GIS Cut Line= 4
      3004258.59     10093948.99      3004688.28     10094600.03
      3005113.63     10094760.62      3005782.03     10094856.11
#Sta/Elev= 30
  4040.9  1049.5  4123.4 1046.01  4174.6 1039.43  4267.9 1033.59  4325.1 1027.06
  4391.4 1014.28  4451.3 1009.14  4459.4 1008.76  4549.8  999.19    4636  993.69
  4656.7  991.26  4926.6  975.72  4949.4  972.27  4970.8  961.25  4999.9  956.27
  5002.6  955.77  5005.9  956.27  5024.2  963.78    5042  967.17  5187.6  978.05
  5248.7  992.95  5290.9  996.45  5502.7 1014.27  5537.7 1021.59  5573.4 1028.26
  5636.8 1035.75  5714.9 1039.56  5735.9 1043.39  5848.1 1049.14  5950.8 1055.49
#Mann= 12 ,-1 , 0
  4040.9      .1       0  4451.3     .05       0  4459.4      .1       0
    4636     .05       0  4656.7      .1       0  4999.9     .07       0
  5005.9      .1       0  5290.9     .05       0  5537.7      .1       0
  5636.8     .05       0  5735.9      .1       0  5848.1     .05       0
Bank Sta=4999.9,5005.9
XS Rating Curve= 0 ,0
Exp/Cntr=0.3,0.1

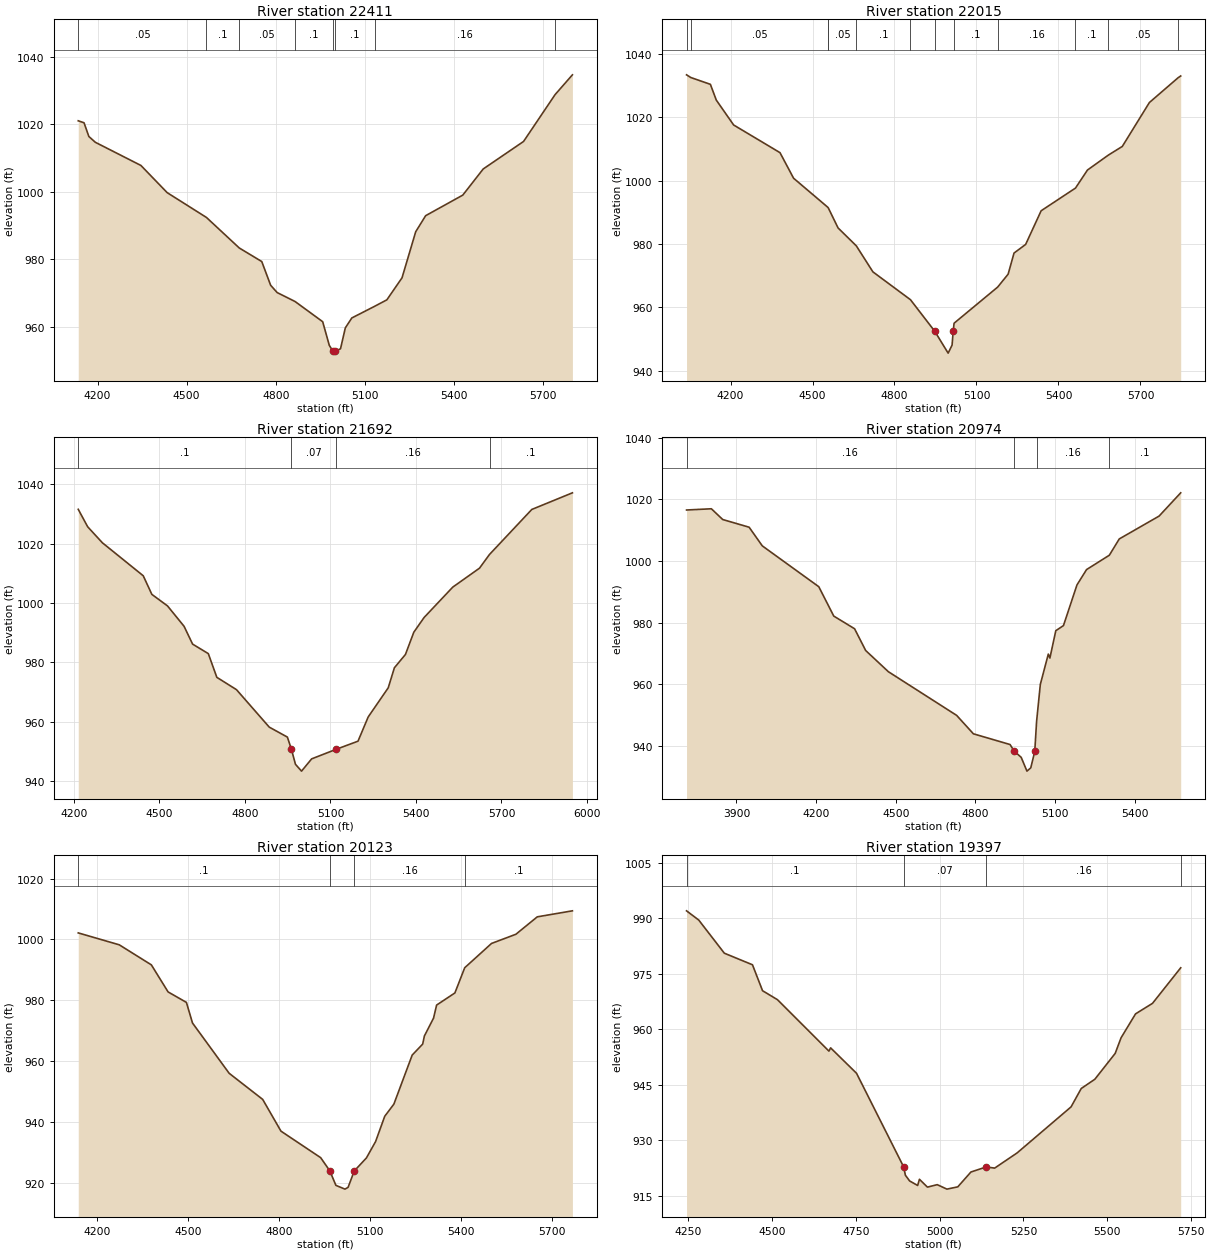
Type RM Length L Ch R = 1 ,22411   ,396,396,396
BEGIN DESCRIPTION:
LICK CREEK 50.0
END DESCRIPTION:
XS GIS Cut Line= 3
      3003985.17     10094580.08      3004884.46     10095066.18
      3005512.89     10095191.17
#Sta/Elev= 30
  4135.1  1021.1  4154.6 1020.51  4170.8 1016.44  4192.7 1014.72  4345.9 1007.86
  4434.4  999.79  4566.6  992.43    4677  983.38  4752.7  979.36  4782.6  972.32
  4804.5  970.16  4864.7  967.51  4957.7  961.52    4980  954.49  4992.8   952.7
  4995.5   952.2  4998.8   952.7  5017.7  953.49  5033.9  959.69  5055.8  962.63
  5132.4  966.08  5173.6     968  5224.7  974.53  5270.7  988.19  5304.2  992.96
  5429.2  999.06  5497.9 1006.81  5633.7 1014.97  5739.7 1028.85  5798.1 1034.73
#Mann= 8 ,-1 , 0
  4135.1     .05       0  4566.6      .1       0    4677     .05       0
  4864.7      .1       0  4992.8     .07       0  4998.8      .1       0
  5132.4     .16       0  5739.7     .05       0
Bank Sta=4992.8,4998.8
XS Rating Curve= 0 ,0
Exp/Cntr=0.3,0.1

Type RM Length L Ch R = 1 ,22015   ,323,323,323
BEGIN DESCRIPTION:
LICK CREEK 49.0
END DESCRIPTION:
XS GIS Cut Line= 2
      3003898.34     10094670.34      3005221.27     10095902.99
#Sta/Elev= 30
  4039.1 1033.36    4055  1032.5  4126.4 1030.36  4147.9  1025.4  4211.4 1017.54
    4381 1008.81  4430.8 1000.74  4555.8  991.59  4558.1  991.33  4593.5  985.06
  4660.4   979.4    4721   971.2  4858.4  962.42  4947.2  952.48  4996.3  945.56
  5010.7  948.08 5014.77  952.39  5018.1     955  5177.5  966.39  5215.9  970.48
  5237.4  977.13  5279.9  979.85  5336.6  990.47  5462.3  997.63  5506.1 1003.32
  5582.1 1008.01  5633.6 1010.77  5732.8 1024.63  5837.9 1032.45  5847.3    1033
#Mann= 12 ,-1 , 0
  4039.1      .1       0    4055     .05       0  4555.8      .1       0
  4558.1     .05       0  4660.4      .1       0  4858.4     .16       0
  4947.2     .07       0  5018.1      .1       0  5177.5     .16       0
  5462.3      .1       0  5582.1     .05       0  5837.9      .1       0
Bank Sta=4947.2,5014.77
XS Rating Curve= 0 ,0
Exp/Cntr=0.3,0.1

Type RM Length L Ch R = 1 ,21692   ,718,718,718
BEGIN DESCRIPTION:
LICK CREEK 48.0
END DESCRIPTION:
XS GIS Cut Line= 4
      3003703.89     10095194.64      3004262.93      10095451.6
      3004637.93     10095798.82      3005200.41     10096027.98
#Sta/Elev= 30
  4215.2  1031.6  4248.3 1025.71  4299.8 1020.32  4443.2 1009.19  4473.4 1002.92
  4528.4  999.02  4586.5  992.15  4616.4  986.14  4671.5  982.94  4701.4  974.94
  4770.4  970.78  4885.4  958.14  4948.9  954.79  4963.1  950.66  4977.3  945.61
  4998.6  943.31    5034  947.44    5119  950.63  5196.7  953.41  5232.4  961.57
  5302.7   971.4  5324.3  978.16  5363.1  982.65  5392.5  990.16  5428.5  995.11
    5529 1005.35  5622.9 1011.75    5658 1016.37  5806.4 1031.55  5948.9 1037.16
#Mann= 4 ,-1 , 0
  4215.2      .1       0  4963.1     .07       0    5119     .16       0
    5658      .1       0
Bank Sta=4963.1,5119
XS Rating Curve= 0 ,0
Exp/Cntr=0.3,0.1

Type RM Length L Ch R = 1 ,20974   ,851,851,851
BEGIN DESCRIPTION:
LICK CREEK 47.0
END DESCRIPTION:
XS GIS Cut Line= 3
      3003483.77      10095346.3      3004129.63     10096085.92
       3004858.8      10096575.5
#Sta/Elev= 30
  3712.4 1016.57  3805.9 1016.97  3848.6 1013.48    3948 1010.98  3997.6 1004.92
  4210.2  991.66  4266.6  982.12    4345     978  4386.8  970.93  4472.2  964.05
  4729.1  949.87  4792.2  943.88  4930.2   940.4  4945.2  938.34  4972.2  936.23
  4993.8  931.76  5008.2  932.82  5023.2  938.15  5030.2  947.98  5044.2  959.94
  5074.2  969.77  5080.2  968.49  5102.4  977.37  5131.2  979.03  5182.2  992.25
  5218.2  997.22    5304 1001.89  5341.3 1007.17  5491.3  1014.6  5572.6 1022.15
#Mann= 4 ,-1 , 0
  3712.4     .16       0  4945.2     .07       0  5030.2     .16       0
    5304      .1       0
Bank Sta=4945.2,5023.2
XS Rating Curve= 0 ,0
Exp/Cntr=0.3,0.1

Type RM Length L Ch R = 1 ,20123   ,726,726,726
BEGIN DESCRIPTION:
LICK CREEK 46.0
END DESCRIPTION:
XS GIS Cut Line= 2
      3003114.02     10096731.75       3004733.6     10096914.02
#Sta/Elev= 30
  4137.7 1002.14    4273  998.22  4378.8  991.63    4434  982.73  4494.4  979.29
  4514.5  972.51  4635.3  955.98    4746  947.38  4806.3  936.94  4937.2  928.22
  4967.3   923.9  4987.5  919.11  5017.4  917.87  5027.7  918.46  5047.9  923.82
  5088.1  928.13  5118.3   933.5  5148.5  941.83  5178.7  945.83  5239.1  961.96
  5273.7  965.58  5279.3  968.24  5309.5  974.11  5319.6   978.4  5379.9  982.39
  5412.3  990.68  5500.7  998.67  5581.2  1001.7  5651.6 1007.42  5767.5  1009.4
#Mann= 4 ,-1 , 0
  4137.7      .1       0  4967.3     .07       0  5047.9     .16       0
  5412.3      .1       0
Bank Sta=4967.3,5047.9
XS Rating Curve= 0 ,0
Exp/Cntr=0.3,0.1

Type RM Length L Ch R = 1 ,19397   ,43,43,43
BEGIN DESCRIPTION:
LICK CREEK 45.0
END DESCRIPTION:
XS GIS Cut Line= 4
      3002922.02     10097391.47      3003574.77     10097433.14
      3003774.42     10097516.47      3004371.62     10097420.99
#Sta/Elev= 30
  4244.4  991.96  4280.9  989.46  4357.2  980.51  4441.2  977.38  4471.3  970.37
  4515.9  967.94  4669.5  954.04  4674.5  954.92  4751.9  948.05  4892.2  922.81
  4897.8  920.48  4910.4  918.95  4934.3  917.73  4939.7   919.4  4963.5  917.28
  4992.7  917.95  5021.7  916.74  5054.2  917.36  5093.4  921.37  5139.2  922.74
  5164.2  922.42  5231.3  926.53  5392.3  938.97  5422.7  943.94  5463.2  946.43
    5524  953.42  5541.5  957.63  5584.8  964.11  5635.4  966.95  5719.6  976.56
#Mann= 4 ,-1 , 0
  4244.4      .1       0  4892.2     .07       0  5139.2     .16       0
  5719.6      .1       0
Bank Sta=4892.2,5139.2
XS Rating Curve= 0 ,0
Exp/Cntr=0.3,0.1

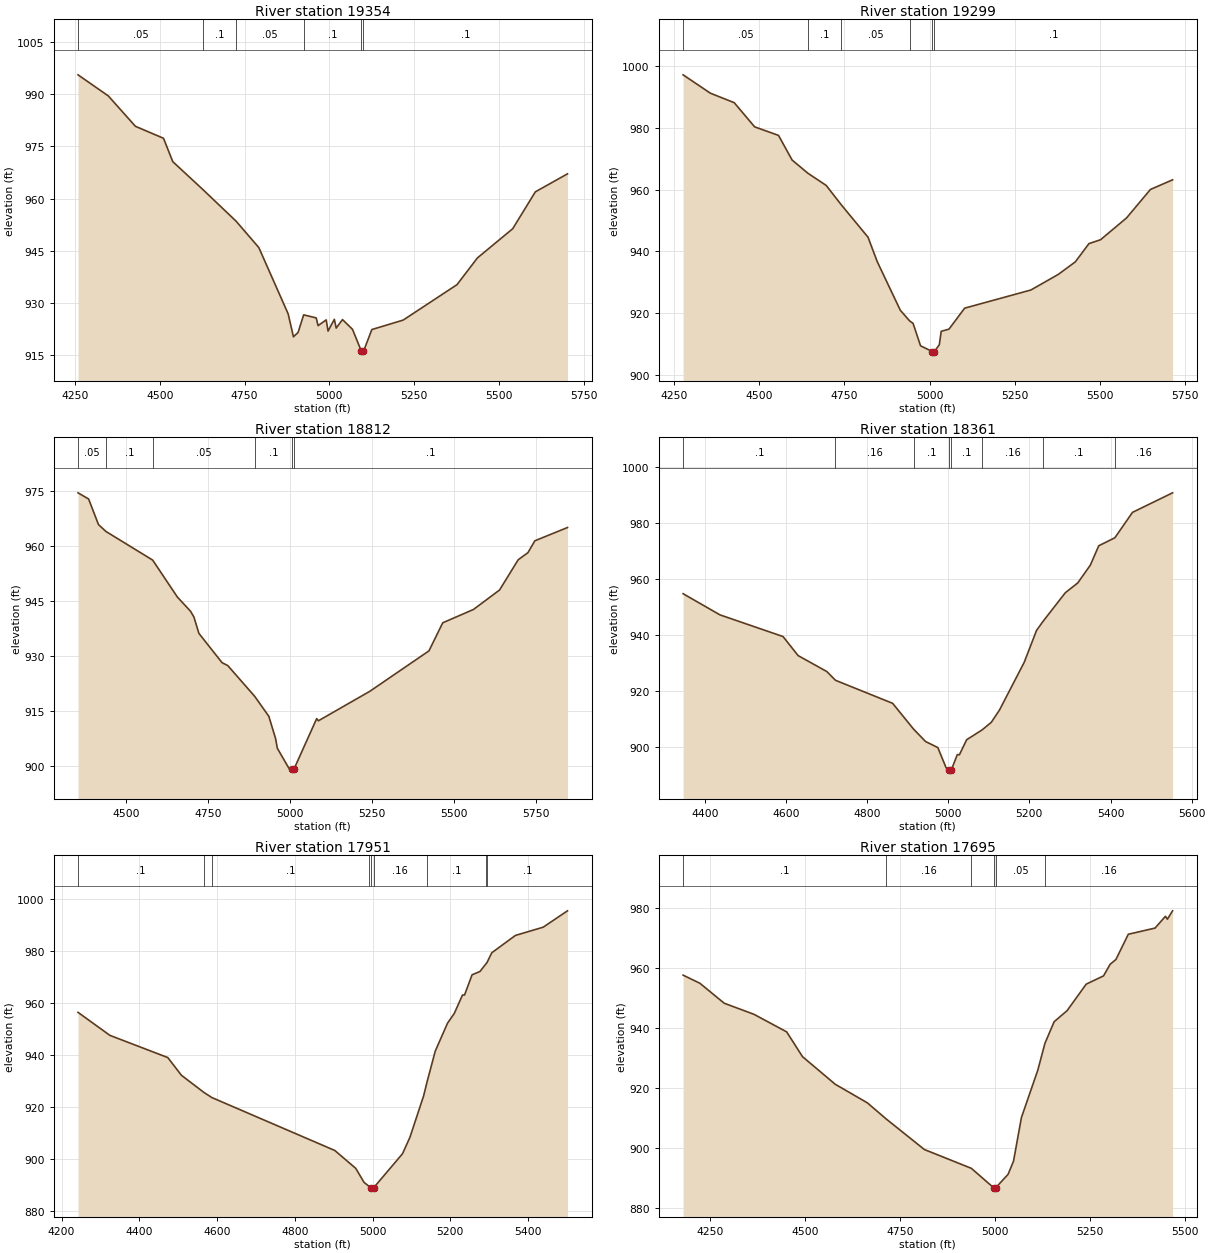
Type RM Length L Ch R = 1 ,19354   ,55,55,55
BEGIN DESCRIPTION:
LICK CREEK 44.0
END DESCRIPTION:
XS GIS Cut Line= 4
      3002919.23     10097449.86       3003554.6     10097472.43
      3003762.93      10097557.5      3004342.83     10097503.68
#Sta/Elev= 30
  4258.7  995.53    4348  989.48    4428  980.75  4510.8  977.32  4538.1  970.61
  4626.5  962.64  4725.1  953.49  4791.8  945.95  4878.3  926.92  4893.9  920.34
  4907.6  921.59    4924  926.64  4961.1  925.76  4966.5  923.54  4990.5   925.2
  4995.9  921.98  5014.5  925.36  5019.9  922.84  5038.5  925.28    5068  922.49
  5094.4  916.15  5097.1  915.65  5100.4  916.15  5125.1  922.42  5217.4  925.13
  5376.1   935.3  5436.4  942.98  5540.4  951.36  5607.1  961.94  5701.9  967.11
#Mann= 6 ,-1 , 0
  4258.7     .05       0  4626.5      .1       0  4725.1     .05       0
    4924      .1       0  5094.4     .07       0  5100.4      .1       0
Bank Sta=5094.4,5100.4
XS Rating Curve= 0 ,0
Exp/Cntr=0.3,0.1

Type RM Length L Ch R = 1 ,19299   ,487,487,487
BEGIN DESCRIPTION:
LICK CREEK 43.0
END DESCRIPTION:
XS GIS Cut Line= 4
      3002918.49     10097499.11      3003540.04     10097521.68
      3003743.17     10097615.43      3004333.43     10097573.77
#Sta/Elev= 30
  4276.3  997.21  4356.3  991.26  4426.4  988.18  4486.4  980.34  4556.5  977.57
  4596.5  969.57  4642.8   965.3  4696.5  961.35  4741.4  954.99  4819.3  944.57
  4846.6  936.59  4914.1   920.9  4941.8  917.39  4951.6  916.64  4973.6  909.35
  5008.4  907.48  5011.1  906.98  5014.4  907.48  5028.7  909.72  5034.3  914.05
  5057.2  914.77  5103.1  921.56  5297.7  927.45  5377.9  932.49    5428  936.56
  5468.1  942.48  5502.2  943.75  5578.4   950.8  5648.6  960.04  5713.7  963.17
#Mann= 6 ,-1 , 0
  4276.3     .05       0  4642.8      .1       0  4741.4     .05       0
  4941.8      .1       0  5008.4     .07       0  5014.4      .1       0
Bank Sta=5008.4,5014.4
XS Rating Curve= 0 ,0
Exp/Cntr=0.3,0.1

Type RM Length L Ch R = 1 ,18812   ,451,451,451
BEGIN DESCRIPTION:
LICK CREEK 42.0
END DESCRIPTION:
XS GIS Cut Line= 4
       3003076.3     10098107.85      3003514.67     10098073.12
      3003844.53     10097960.28      3004424.77     10097561.91
#Sta/Elev= 30
  4352.8  974.52  4385.1  972.84  4415.2  965.86  4437.9  963.98  4580.4  956.16
  4655.9  946.06    4696  942.19  4706.1  940.64  4721.3  936.17  4791.9  928.17
  4809.3  927.38  4891.3     919  4934.5  913.54  4955.1  907.47  4960.5   904.8
  4997.4  899.09  5004.9  899.07  5007.7  898.57  5010.9  899.07  5080.4   912.9
  5085.7  912.31    5243  920.39  5422.7  931.39  5464.7  939.05  5558.4  942.69
  5637.9     948  5694.7  956.25  5724.5   958.2  5745.5  961.43    5845  965.05
#Mann= 6 ,-1 , 0
  4352.8     .05       0  4437.9      .1       0  4580.4     .05       0
  4891.3      .1       0  5004.9     .07       0  5010.9      .1       0
Bank Sta=5004.9,5010.9
XS Rating Curve= 0 ,0
Exp/Cntr=0.3,0.1

Type RM Length L Ch R = 1 ,18361   ,410,410,410
BEGIN DESCRIPTION:
LICK CREEK 41.0
END DESCRIPTION:
XS GIS Cut Line= 3
      3003158.78      10098329.2      3004113.63     10098485.45
      3004343.55     10098550.52
#Sta/Elev= 30
  4346.5  954.82  4437.4  947.26  4592.9  939.51  4629.9  932.72  4700.8  927.01
  4722.1  923.89    4863  915.66  4914.7  906.43    4944  902.03  4974.4  899.85
  4994.7  892.66  5001.8  891.94  5004.6  891.44  5007.8  891.94  5022.4  897.35
  5027.5  897.27  5045.4  902.65  5083.5  906.17  5106.2  908.88  5126.4  913.28
  5187.2  930.29  5217.6  941.68    5233  944.81  5288.6  955.17  5319.2  958.66
  5350.3  965.03    5371  971.94  5410.7   974.8  5454.2  983.88    5553  990.86
#Mann= 8 ,-1 , 0
  4346.5      .1       0  4722.1     .16       0  4914.7      .1       0
  5001.8     .07       0  5007.8      .1       0  5083.5     .16       0
    5233      .1       0  5410.7     .16       0
Bank Sta=5001.8,5007.8
XS Rating Curve= 0 ,0
Exp/Cntr=0.3,0.1

Type RM Length L Ch R = 1 ,17951   ,256,256,256
BEGIN DESCRIPTION:
LICK CREEK 40.0
END DESCRIPTION:
XS GIS Cut Line= 4
      3003080.62     10098385.61      3003484.29     10098741.53
      3003905.29     10098906.46       3004170.1     10098954.21
#Sta/Elev= 30
  4242.3   956.5  4324.4  947.64  4473.3  939.11  4508.4  932.29  4566.2   925.7
  4586.6  923.73  4903.1  903.36  4956.8  896.51  4978.3   891.1  4992.1  889.45
  4996.8     889  4999.5   888.5  5002.8     889  5077.3  902.13  5096.4  908.47
  5131.6   924.4  5140.3  929.69  5161.4  941.56  5193.1  952.36  5210.3  956.04
  5231.6  963.17  5236.8  963.17  5256.2  970.94  5276.5  972.22    5293  975.35
  5294.7  975.69    5307  979.43  5367.9   986.1  5439.1  989.25  5501.7  995.55
#Mann= 9 ,-1 , 0
  4242.3      .1       0  4566.2     .16       0  4586.6      .1       0
  4992.1     .16       0  4996.8     .07       0  5002.8     .16       0
  5140.3      .1       0    5293     .16       0  5294.7      .1       0
Bank Sta=4996.8,5002.8
XS Rating Curve= 0 ,0
Exp/Cntr=0.3,0.1

Type RM Length L Ch R = 1 ,17695   ,680,680,680
BEGIN DESCRIPTION:
LICK CREEK 39.0
END DESCRIPTION:
XS GIS Cut Line= 3
      3003015.54      10098394.3      3003662.24     10099171.21
      3003925.23     10099253.13
#Sta/Elev= 30
    4180  957.54  4224.2  954.83    4288   948.2  4366.1  944.51  4452.1  938.67
  4493.7  930.43  4579.6  921.25  4664.2  915.05  4713.2  909.74    4814  899.52
  4937.5  893.26  4995.8  886.84  4998.6  886.34  5001.8  886.84    5034  891.26
  5048.3  895.65  5069.1  910.17  5112.1  925.92  5130.8  934.83    5155  942.03
  5189.2  945.74  5239.3  954.54  5284.9   957.3  5302.1  961.14  5317.4  962.75
  5349.9  971.14  5420.2   973.2  5447.5  977.12  5452.7  976.16  5466.3  978.94
#Mann= 6 ,-1 , 0
    4180      .1       0  4713.2     .16       0  4937.5     .05       0
  4995.8    .035       0  5001.8     .05       0  5130.8     .16       0
Bank Sta=4995.8,5001.8
XS Rating Curve= 0 ,0
Exp/Cntr=0.3,0.1

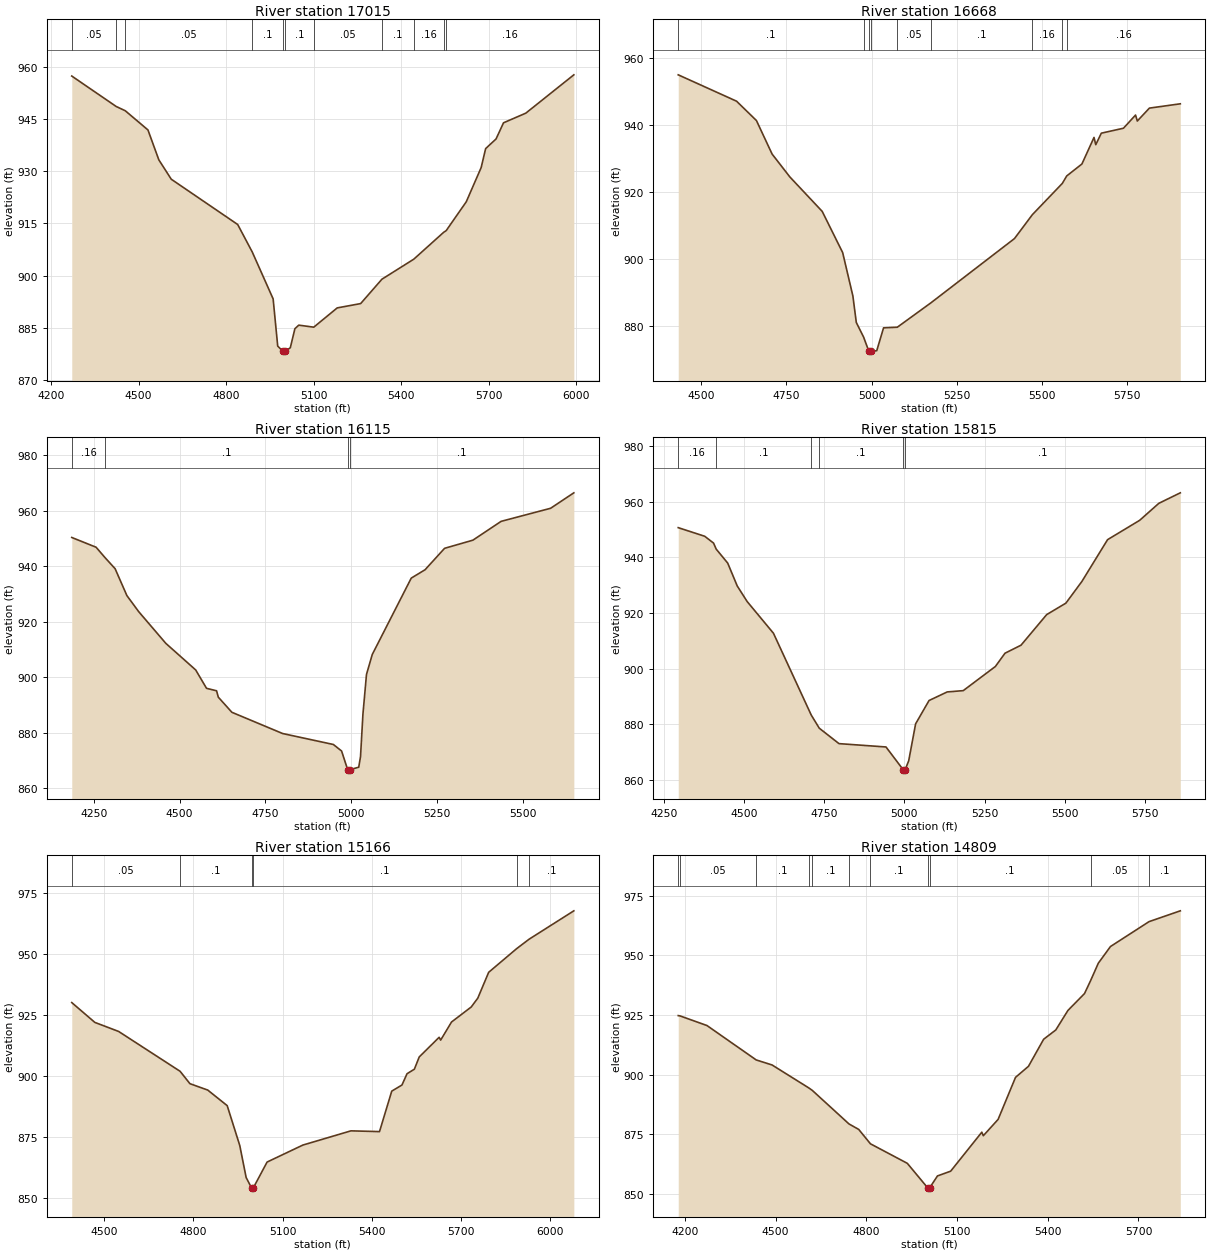
Type RM Length L Ch R = 1 ,17015   ,347,347,347
BEGIN DESCRIPTION:
LICK CREEK 38.0
END DESCRIPTION:
XS GIS Cut Line= 4
      3002225.59     10098850.03      3002854.95      10098997.6
      3003401.82     10099314.44      3003834.69     10099401.02
#Sta/Elev= 30
  4271.1   957.3  4423.2  948.57  4454.5  947.33  4532.1  941.83  4569.4  933.24
  4611.9  927.69  4839.5  914.69  4889.3  906.81  4960.9  893.34  4976.6  879.78
  4995.1  878.27  4997.9  877.77  5001.1  878.27  5019.7  879.31  5035.4  884.77
  5048.7   885.8  5100.1  885.22  5180.4  890.75  5260.7  891.99  5333.6  898.99
  5442.8  904.74  5545.1  912.45  5553.7  912.93  5622.5  921.21  5673.5  931.03
  5688.9  936.48  5724.5  939.24  5750.1  943.88  5826.5  946.65    5991  957.65
#Mann= 11 ,-1 , 0
  4271.1     .05       0  4423.2      .1       0  4454.5     .05       0
  4889.3      .1       0  4995.1     .07       0  5001.1      .1       0
  5100.1     .05       0  5333.6      .1       0  5442.8     .16       0
  5545.1      .1       0  5553.7     .16       0
Bank Sta=4995.1,5001.1
XS Rating Curve= 0 ,0
Exp/Cntr=0.3,0.1

Type RM Length L Ch R = 1 ,16668   ,553,553,553
BEGIN DESCRIPTION:
LICK CREEK 37.0
END DESCRIPTION:
XS GIS Cut Line= 4
      3002373.14     10099297.08      3002759.46     10099370.87
      3003336.72     10099375.21      3003822.81     10099501.07
#Sta/Elev= 30
  4432.9  955.06    4604  947.17  4662.3  941.38  4708.2  931.36  4760.3  924.51
  4855.2   914.2  4915.2  901.88  4945.2  888.88  4955.2  880.97  4976.8  876.55
  4992.2  872.29    4995  871.79  4998.2  872.29  5015.2  872.52  5035.2  879.36
  5075.5  879.54  5174.1  886.84  5419.2  906.07  5471.6  913.21  5559.5  922.57
  5572.4   924.8    5617  928.38  5652.5  936.33  5657.6  934.15  5673.9   937.6
  5738.8  939.08  5774.3  943.02  5779.5  941.24  5814.9   945.1  5905.6  946.39
#Mann= 9 ,-1 , 0
  4432.9      .1       0  4976.8     .16       0  4992.2     .07       0
  4998.2     .16       0  5075.5     .05       0  5174.1      .1       0
  5471.6     .16       0  5559.5      .1       0  5572.4     .16       0
Bank Sta=4992.2,4998.2
XS Rating Curve= 0 ,0
Exp/Cntr=0.3,0.1

Type RM Length L Ch R = 1 ,16115   ,300,300,300
BEGIN DESCRIPTION:
LICK CREEK 36.0
END DESCRIPTION:
XS GIS Cut Line= 3
      3002360.13     10099635.62      3003336.72     10099904.72
      3003774.23     10100013.02
#Sta/Elev= 30
  4185.9  950.39  4256.8  946.87  4283.2  943.07  4312.2  939.14  4346.6  929.43
    4381  923.64  4460.1   912.2  4547.2  902.61  4578.8  895.98    4608   895.1
  4613.2  892.78  4652.7  887.34  4800.6  879.68  4948.5  875.73  4972.5  873.38
  4990.3  866.62    4993  866.12  4996.3  866.62  5022.5  867.54  5027.7  871.35
  5034.7  886.62  5045.1     901    5062   908.2  5175.6  935.73  5215.9  938.75
  5272.8  946.48  5355.2  949.41  5437.6   956.2  5581.9  960.92  5649.6  966.49
#Mann= 4 ,-1 , 0
  4185.9     .16       0  4283.2      .1       0  4990.3     .07       0
  4996.3      .1       0
Bank Sta=4990.3,4996.3
XS Rating Curve= 0 ,0
Exp/Cntr=0.3,0.1

Type RM Length L Ch R = 1 ,15815   ,649,649,649
BEGIN DESCRIPTION:
LICK CREEK 35.0
END DESCRIPTION:
XS GIS Cut Line= 4
      3002325.43     10099687.71      3002846.27     10099961.15
       3003054.6     10100186.84      3003725.39     10100191.17
#Sta/Elev= 30
  4294.6  950.67  4377.1  947.58  4404.8  945.12    4413  942.96  4448.9  937.93
  4478.7  929.69  4509.5  924.11  4591.7  912.68  4709.4  883.29  4734.5  878.54
  4796.1  872.98  4942.7  871.78  4996.4  863.59  4999.1  863.09  5002.4  863.59
  5013.5  866.79  5035.1   880.1    5077  888.49  5133.7  891.58  5183.6  892.04
  5283.9  900.73  5313.9   905.5  5363.9  908.39  5443.9  919.39  5503.9  923.52
  5553.9  931.34  5633.9  946.35  5733.9   953.3  5793.9  959.43  5860.8   963.2
#Mann= 6 ,-1 , 0
  4294.6     .16       0    4413      .1       0  4709.4     .05       0
  4734.5      .1       0  4996.4     .07       0  5002.4      .1       0
Bank Sta=4996.4,5002.4
XS Rating Curve= 0 ,0
Exp/Cntr=0.3,0.1

Type RM Length L Ch R = 1 ,15166   ,357,357,357
BEGIN DESCRIPTION:
LICK CREEK 34.0
END DESCRIPTION:
XS GIS Cut Line= 4
      3002190.84     10100464.62      3002707.38     10100481.98
      3002920.05     10100277.99      3003774.24     10100486.11
#Sta/Elev= 30
  4390.1  930.11  4467.8  921.99  4547.8  918.29    4755  901.95    4788  896.88
    4848  894.26  4913.5  887.88  4955.9  871.51  4977.3  858.44  4995.4  854.17
  4998.2  853.67  5001.4  854.17  5047.8  864.76  5168.2  871.72  5330.1  877.55
  5426.4  877.24  5467.6  893.82    5502  896.33  5519.1  900.96  5543.8  902.82
  5560.2  907.84  5627.2  915.89  5632.3  914.73  5668.9  922.15  5735.2   928.3
  5757.4  931.93    5794  942.52  5888.2  952.21  5930.1  956.08  6080.8  967.71
#Mann= 6 ,-1 , 0
  4390.1     .05       0    4755      .1       0  4995.4     .07       0
  5001.4      .1       0  5888.2     .05       0  5930.1      .1       0
Bank Sta=4995.4,5001.4
XS Rating Curve= 0 ,0
Exp/Cntr=0.3,0.1

Type RM Length L Ch R = 1 ,14809   ,435,435,435
BEGIN DESCRIPTION:
LICK CREEK 33.0
END DESCRIPTION:
XS GIS Cut Line= 4
      3002225.62     10100564.45      3002954.77     10100725.03
      3003137.07     10100586.15      3003818.46     10100646.91
#Sta/Elev= 30
  4178.4  924.76    4184  924.65  4273.5  920.59  4436.2  906.16  4488.5  904.06
  4609.6  894.46  4621.4  893.41    4743   879.3  4775.2     877  4813.9  870.97
  4935.7  862.79  5003.4  852.46  5006.2  851.96  5009.4  852.46  5035.5   857.5
  5079.1  859.49    5182  875.84    5187  874.36  5235.9  881.21  5293.5  898.85
  5336.3  903.49  5386.5  914.84  5426.7  918.75  5466.8  926.93  5521.6  934.01
  5541.9  939.48  5567.2  946.74  5607.4  953.74    5735  964.19  5838.3  968.72
#Mann= 11 ,-1 , 0
  4178.4      .1       0    4184     .05       0  4436.2      .1       0
  4609.6     .05       0  4621.4      .1       0    4743     .05       0
  4813.9      .1       0  5003.4     .07       0  5009.4      .1       0
  5541.9     .05       0    5735      .1       0
Bank Sta=5003.4,5009.4
XS Rating Curve= 0 ,0
Exp/Cntr=0.3,0.1

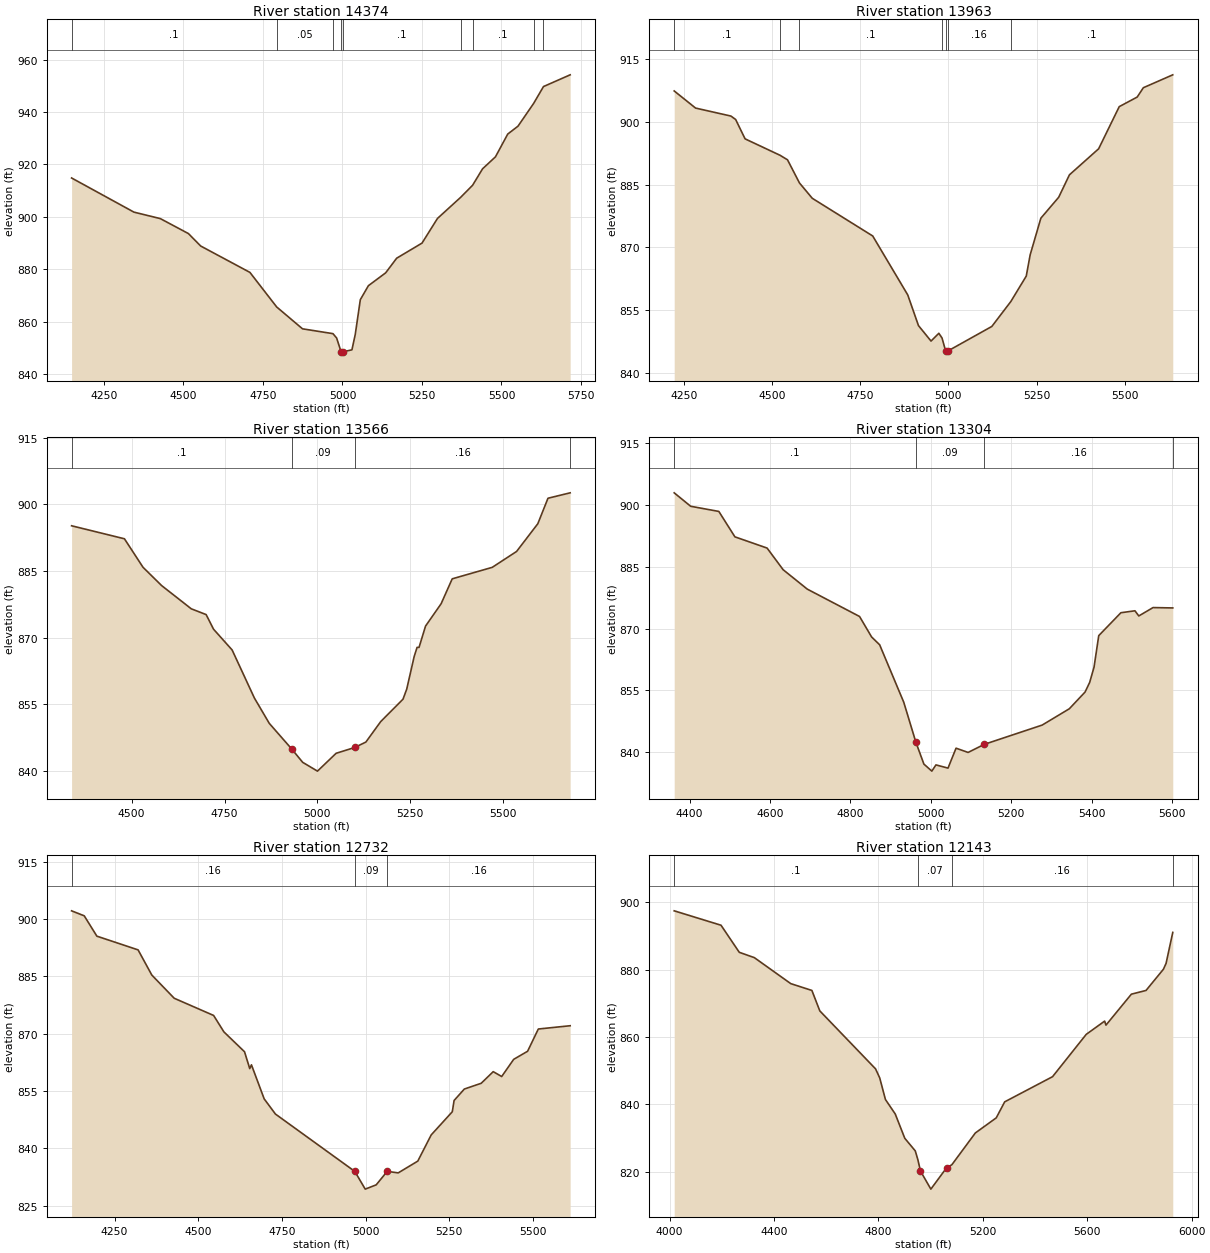
Type RM Length L Ch R = 1 ,14374   ,411,411,411
BEGIN DESCRIPTION:
LICK CREEK 32.0
END DESCRIPTION:
XS GIS Cut Line= 4
      3002264.67     10100720.69      3002798.52     10100998.47
      3003310.68     10101137.36      3003740.35     10101067.92
#Sta/Elev= 30
  4148.3  914.83  4344.4   901.8  4427.2  899.34  4515.6  893.63  4554.2  888.88
    4709  878.82  4793.2  865.63  4874.4  857.29  4970.1  855.45  4981.7  853.79
  4995.7  848.52  4998.5  848.02  5001.7  848.52  5029.8  849.28  5040.2  855.11
  5056.2  868.41  5081.6  873.74  5135.9  878.65  5170.5  884.23  5250.2  889.99
  5298.8   899.4  5371.5  907.43  5409.2  912.05  5440.6  918.33  5481.1   922.9
  5519.7  931.58    5552  934.59  5601.3   943.3  5632.1   949.7    5716  954.18
#Mann= 9 ,-1 , 0
  4148.3      .1       0  4793.2     .05       0  4970.1      .1       0
  4995.7     .07       0  5001.7      .1       0  5371.5     .05       0
  5409.2      .1       0  5601.3     .05       0  5632.1      .1       0
Bank Sta=4995.7,5001.7
XS Rating Curve= 0 ,0
Exp/Cntr=0.3,0.1

Type RM Length L Ch R = 1 ,13963   ,397,397,397
BEGIN DESCRIPTION:
LICK CREEK 31.0
END DESCRIPTION:
XS GIS Cut Line= 4
      3002078.06     10101315.31      3002746.44      10101367.4
      3002976.48     10101480.24      3003458.22     10101406.46
#Sta/Elev= 30
  4222.3  907.36  4282.9  903.27  4383.2  901.36  4396.6  900.54  4423.3  895.92
  4522.8  891.98  4543.7  890.91  4577.6  885.38  4613.9  881.72  4785.3  872.72
  4884.7  858.64  4915.1  851.31  4950.7  847.62  4972.9  849.48  4981.9  848.35
  4992.2  845.24    4995  844.74  4998.2  845.24  5123.1  851.11  5176.9  857.05
  5220.8  863.14  5231.9  868.23  5262.2  876.97  5312.8  881.97  5343.2  887.32
  5426.1  893.55  5484.5  903.61  5535.4   905.9  5552.9  908.13  5636.3  911.21
#Mann= 7 ,-1 , 0
  4222.3      .1       0  4522.8     .05       0  4577.6      .1       0
  4981.9     .16       0  4992.2     .07       0  4998.2     .16       0
  5176.9      .1       0
Bank Sta=4992.2,4998.2
XS Rating Curve= 0 ,0
Exp/Cntr=0.3,0.1

Type RM Length L Ch R = 1 ,13566   ,262,262,262
BEGIN DESCRIPTION:
LICK CREEK 30.0
END DESCRIPTION:
XS GIS Cut Line= 3
      3002156.15      10101810.1      3003089.32     10101801.42
      3003427.85      10101571.4
#Sta/Elev= 30
  4338.2  895.19  4480.5  892.26  4530.5  885.84  4580.5  881.72  4660.5  876.47
  4700.5  875.17  4720.5  871.87  4770.5  867.19  4830.5  856.35  4870.5  850.65
  4930.5  844.91  4960.5  841.86  5000.3  839.88  5050.5   843.9  5100.6  845.21
  5130.6  846.43  5170.6  851.05  5230.6   856.1  5240.6  858.36  5260.6  865.69
  5268.5  867.78  5273.8  867.78  5291.3  872.58  5333.2  877.61  5363.1  883.23
  5470.9  885.82  5536.4   889.4  5593.6  895.65    5621   901.4  5680.7  902.62
#Mann= 4 ,-1 , 0
  4338.2      .1       0  4930.5     .09       0  5100.6     .16       0
  5680.7      .1       0
Bank Sta=4930.5,5100.6
XS Rating Curve= 0 ,0
Exp/Cntr=0.3,0.1

Type RM Length L Ch R = 1 ,13304   ,572,572,572
BEGIN DESCRIPTION:
LICK CREEK 29.0
END DESCRIPTION:
XS GIS Cut Line= 3
      3002147.45     10102061.84      3002963.45     10102061.84
      3003344.41     10101875.69
#Sta/Elev= 30
  4361.9   902.9  4402.9  899.64  4472.9  898.39  4512.9  892.23  4592.9  889.51
  4632.9  884.26  4692.9  879.56  4822.9  872.93  4852.9  867.96  4872.9  866.07
  4932.9  852.13  4962.9  842.48  4982.9  837.16  5002.7  835.45  5012.9  836.96
  5042.9  836.18  5062.9  841.01  5092.9  839.98  5132.9  841.93  5277.1  846.61
  5344.6  850.56  5383.8  854.62  5395.2  856.94  5406.1  860.65  5417.8  868.29
  5472.9  873.84  5507.8  874.31  5517.4  873.06  5552.9  875.09  5601.9     875
#Mann= 4 ,-1 , 0
  4361.9      .1       0  4962.9     .09       0  5132.9     .16       0
  5601.9      .1       0
Bank Sta=4962.9,5132.9
XS Rating Curve= 0 ,0
Exp/Cntr=0.3,0.1

Type RM Length L Ch R = 1 ,12732   ,589,589,589
BEGIN DESCRIPTION:
LICK CREEK 28.0
END DESCRIPTION:
XS GIS Cut Line= 4
       3002164.8     10102430.75      3002928.73     10102604.37
      3003228.21     10102513.23      3003362.74     10102144.35
#Sta/Elev= 30
  4121.8  902.14  4159.6  900.83  4197.3  895.51  4320.4  891.92  4361.4  885.33
  4428.3  879.26    4546  874.76  4576.8  870.45  4638.3  865.26  4653.9  860.85
    4659  861.84    4697  852.93  4730.6  848.96  4967.7  833.95  4998.8  829.31
  5031.6  830.43  5064.5  833.96  5097.3  833.56  5155.8  836.64  5195.9   843.5
  5258.9  849.56  5264.2   852.5  5294.8   855.5  5345.2  857.01  5381.1  860.05
  5406.4  858.78  5442.2  863.27  5483.8  865.39  5515.8  871.21  5610.9  872.07
#Mann= 3 , 0 , 0
  4121.8     .16       0  4967.7     .09       0  5064.5     .16       0
Bank Sta=4967.7,5064.5
XS Rating Curve= 0 ,0
Exp/Cntr=0.3,0.1

Type RM Length L Ch R = 1 ,12143   ,391,391,391
BEGIN DESCRIPTION:
LICK CREEK 27.0
END DESCRIPTION:
XS GIS Cut Line= 4
      3002208.27     10102786.67      3002993.84     10103133.89
      3003466.93     10103151.25      3004033.68     10103038.76
#Sta/Elev= 30
  4017.6  897.51    4197  893.23  4266.9  885.19  4324.5  883.61  4464.3  875.88
  4545.1  873.86  4575.4  867.79  4789.1  850.56    4805  847.87  4826.9  841.46
  4864.4  837.17  4901.1  829.93  4941.2   826.2  4951.2  823.56  4961.2   820.2
  5000.9  814.84  5061.2  821.19  5081.2  822.07  5171.3  831.52  5251.4  836.01
  5283.8  840.77  5467.1  848.24  5596.1  860.81  5666.7  864.75  5671.8  863.56
  5769.1  872.75  5825.3  873.86  5891.8  880.15    5902  881.88  5927.7   891.1
#Mann= 4 ,-1 , 0
  4017.6      .1       0  4951.2     .07       0  5081.2     .16       0
  5927.7      .1       0
Bank Sta=4961.2,5061.2
XS Rating Curve= 0 ,0
Exp/Cntr=0.3,0.1