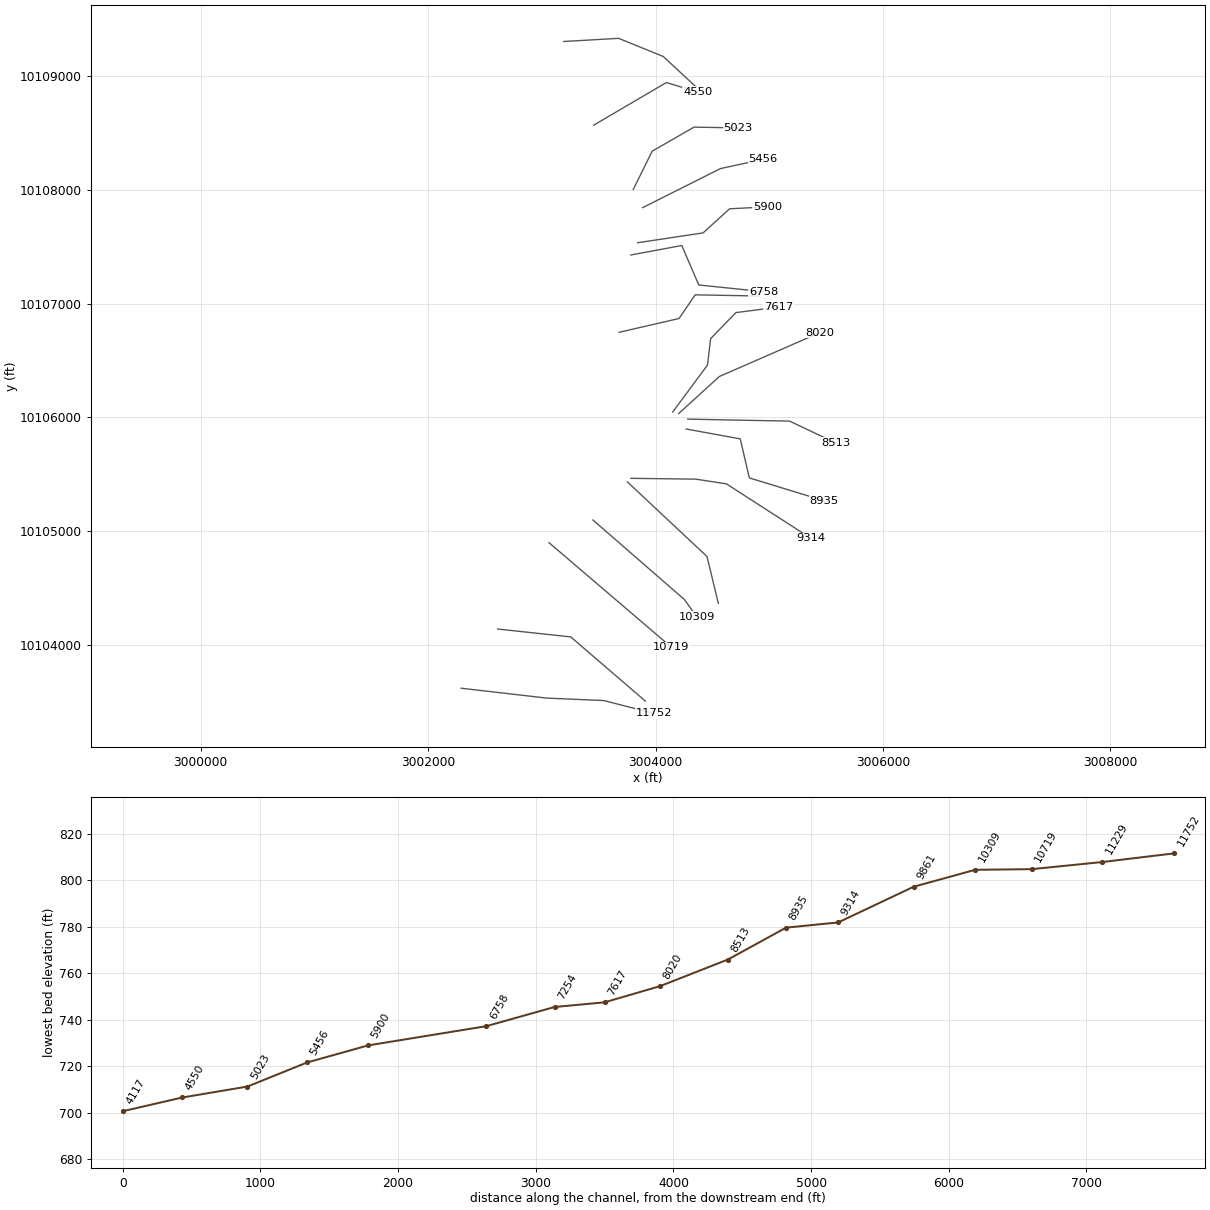
HEC-RAS study LICK CREEK.prj: LICK CREEK Base Level Engineering

--- LICK CREEK.g01 (geometry) --- (continued)

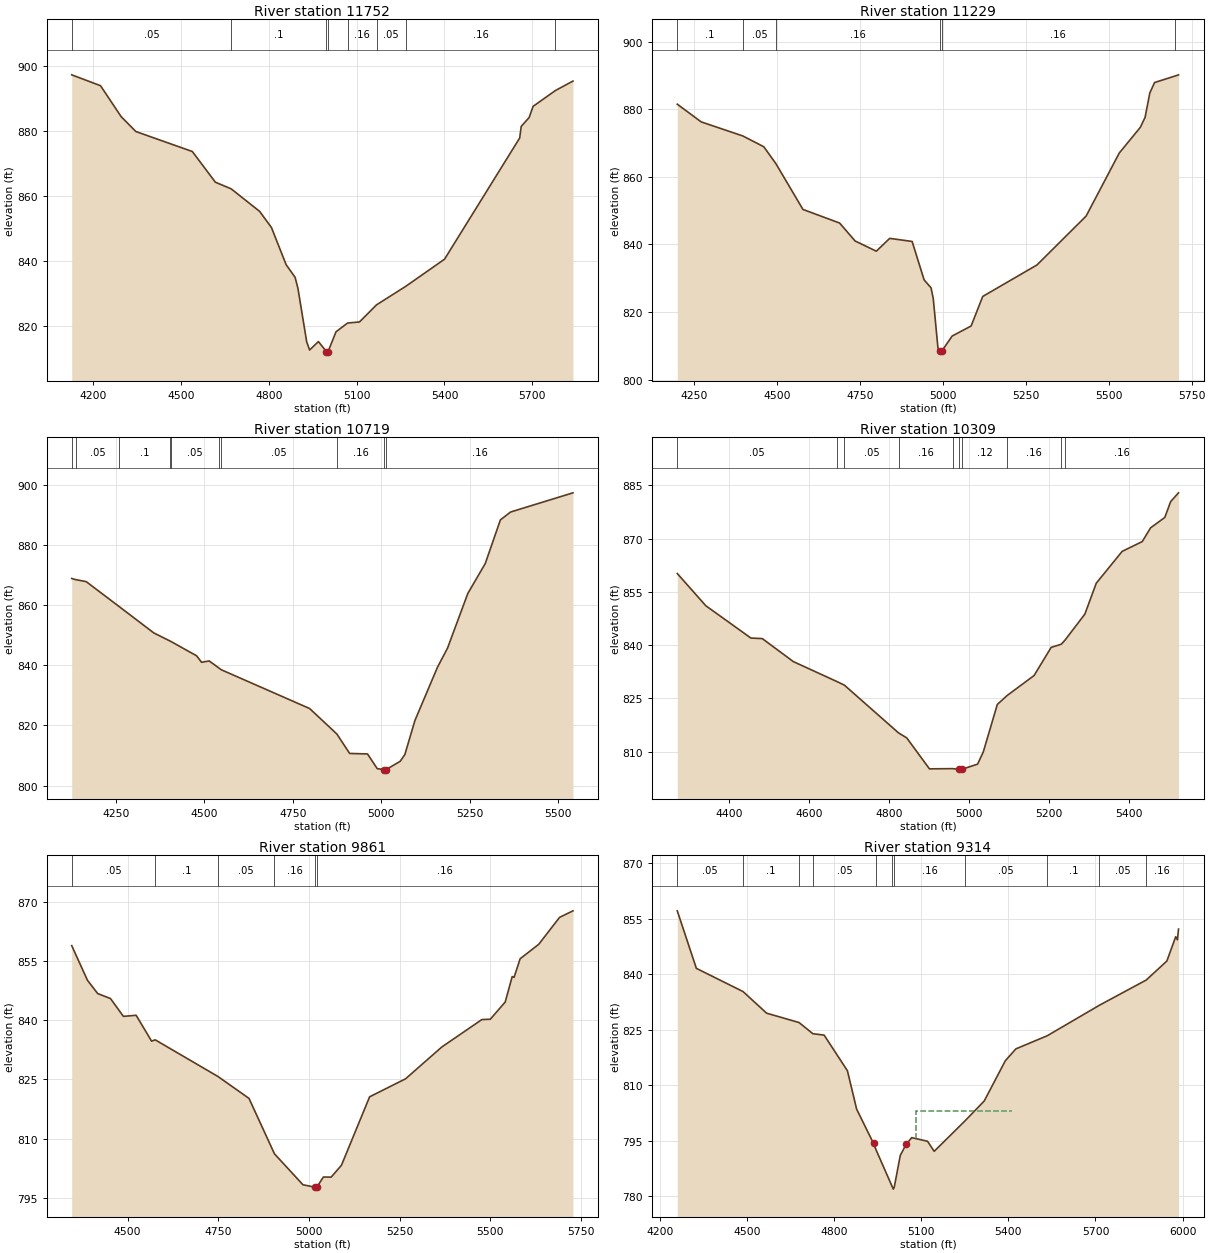
Type RM Length L Ch R = 1 ,11752   ,523,523,523
BEGIN DESCRIPTION:
LICK CREEK 26.0
END DESCRIPTION:
XS GIS Cut Line= 4
       3002290.7     10103615.66      3003041.58     10103528.85
      3003545.05     10103507.15      3003983.44      10103394.3
#Sta/Elev= 30
  4126.6  897.25    4225   893.9  4295.5  884.37  4345.8  879.79  4538.7  873.64
  4617.4  864.19  4671.5  862.14  4768.6  855.21  4808.9  850.25  4859.2  838.79
  4889.8  834.91  4899.4  831.53  4929.4  815.04  4939.4  812.53  4969.4  815.13
  4996.5  812.07  4999.2  811.57  5002.5  812.07  5029.5  818.14  5069.2  820.84
  5109.6  821.16  5168.2  826.45  5267.1  832.09  5400.3  840.49  5657.1  877.81
  5662.2  881.36  5689.4  884.11  5702.9  887.55  5779.2  892.42  5839.1  895.33
#Mann= 8 ,-1 , 0
  4126.6     .05       0  4671.5      .1       0  4996.5     .07       0
  5002.5      .1       0  5069.2     .16       0  5168.2     .05       0
  5267.1     .16       0  5779.2      .1       0
Bank Sta=4996.5,5002.5
XS Rating Curve= 0 ,0
Exp/Cntr=0.3,0.1

Type RM Length L Ch R = 1 ,11229   ,510,510,510
BEGIN DESCRIPTION:
LICK CREEK 25.0
END DESCRIPTION:
XS GIS Cut Line= 3
       3002611.9     10104136.49      3003254.25     10104067.05
      3003909.63     10103502.81
#Sta/Elev= 30
  4199.6  881.52  4271.7  876.28  4397.1  872.12  4460.3  868.93  4496.8  863.93
  4578.4  850.37    4689  846.34  4735.6  841.03  4799.6  838.01  4839.9  841.81
  4907.5  840.89  4943.6  829.53  4964.6  827.16  4971.2  823.98  4985.4  809.33
  4990.1  808.34  4992.8  807.84  4996.1  808.34  5028.2   812.9  5085.3  815.87
  5120.4  824.62  5283.9  833.94    5432  848.41  5531.8  867.05  5595.5  874.69
  5609.7  877.62    5624  884.86  5638.3  887.93  5698.9  889.82  5710.5  890.21
#Mann= 6 ,-1 , 0
  4199.6      .1       0  4397.1     .05       0  4496.8     .16       0
  4990.1     .07       0  4996.1     .16       0  5698.9      .1       0
Bank Sta=4990.1,4996.1
XS Rating Curve= 0 ,0
Exp/Cntr=0.3,0.1

Type RM Length L Ch R = 1 ,10719   ,410,410,410
BEGIN DESCRIPTION:
LICK CREEK 24.0
END DESCRIPTION:
XS GIS Cut Line= 2
      3003063.26     10104896.06      3004139.67      10103975.9
#Sta/Elev= 30
  4125.6  868.86  4136.6  868.49  4166.5  867.82  4259.9   859.5  4357.5  850.76
  4404.1  848.02    4406  847.91  4478.3  843.16  4492.5     841    4514  841.44
  4540.7  839.15  4548.3   838.5  4797.7  825.62  4874.7  817.14  4910.8  810.68
  4961.3  810.51  4988.7  805.63  5007.7   805.3  5010.5   804.8  5013.7   805.3
  5053.4  808.06  5066.7  810.29  5095.2  821.64  5158.9  839.35  5187.4  845.73
  5244.5  863.85  5293.9  873.84  5336.7  888.35  5365.3  890.96  5541.7  897.35
#Mann= 10 ,-1 , 0
  4125.6      .1       0  4136.6     .05       0  4259.9      .1       0
  4404.1     .16       0    4406     .05       0  4540.7      .1       0
  4548.3     .05       0  4874.7     .16       0  5007.7     .07       0
  5013.7     .16       0
Bank Sta=5007.7,5013.7
XS Rating Curve= 0 ,0
Exp/Cntr=0.3,0.1

Type RM Length L Ch R = 1 ,10309   ,448,448,448
BEGIN DESCRIPTION:
LICK CREEK 23.0
END DESCRIPTION:
XS GIS Cut Line= 3
      3003449.54     10105095.71      3004252.52     10104396.91
      3004364.42     10104241.96
#Sta/Elev= 30
  4269.2  860.15  4340.7  851.08  4453.7  841.98  4482.2  841.83    4560  835.35
  4668.7  829.76  4687.8  828.73  4823.6  815.27  4843.9  813.89  4900.9  805.16
  4959.4  805.22  4975.8  805.02  4978.5  804.52  4981.8  805.02  5021.5  806.49
  5035.7  809.91  5070.9  823.29  5095.2  825.78    5163  831.44  5205.7  839.35
  5231.1  840.25  5240.2  841.36  5290.2  848.73  5318.7  857.42  5383.6  866.39
  5433.9  869.14  5454.8  873.01  5490.4  875.94  5505.1   880.4  5524.8  882.87
#Mann= 10 ,-1 , 0
  4269.2     .05       0  4668.7      .1       0  4687.8     .05       0
  4823.6     .16       0  4959.4     .12       0  4975.8     .07       0
  4981.8     .12       0  5095.2     .16       0  5231.1     .12       0
  5240.2     .16       0
Bank Sta=4975.8,4981.8
XS Rating Curve= 0 ,0
Exp/Cntr=0.3,0.1

Type RM Length L Ch R = 1 ,9861    ,547,547,547
BEGIN DESCRIPTION:
LICK CREEK 22.0
END DESCRIPTION:
XS GIS Cut Line= 3
      3003753.39     10105429.89      3004452.17     10104774.51
      3004552.01     10104362.15
#Sta/Elev= 30
  4345.8  858.89  4389.2  850.12  4417.5  846.75  4452.7  845.49  4488.3  840.98
  4523.5  841.25    4566  834.71  4576.1  835.03  4748.7  825.77  4834.7   820.2
  4904.9  806.16  4983.4  798.33  5015.8  797.72  5018.5  797.22  5021.8  797.72
  5039.8  800.29  5061.3  800.26  5089.6  803.26  5167.3   820.6  5266.4  825.16
  5366.4  833.22  5476.9  840.17  5500.1  840.25  5541.3  844.62  5560.5  851.06
  5565.7  850.87  5582.4  855.57  5633.9  859.25  5691.1  866.05  5728.1  867.71
#Mann= 6 ,-1 , 0
  4345.8     .05       0  4576.1      .1       0  4748.7     .05       0
  4904.9     .16       0  5015.8     .07       0  5021.8     .16       0
Bank Sta=5015.8,5021.8
XS Rating Curve= 0 ,0
Exp/Cntr=0.3,0.1

Type RM Length L Ch R = 1 ,9314    ,379,379,379
BEGIN DESCRIPTION:
LICK CREEK 21.0
END DESCRIPTION:
XS GIS Cut Line= 4
      3003782.79     10105462.45       3004352.2      10105455.5
      3004623.03     10105413.84       3005364.8      10104935.5
#Sta/Elev= 30
  4259.9  857.08  4325.6  841.54  4486.4  835.27  4567.6  829.43  4679.4   826.9
  4726.9  823.88  4765.6  823.51  4845.8  813.88  4877.6   803.5  4935.7  794.25
  4945.2  792.37    5001   782.4  5003.8   781.9    5007   782.4  5027.9  791.02
  5048.2  794.02  5067.3  795.81  5121.7  794.83  5144.6  792.11  5250.6  800.33
  5316.9  805.71  5389.5  816.57  5425.8  819.78  5534.1  823.34  5713.5  831.57
  5874.7  838.38  5945.9  843.52  5976.3  850.09  5982.2  849.26    5986  852.15
#Mann= 11 ,-1 , 0
  4259.9     .05       0  4486.4      .1       0  4679.4     .16       0
  4726.9     .05       0  4945.2     .16       0    5001     .07       0
    5007     .16       0  5250.6     .05       0  5534.1      .1       0
  5713.5     .05       0  5874.7     .16       0
#XS Ineff= 1 ,-1
 5083.64 5412.95  803.13
Permanent Ineff=
       F
Bank Sta=4935.7,5048.2
XS Rating Curve= 0 ,0
Exp/Cntr=0.3,0.1

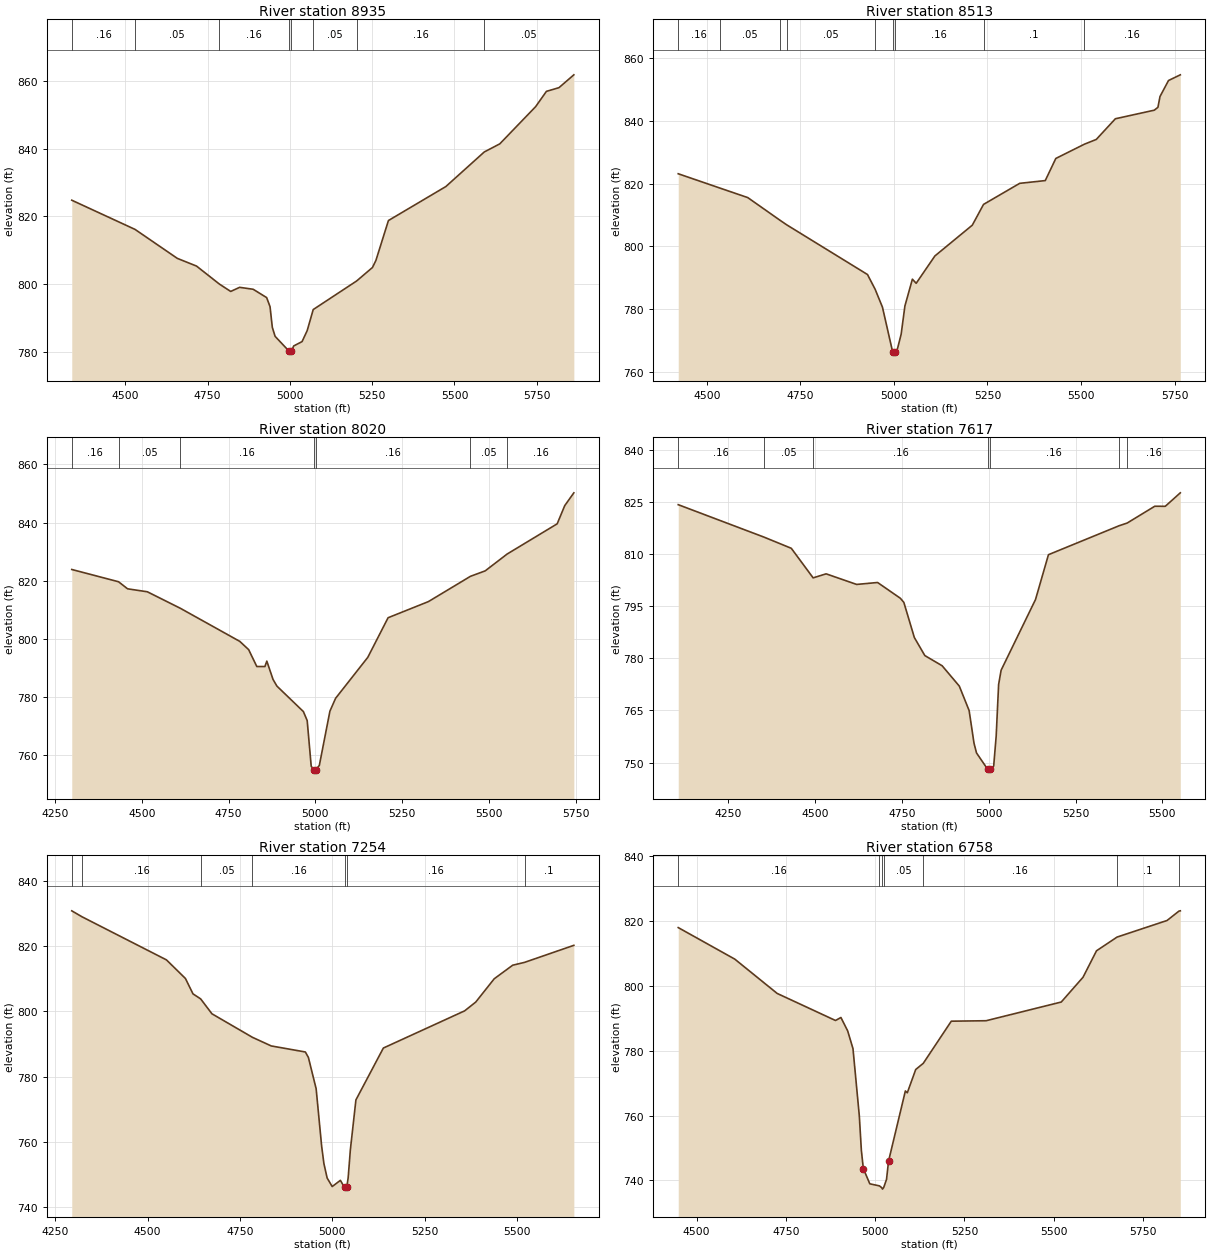
Type RM Length L Ch R = 1 ,8935    ,422,422,422
BEGIN DESCRIPTION:
LICK CREEK 20.0
END DESCRIPTION:
XS GIS Cut Line= 4
      3004268.83     10105896.48      3004744.56     10105809.67
      3004824.42     10105465.92      3005483.79     10105264.64
#Sta/Elev= 30
    4337  824.79  4529.3  816.17  4657.8  807.62  4716.1  805.35  4785.6  800.04
    4820  797.86  4847.2  799.07  4888.3   798.5  4929.3  796.04  4939.6  793.36
  4946.5  787.27    4955   784.6  4998.2  780.15    5001  779.65  5004.2  780.15
  5011.5  781.77  5036.9  783.05  5052.5   786.3  5070.8  792.51  5202.8  800.95
  5250.9  804.93  5261.4  807.03  5299.4  818.79  5473.9  828.82  5590.7  839.03
  5637.8  841.42  5746.8  852.41  5779.6  856.92  5817.7  858.01  5862.9   861.8
#Mann= 8 ,-1 , 0
    4337     .16       0  4529.3     .05       0  4785.6     .16       0
  4998.2     .07       0  5004.2     .16       0  5070.8     .05       0
  5202.8     .16       0  5590.7     .05       0
Bank Sta=4998.2,5004.2
XS Rating Curve= 0 ,0
Exp/Cntr=0.3,0.1

Type RM Length L Ch R = 1 ,8513    ,493,493,493
BEGIN DESCRIPTION:
LICK CREEK 19.0
END DESCRIPTION:
XS GIS Cut Line= 3
      3004282.73     10105983.28      3005178.59     10105965.92
      3005581.38     10105774.94
#Sta/Elev= 30
  4423.6  823.16  4535.6  818.57  4609.4  815.56  4695.3  808.35  4713.6  806.86
  4929.4  791.02  4949.9   786.3  4969.4   780.6  4996.4  766.45  4999.2  765.95
  5002.4  766.45  5009.4  767.29  5019.4  772.01  5029.4     781  5049.4  789.53
  5059.5  788.22  5109.5  796.94  5209.5  806.76  5239.5  813.38  5336.2   820.1
  5404.5  820.98  5432.7  828.04    5509  832.58  5540.8   834.1  5591.9   840.7
  5695.8  843.43  5705.6  844.35  5711.1  847.79  5733.9   852.9  5765.4  854.71
#Mann= 9 ,-1 , 0
  4423.6     .16       0  4535.6     .05       0  4695.3     .16       0
  4713.6     .05       0  4949.9     .16       0  4996.4     .07       0
  5002.4     .16       0  5239.5      .1       0    5509     .16       0
Bank Sta=4996.4,5002.4
XS Rating Curve= 0 ,0
Exp/Cntr=0.3,0.1

Type RM Length L Ch R = 1 ,8020    ,403,403,403
BEGIN DESCRIPTION:
LICK CREEK 18.0
END DESCRIPTION:
XS GIS Cut Line= 3
      3004202.92     10106031.92      3004560.53     10106358.28
      3005442.45     10106743.68
#Sta/Elev= 30
  4298.1  823.87  4432.8  819.65  4458.9  817.22  4515.7   816.2  4611.1  810.51
  4782.3  799.13  4807.8  796.29  4831.2  790.49  4854.6  790.48  4860.1  792.35
    4878  786.04  4889.1  783.76  4965.5  774.98  4976.4  771.89    4988  756.18
  4995.3     755    4998   754.5  5001.3     755  5011.4  756.47  5041.9  775.13
  5058.2  779.55    5151  793.64  5209.5  807.27  5325.7  812.82  5446.7  821.51
  5489.4   823.4  5552.5  829.18  5696.7  839.58  5718.5  845.84  5744.7  850.24
#Mann= 7 ,-1 , 0
  4298.1     .16       0  4432.8     .05       0  4611.1     .16       0
  4995.3     .07       0  5001.3     .16       0  5446.7     .05       0
  5552.5     .16       0
Bank Sta=4995.3,5001.3
XS Rating Curve= 0 ,0
Exp/Cntr=0.3,0.1

Type RM Length L Ch R = 1 ,7617    ,363,363,363
BEGIN DESCRIPTION:
LICK CREEK 17.0
END DESCRIPTION:
XS GIS Cut Line= 5
      3004150.84     10106045.82      3004456.37     10106458.98
      3004484.14     10106691.61      3004706.37     10106920.78
      3005081.36     10106969.39
#Sta/Elev= 30
  4106.2  824.21  4352.5   814.9  4431.7  811.66  4494.6  803.15  4531.9  804.31
  4619.9  801.26  4680.1  801.82  4745.7  797.28  4755.8  796.08    4786  785.98
  4816.2  780.79    4866  777.86  4915.4  772.01  4943.7  764.97  4957.8  755.55
    4965  752.77  4997.3  748.04    5000  747.54  5003.3  748.04  5014.4  748.98
  5021.6  757.67  5028.6  772.48  5035.8  776.58  5134.8  796.91  5172.1  809.82
  5374.8  818.12  5398.8  818.93  5478.2  823.76  5508.4  823.74  5551.7  827.62
#Mann= 7 ,-1 , 0
  4106.2     .16       0  4352.5     .05       0  4494.6     .16       0
  4997.3     .07       0  5003.3     .16       0  5374.8      .1       0
  5398.8     .16       0
Bank Sta=4997.3,5003.3
XS Rating Curve= 0 ,0
Exp/Cntr=0.3,0.1

Type RM Length L Ch R = 1 ,7254    ,496,496,496
BEGIN DESCRIPTION:
LICK CREEK 16.0
END DESCRIPTION:
XS GIS Cut Line= 4
      3003678.63     10106747.18      3004206.37      10106868.7
      3004348.73     10107077.03      3004914.06     10107066.63
#Sta/Elev= 30
  4294.9  830.79  4322.9  828.95  4551.3  815.76  4602.6  810.07  4623.1  805.35
  4643.8  803.82  4674.4  799.25  4783.9  792.05    4835   789.4  4927.3  787.55
  4935.5  785.89  4956.5   776.3  4971.4  758.73  4977.5  753.38  4986.3  748.95
    5000  746.33  5022.2  748.23  5033.3  746.04  5036.1  745.54  5039.3  746.04
  5043.2     749  5049.2  757.64  5064.2  772.87  5138.5  788.76  5358.6  800.15
  5388.6  802.84  5438.6  809.97  5488.6  814.13  5520.7     815  5654.2  820.22
#Mann= 7 ,-1 , 0
  4294.9      .1       0  4322.9     .16       0  4643.8     .05       0
  4783.9     .16       0  5033.3     .07       0  5039.3     .16       0
  5520.7      .1       0
Bank Sta=5033.3,5039.3
XS Rating Curve= 0 ,0
Exp/Cntr=0.3,0.1

Type RM Length L Ch R = 1 ,6758    ,858,858,858
BEGIN DESCRIPTION:
LICK CREEK 15.0
END DESCRIPTION:
XS GIS Cut Line= 4
      3003782.75     10107427.72      3004230.67     10107511.06
      3004379.98     10107163.84      3004949.46      10107104.8
#Sta/Elev= 30
  4448.6  817.96    4607  808.23  4725.7  797.65  4889.1   789.3  4904.2  790.23
  4923.1  786.11    4938  780.62  4955.7  759.92  4961.5  749.22    4967  743.63
  4985.1  738.93  5012.1  738.29    5018  737.79  5020.8  737.29    5024  737.79
  5031.9  740.27  5037.6  745.91  5084.7  767.57  5090.1     767  5113.7  774.19
  5134.9   776.1  5213.3  789.09  5310.8  789.23  5521.3     795  5582.3  802.65
    5620   810.8  5677.5  815.03  5817.6  820.15  5851.1  823.06  5854.7  823.13
#Mann= 7 ,-1 , 0
  4448.6     .16       0  5012.1     .05       0    5018     .07       0
    5024     .05       0  5134.9     .16       0  5677.5      .1       0
  5851.1     .16       0
Bank Sta=4967,5037.6
XS Rating Curve= 0 ,0
Exp/Cntr=0.3,0.1

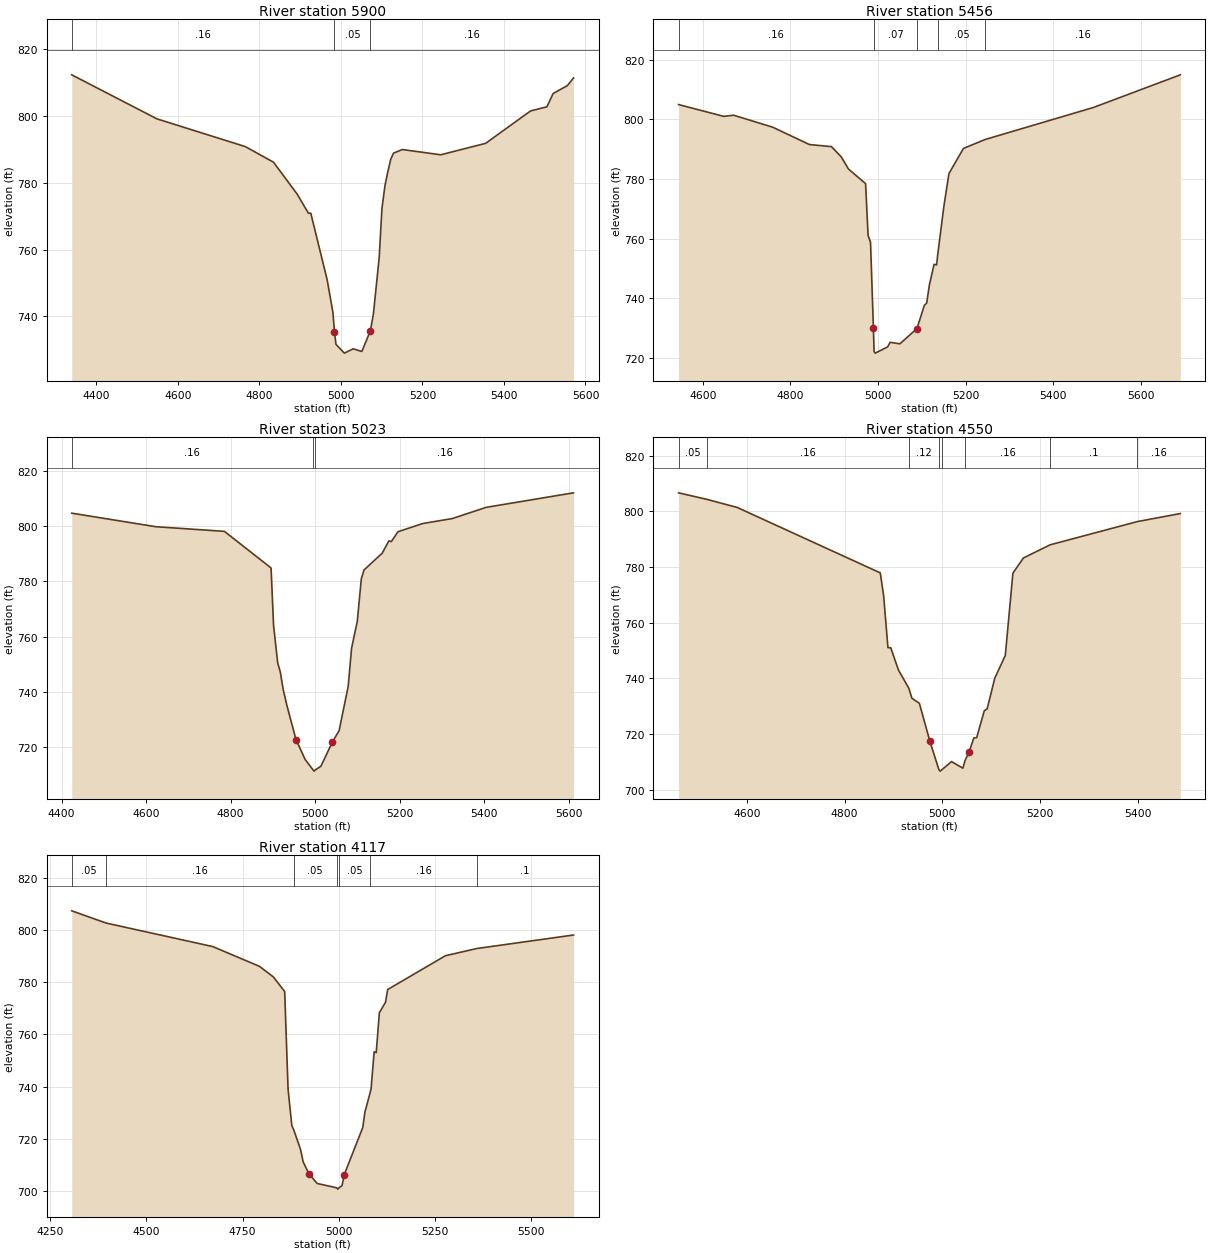
Type RM Length L Ch R = 1 ,5900    ,444,444,444
BEGIN DESCRIPTION:
LICK CREEK 13.0
END DESCRIPTION:
XS GIS Cut Line= 4
      3003841.81     10107535.37      3004418.17     10107622.17
      3004650.81     10107833.98      3004983.78     10107851.32
#Sta/Elev= 30
  4339.8  812.38  4548.8  799.19  4765.7  790.88  4834.7  786.21  4892.6  776.68
  4920.3  770.93  4926.2  770.93  4966.3     751  4980.4  741.26 4984.32  735.39
  4987.9  731.66  5008.6  729.03  5030.4  730.32  5051.4  729.53  5072.3   735.7
  5079.8  740.78    5094  757.68  5100.7  772.34  5108.1  779.18  5114.9  783.18
  5122.3  787.09  5129.1  788.92  5150.7  790.01  5244.9  788.43  5355.1  791.86
  5465.2  801.56  5505.3   802.8  5520.7  806.79  5555.4  809.14  5570.7  811.45
#Mann= 3 , 0 , 0
  4339.8     .16       0 4984.32     .05       0  5072.3     .16       0
Bank Sta=4984.32,5072.3
XS Rating Curve= 0 ,0
Exp/Cntr=0.3,0.1

Type RM Length L Ch R = 1 ,5456    ,433,433,433
BEGIN DESCRIPTION:
LICK CREEK 12.0
END DESCRIPTION:
XS GIS Cut Line= 3
      3003886.94      10107844.4      3004570.95     10108188.14
      3004942.44     10108267.99
#Sta/Elev= 30
  4544.6  804.92    4648  800.95  4670.3  801.35  4759.6  797.33  4843.3  791.53
  4893.6  790.83  4915.9  787.42  4932.6  783.31  4971.6  778.44  4977.3  761.12
  4982.9  758.73 4989.43  730.26    4991  722.18  4993.7  721.68  5021.9  723.77
  5027.6  725.31  5049.9  724.79  5088.9  729.91  5105.7  737.68  5111.2  738.49
  5117.1   744.4    5128  751.43  5133.6   751.2  5136.5   754.9  5150.3   770.8
  5161.9  781.81    5195  790.22  5244.6  793.22  5491.7  803.94  5690.1  814.87
#Mann= 5 ,-1 , 0
  4544.6     .16       0    4991     .07       0  5088.9     .16       0
  5136.5     .05       0  5244.6     .16       0
Bank Sta=4989.43,5088.9
XS Rating Curve= 0 ,0
Exp/Cntr=0.3,0.1

Type RM Length L Ch R = 1 ,5023    ,473,473,473
BEGIN DESCRIPTION:
LICK CREEK 11.0
END DESCRIPTION:
XS GIS Cut Line= 4
      3003803.59     10108004.11      3003970.25     10108340.92
      3004338.31     10108552.73      3004725.31     10108545.81
#Sta/Elev= 30
  4424.1  804.66  4622.8  799.76  4785.4  798.08  4895.8  784.83  4901.7     764
  4911.6   750.4  4917.4  747.36  4924.7  740.69  4933.2  735.12  4954.7  722.77
  4976.3  715.59  4994.9  711.83  4997.6  711.33  5000.9  711.83  5013.7  713.08
    5041   721.9  5056.8  725.95  5078.3     742  5086.3  755.77  5099.9  765.59
  5109.3  780.84  5115.7  784.11  5158.8  790.19  5174.6  794.64  5180.4  794.38
  5196.2  797.95  5254.7  800.91  5324.7  802.71  5404.7  806.76  5611.6  812.02
#Mann= 3 ,-1 , 0
  4424.1     .16       0  4994.9     .07       0  5000.9     .16       0
Bank Sta=4954.7,5041
XS Rating Curve= 0 ,0
Exp/Cntr=0.3,0.1

Type RM Length L Ch R = 1 ,4550    ,433,433,433
BEGIN DESCRIPTION:
LICK CREEK 10.0
END DESCRIPTION:
XS GIS Cut Line= 3
      3003456.37     10108570.09      3004095.25     10108945.09
      3004369.57     10108861.75
#Sta/Elev= 30
  4459.9  806.64  4518.5  804.27  4579.9  801.39    4873  777.87  4879.8  769.79
  4888.7  751.02  4894.5  750.96  4910.2  742.97  4931.6  736.38  4937.7  732.84
  4953.1  730.99  4974.6  717.35  4993.1  707.13  4995.8  706.63  4999.1  707.13
  5018.9  710.06  5042.1  707.69  5046.8  710.54  5054.7  713.45  5064.6  718.55
  5070.4  718.67    5086  728.33  5091.8  728.99  5107.5  740.04    5129   748.2
  5144.6  777.78  5166.1  783.23  5220.7  787.95  5399.5  796.31  5487.4  799.19
#Mann= 8 ,-1 , 0
  4459.9     .05       0  4518.5     .16       0  4931.6     .12       0
  4993.1     .07       0  4999.1     .12       0  5046.8     .16       0
  5220.7      .1       0  5399.5     .16       0
Bank Sta=4974.6,5054.7
XS Rating Curve= 0 ,0
Exp/Cntr=0.3,0.1

Type RM Length L Ch R = 1 ,4117    ,445,445,445
BEGIN DESCRIPTION:
LICK CREEK 9.0
END DESCRIPTION:
XS GIS Cut Line= 4
       3003192.5      10109306.2      3003675.12     10109333.98
      3004067.48     10109174.25      3004359.18     10108903.39
#Sta/Elev= 30
  4305.7  807.27  4395.1  802.59  4672.3  793.59  4793.6  786.04    4830  781.97
  4859.5  776.38  4868.3  739.04  4878.1     725  4882.5  723.66  4900.7  715.93
  4907.6  711.16  4922.3  706.63  4943.9  702.89  4994.9  701.22  4997.6  700.72
  5000.9  701.22  5008.7  702.07  5014.6  706.31  5062.6  724.33  5068.1  730.14
    5081  737.23  5084.2  739.11  5092.2  753.31  5097.6  752.99  5105.8  768.27
  5121.7  772.25  5127.4  777.14  5277.6  790.08  5359.6  792.85  5610.8  798.01
#Mann= 7 ,-1 , 0
  4305.7     .05       0  4395.1     .16       0  4882.5     .05       0
  4994.9     .04       0  5000.9     .05       0    5081     .16       0
  5359.6      .1       0
Bank Sta=4922.3,5014.6
XS Rating Curve= 0 ,0
Exp/Cntr=0.3,0.1