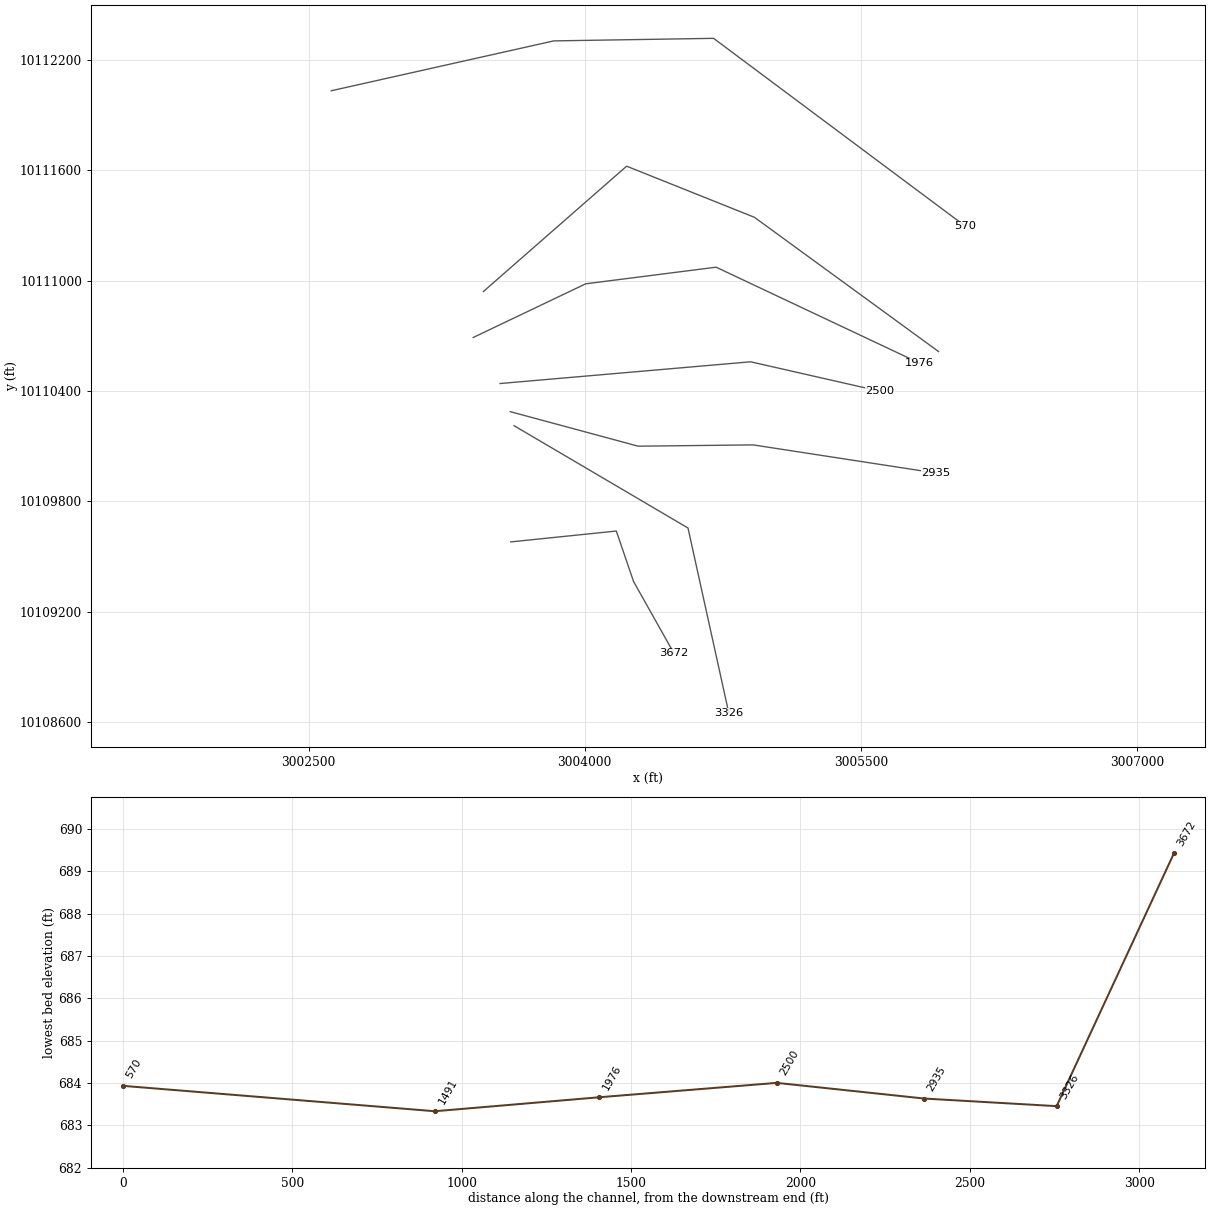
HEC-RAS study LICK CREEK.prj: LICK CREEK Base Level Engineering

--- LICK CREEK.g01 (geometry) --- (continued)

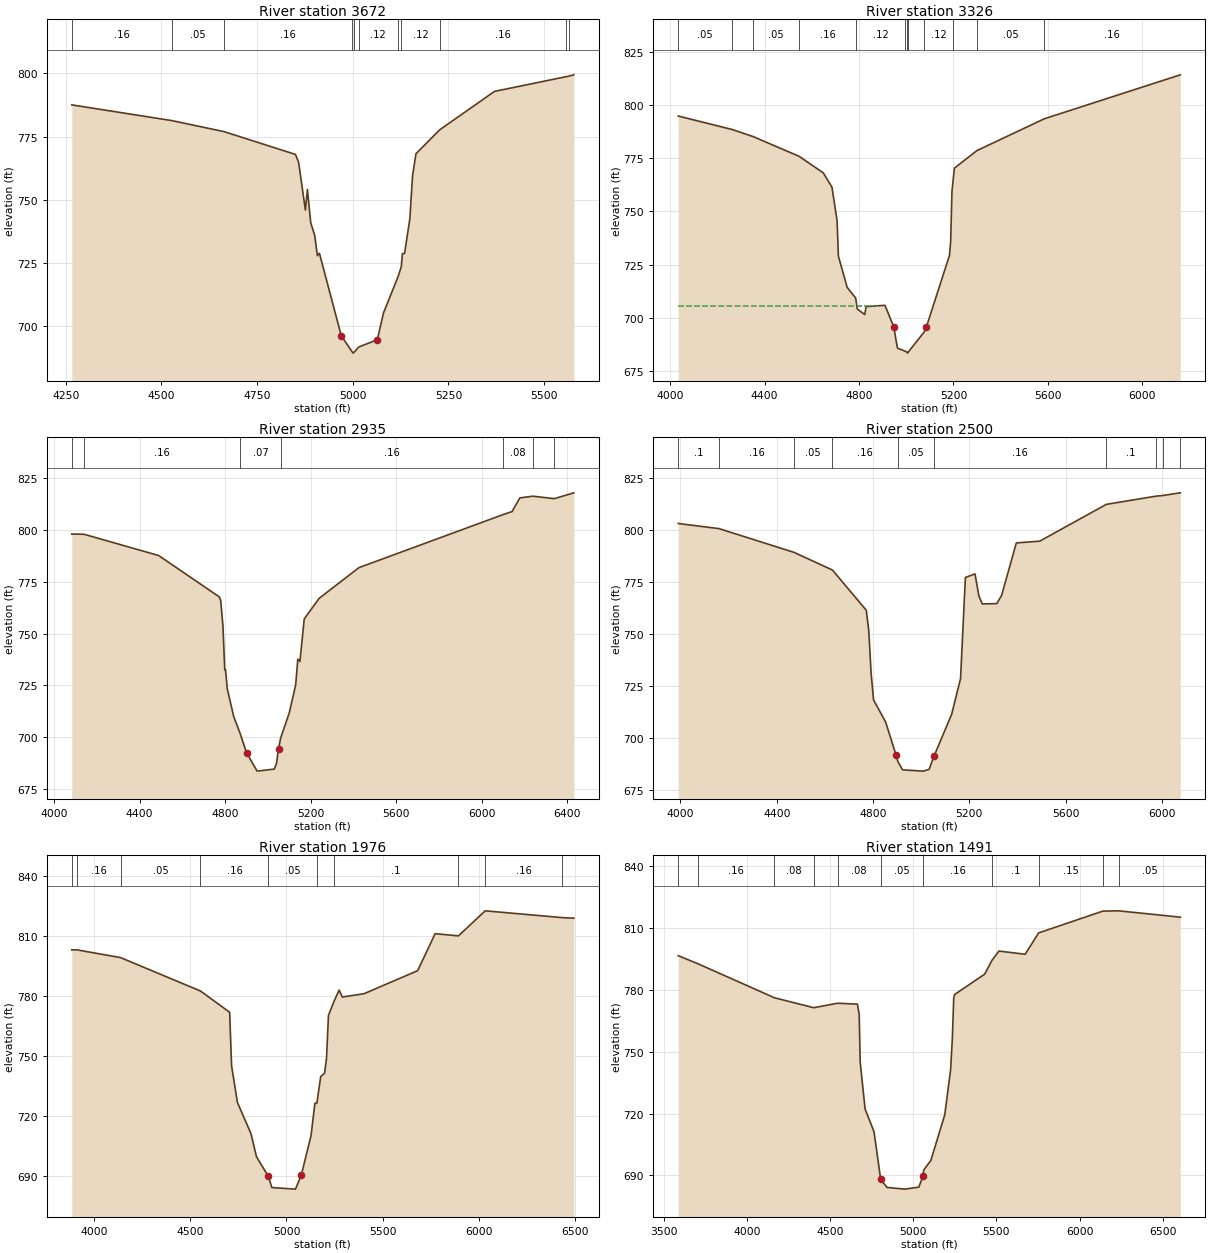
Type RM Length L Ch R = 1 ,3672    ,346,346,346
BEGIN DESCRIPTION:
LICK CREEK 8.0
END DESCRIPTION:
XS GIS Cut Line= 4
      3003598.72      10109580.5      3004171.64     10109639.53
      3004265.39     10109365.23      3004484.13     10108976.37
#Sta/Elev= 30
  4265.6  787.55  4527.3  781.33  4663.2  776.99  4850.1  767.97  4858.3  764.91
  4876.1  745.98  4881.4  754.11    4890  740.98  4900.5   735.9  4907.4  727.95
  4912.7  728.91    4970  696.23  4998.4  689.92  5001.1  689.42  5004.4  689.92
  5015.6  691.87    5064  694.68  5080.2  705.32    5118  719.54  5126.7   723.6
  5129.6  728.78  5135.2  728.78  5149.1  742.58  5156.1  759.53  5165.1  768.24
  5227.2  777.71  5370.3  792.88  5557.8  798.71  5563.8  798.89  5577.6  799.43
#Mann= 11 ,-1 , 0
  4265.6     .16       0  4527.3     .05       0  4663.2     .16       0
  4998.4     .07       0  5004.4     .16       0  5015.6     .12       0
    5118     .16       0  5126.7     .12       0  5227.2     .16       0
  5557.8      .1       0  5563.8     .16       0
Bank Sta=4970,5064
XS Rating Curve= 0 ,0
Exp/Cntr=0.3,0.1

Type RM Length L Ch R = 1 ,3326    ,391,391,391
BEGIN DESCRIPTION:
LICK CREEK 7.0
END DESCRIPTION:
XS GIS Cut Line= 3
      3003616.51     10110211.59      3004560.97     10109656.02
      3004783.18      10108649.1
#Sta/Elev= 30
    4034   794.8  4263.2  788.45  4351.6  785.13  4546.2  775.87  4648.2  768.14
  4685.3  761.39  4706.8  745.72  4712.6  728.94  4749.7  714.32  4785.6  709.33
  4792.7  704.15    4824  701.56  4829.8  705.32  4909.8  705.89    4947  695.78
  4962.6  685.81  4996.7  684.31  5002.5  683.95  5005.3  683.45  5008.5  683.95
  5075.5  693.32  5085.6  695.87    5183  729.33  5188.1   735.9  5193.5   759.3
  5199.6  765.81  5203.8   770.3  5299.4  778.58  5585.2  793.52  6160.9  814.15
#Mann= 12 ,-1 , 0
    4034     .05       0  4263.2     .16       0  4351.6     .05       0
  4546.2     .16       0  4785.6     .12       0  4996.7     .16       0
  5002.5     .07       0  5008.5     .16       0  5075.5     .12       0
  5199.6     .16       0  5299.4     .05       0  5585.2     .16       0
#XS Ineff= 2 , 0
          4882.1  705.76
Permanent Ineff=
       F       F
Bank Sta=4947,5085.6
XS Rating Curve= 0 ,0
Exp/Cntr=0.3,0.1

Type RM Length L Ch R = 1 ,2935    ,435,435,435
BEGIN DESCRIPTION:
LICK CREEK 6.0
END DESCRIPTION:
XS GIS Cut Line= 4
      3003595.73     10110287.96      3004290.13     10110100.47
      3004915.13     10110107.41      3005908.14     10109954.64
#Sta/Elev= 30
  4082.5  798.18  4140.2  798.04  4489.3  787.77  4772.1  767.84  4779.3  766.16
  4789.7  753.74  4798.3  732.62  4801.8  732.62  4810.1  723.41  4840.1  710.02
  4870.1  701.86  4900.1  692.53  4949.9  683.63  5030.1  684.62  5040.1  687.22
  5050.1  694.55  5060.1  699.75  5100.1  711.76  5130.1  725.25  5140.1  737.72
  5150.1  736.63  5170.1  757.17  5240.1  767.11    5426  781.93  6097.8  807.45
  6142.5  809.02  6178.9  815.62  6239.4  816.45  6339.9  815.25  6431.5  818.07
#Mann= 7 ,-1 , 0
  4082.5      .1       0  4140.2     .16       0  4870.1     .07       0
  5060.1     .16       0  6097.8     .08       0  6239.4     .05       0
  6339.9     .16       0
Bank Sta=4900.1,5050.1
XS Rating Curve= 0 ,0
Exp/Cntr=0.3,0.1

Type RM Length L Ch R = 1 ,2500    ,524,524,524
BEGIN DESCRIPTION:
LICK CREEK 5.0
END DESCRIPTION:
XS GIS Cut Line= 3
      3003540.14     10110440.75      3004901.24      10110558.8
      3005602.68     10110399.07
#Sta/Elev= 30
  3990.7   803.1  4159.7  800.64  4471.8  789.22  4631.4  780.71  4771.9  761.36
  4782.2  751.55    4792  730.84  4802.1  718.26  4852.2  707.63  4895.3  691.76
  4902.4  688.76  4922.5  684.62  5008.1     684  5032.9  684.84    5053  691.14
  5126.5  711.35  5163.4   728.5  5183.5  777.13  5223.6  778.86  5239.5  768.31
  5253.7  764.43    5314  764.56    5334  768.53  5395.1  793.75  5492.4  794.61
    5769   812.3  5973.4  816.21  6005.8   816.6  6075.6  817.85  6076.3  817.85
#Mann= 10 ,-1 , 0
  3990.7      .1       0  4159.7     .16       0  4471.8     .05       0
  4631.4     .16       0  4902.4     .05       0    5053     .16       0
    5769      .1       0  5973.4     .16       0  6005.8     .08       0
  6075.6     .16       0
Bank Sta=4895.3,5053
XS Rating Curve= 0 ,0
Exp/Cntr=0.3,0.1

Type RM Length L Ch R = 1 ,1976    ,485,485,485
BEGIN DESCRIPTION:
LICK CREEK 4.0
END DESCRIPTION:
XS GIS Cut Line= 4
      3003394.26     10110690.73      3004005.41     10110982.41
      3004713.74     10111072.69      3005817.92     10110551.85
#Sta/Elev= 30
  3883.1  803.04  3909.4  803.04  4136.8  799.17  4552.6  782.51  4704.5   771.9
  4714.6  745.17  4744.8  726.92  4815.4  711.36  4844.1  699.81  4906.1     690
    4924  684.44    5047  683.66  5077.5  690.75  5127.9  710.34  5148.1  726.54
  5158.1  726.45  5178.3  739.82  5198.5   741.5  5208.5  748.91  5218.6  770.32
  5245.9     777  5274.2  782.97  5290.6  779.51  5403.8  781.15  5682.6  792.65
  5773.7  811.11  5894.7  809.99    6034   822.5    6436  819.11  6495.2  818.83
#Mann= 10 ,-1 , 0
  3883.1      .1       0  3909.4     .16       0  4136.8     .05       0
  4552.6     .16       0  4906.1     .05       0  5158.1     .16       0
  5245.9      .1       0  5894.7     .08       0    6034     .16       0
    6436     .05       0
Bank Sta=4906.1,5077.5
XS Rating Curve= 0 ,0
Exp/Cntr=0.3,0.1

Type RM Length L Ch R = 1 ,1491    ,921,921,921
BEGIN DESCRIPTION:
LICK CREEK 3.0
END DESCRIPTION:
XS GIS Cut Line= 4
      3003449.83     10110940.73      3004227.63      10111621.3
      3004922.08     10111343.52       3005922.1     10110614.34
#Sta/Elev= 30
    3587  796.55  3705.9  792.62  4165.6  776.14  4402.1  771.32    4545  773.49
  4664.5  773.05  4675.3  768.02    4681  745.11  4710.6  722.21  4764.4  711.12
  4804.5  688.02  4842.5  684.15    4950  683.33  5033.7  684.31  5057.9   689.5
  5063.3  692.63  5106.1  697.23  5189.9  719.44  5224.9  741.33  5235.3  756.28
  5243.7  776.17  5249.1  777.72  5429.8   787.6  5473.8  794.31  5515.5   798.8
  5673.4  797.24    5754  807.59    6140  818.16  6235.1  818.31  6606.1  815.24
#Mann= 11 ,-1 , 0
    3587     .05       0  3705.9     .16       0  4165.6     .08       0
  4402.1     .16       0    4545     .08       0  4804.5     .05       0
  5057.9     .16       0  5473.8      .1       0    5754     .15       0
    6140     .16       0  6235.1     .05       0
Bank Sta=4804.5,5057.9
XS Rating Curve= 0 ,0
Exp/Cntr=0.3,0.1

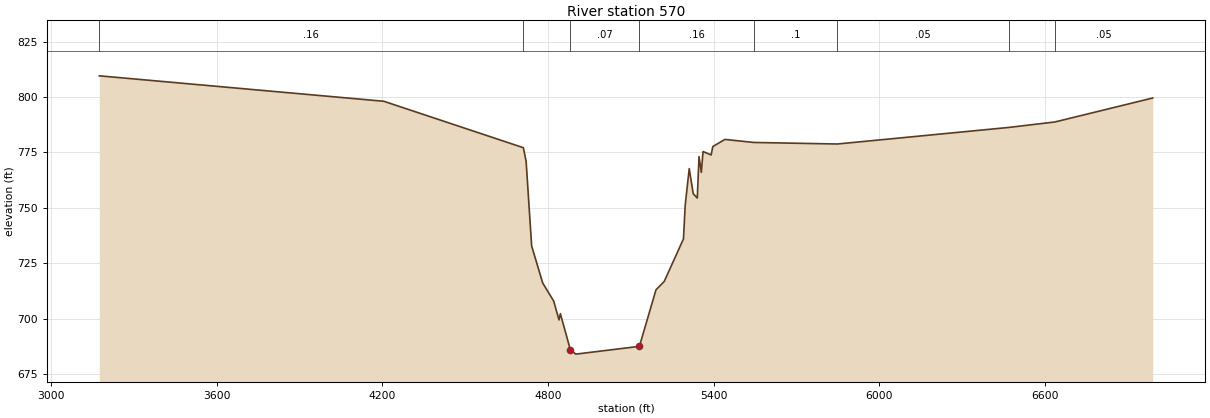
Type RM Length L Ch R = 1 ,570     ,0,0,0
BEGIN DESCRIPTION:
LICK CREEK 1.0
END DESCRIPTION:
XS GIS Cut Line= 4
      3002623.48     10112031.03       3003831.8     10112301.86
      3004699.85     10112315.75       3006067.9     10111294.92
#Sta/Elev= 30
  3175.8  809.58  4205.7  798.09  4710.8  777.13  4720.8  770.97  4740.8  732.77
  4780.8  716.05  4820.7  707.86  4839.8  699.38  4844.8  702.19  4880.8  685.96
  4900.6  683.93  5130.9  687.44  5190.9  712.96  5220.9  716.78  5290.4  735.95
  5296.6  751.01  5311.2  767.68  5325.8  756.33  5340.4  754.41  5346.7  773.08
    5355     766  5361.3   775.4  5390.5  773.85  5396.7  777.66  5440.5  780.87
  5545.5  779.49  5847.6   778.8  6467.4  786.27  6634.9  788.74  6989.2  799.57
#Mann= 8 ,-1 , 0
  3175.8     .16       0  4710.8     .16       0  4880.8     .07       0
  5130.9     .16       0  5545.5      .1       0  5847.6     .05       0
  6467.4     .16       0  6634.9     .05       0
Bank Sta=4880.8,5130.9
XS Rating Curve= 0 ,0
Exp/Cntr=0.3,0.1

Chan Stop Cuts=-1
Use User Specified Reach Order=0
Composite Channel Slope=5