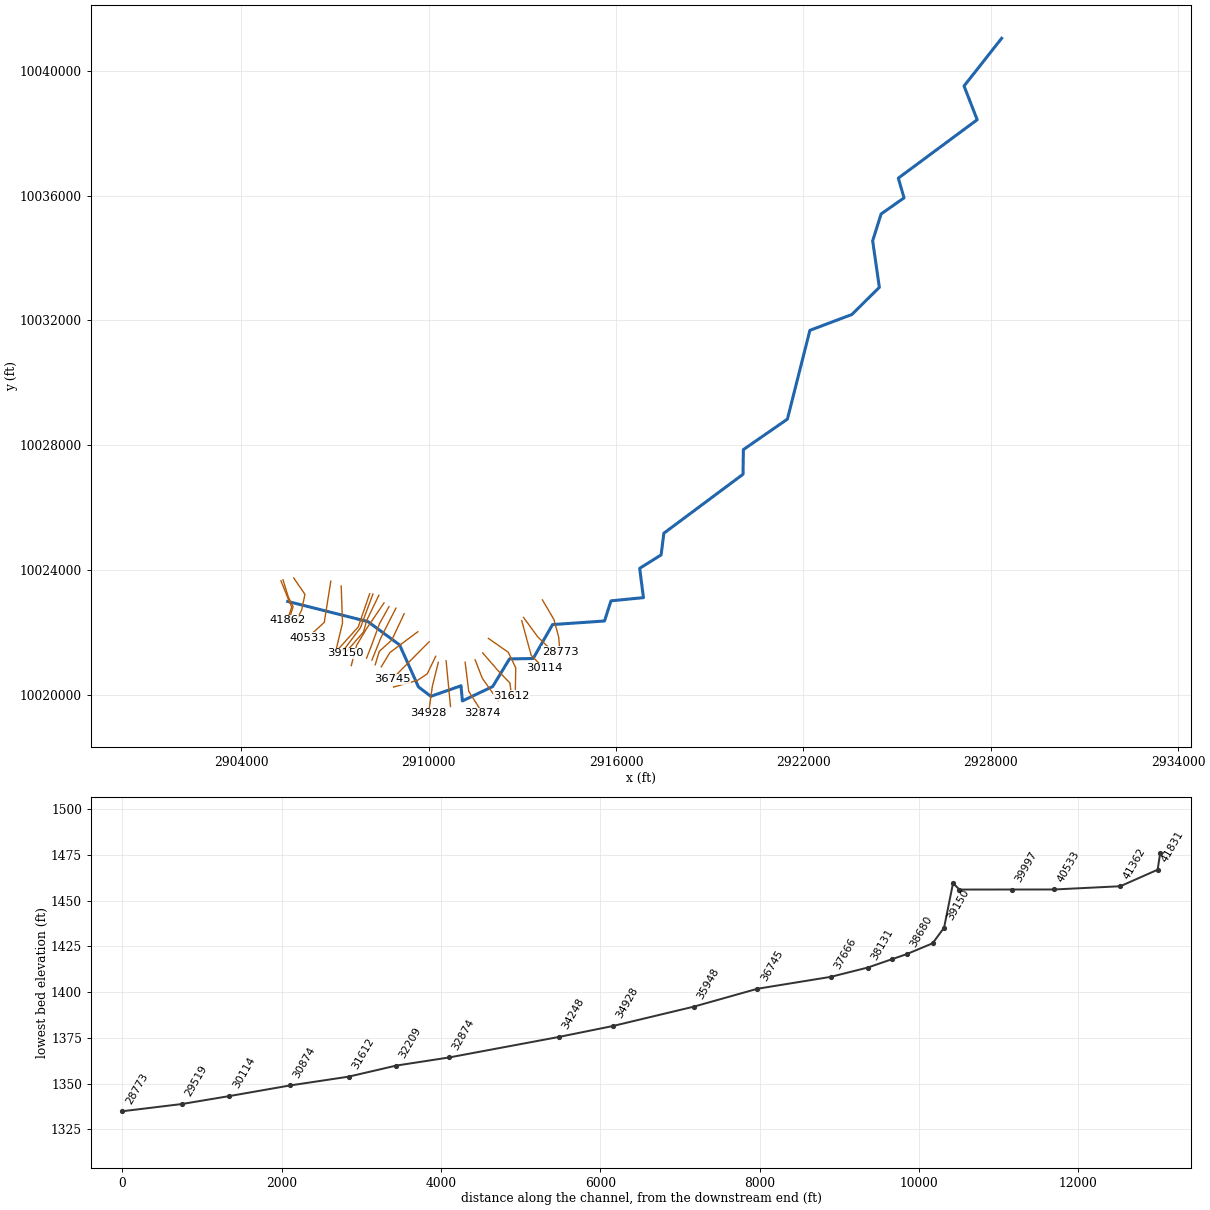
--- MCCALL CREEK.prj (project) ---

Proj Title=MCCALL CREEK Base Level Engineering
Current Plan=p01
Default Exp/Contr=0.3,0.1
English Units
Geom File=g01
Flow File=f01
Plan File=p01
Y Axis Title=Elevation
X Axis Title(PF)=Main Channel Distance
X Axis Title(XS)=Station
BEGIN DESCRIPTION:
MCCALL CREEK
END DESCRIPTION:
DSS Export Rating Curves= 0
DSS Export Rating Curve Sorted= 0
DSS Export Volume Flow Curves= 0
DXF OffsetX= 0
DXF OffsetY= 0
DXF ScaleX= 1
DXF ScaleY= 10

--- MCCALL CREEK.p01 (plan) ---

Plan Title=Multiple Run
Short Identifier=Multiple
Geom File=g01
Flow File=f01
Subcritical Flow
K Sum by GR= 0
Std Step Tol= 0.01
Critical Tol= 0.01
Num of Std Step Trials= 20
Max Error Tol= 0.3
Flow Tol Ratio= 0.001
Split Flow NTrial= 30
Split Flow Tol= 0.02
Split Flow Ratio= 0.02
Log Output Level= 0
Friction Slope Method= 1
Unsteady Friction Slope Method= 2
Unsteady Bridges Friction Slope Method= 1
Parabolic Critical Depth
Global Vel Dist=  1 , 1 , 1
Global Log Level= 0
CheckData=True
Encroach Param= -1, 0, 0, 0
BEGIN DESCRIPTION:
Multiple Run
END DESCRIPTION:

--- MCCALL CREEK.f01 (steady flow) ---

Flow Title=Multiple
Program Version=4.10
Number of Profiles= 7
Profile Names=10-year,25-year,50-year,1pct_min,100-year,1pct_plu,500-year
River Rch & RM=MCCALL CREEK,Reach-1         ,41862
    1045    1528    1954    1830    2475    3347    3982
River Rch & RM=MCCALL CREEK,Reach-1         ,40533
    1166    1712    2192    2056    2780    3760    4485
River Rch & RM=MCCALL CREEK,Reach-1         ,38438
    1752    2617    3392    3213    4345    5876    7155
River Rch & RM=MCCALL CREEK,Reach-1         ,30114
    2151    3242    4225    4022    5439    7356    9047
River Rch & RM=MCCALL CREEK,Reach-1         ,26630
    2620    3980    5215    4986    6743    9118   11317
River Rch & RM=MCCALL CREEK,Reach-1         ,20634
    3551    5465    7222    6958    9410   12726   16041
River Rch & RM=MCCALL CREEK,Reach-1         ,17393
    4379    6798    9036    8752   11837   16008   20393
River Rch & RM=MCCALL CREEK,Reach-1         ,16695
    4379    6798    9036    8752   11837   16008   20393
River Rch & RM=MCCALL CREEK,Reach-1         ,15331
    4545    7057    9381    9085   12287   16617   21164
River Rch & RM=MCCALL CREEK,Reach-1         ,12634
    4772    7415    9863    9555   12922   17476   22273
River Rch & RM=MCCALL CREEK,Reach-1         ,9792
    4961    7708   10252    9930   13429   18161   23136
River Rch & RM=MCCALL CREEK,Reach-1         ,5183
    5137    7989   10632   10302   13932   18841   24023
River Rch & RM=MCCALL CREEK,Reach-1         ,3416
    5224    8120   10803   10464   14151   19137   24378
Boundary for River Rch & Prof#=MCCALL CREEK,Reach-1         , 1
Up Type= 0
Dn Type= 3
Dn Slope=0.008
Boundary for River Rch & Prof#=MCCALL CREEK,Reach-1         , 2
Up Type= 0
Dn Type= 3
Dn Slope=0.008
Boundary for River Rch & Prof#=MCCALL CREEK,Reach-1         , 3
Up Type= 0
Dn Type= 3
Dn Slope=0.008
Boundary for River Rch & Prof#=MCCALL CREEK,Reach-1         , 4
Up Type= 0
Dn Type= 3
Dn Slope=0.008
Boundary for River Rch & Prof#=MCCALL CREEK,Reach-1         , 5
Up Type= 0
Dn Type= 3
Dn Slope=0.008
Boundary for River Rch & Prof#=MCCALL CREEK,Reach-1         , 6
Up Type= 0
Dn Type= 3
Dn Slope=0.008
Boundary for River Rch & Prof#=MCCALL CREEK,Reach-1         , 7
Up Type= 0
Dn Type= 3
Dn Slope=0.008
DSS Import GetInterval= 0
DSS Import GetPeak= 0
DSS Import FillOption= 0

--- MCCALL CREEK.g01 (geometry) ---

Geom Title=Existing Conditions
Program Version=4.10

River Reach=MCCALL CREEK    ,Reach-1
Reach XY= 30
        2905489.     10023002.07      2908055.51      10022356.9
      2909071.06     10021610.28      2909674.36     10020266.58
      2910071.41     10019963.45       2911037.5       10020301.
      2911082.17      10019815.7       2912052.4     10020278.02
      2912589.45      10021161.3      2913348.92     10021174.81
      2913969.19     10022261.46       2915632.8      10022375.9
      2915839.52     10023021.18      2916878.56      10023124.1
      2916759.22     10024063.42      2917444.04     10024490.75
        2917533.      10025186.7      2920068.31     10027074.34
      2920079.08     10027863.47      2921488.13     10028838.87
      2922209.05     10031683.54        2923553.     10032189.66
      2924433.71     10033060.99      2924218.23     10034547.85
      2924489.18     10035409.03      2925224.77     10035925.32
      2925040.34     10036556.83      2927566.17     10038427.29
       2927145.6     10039507.71      2928348.47     10041033.73

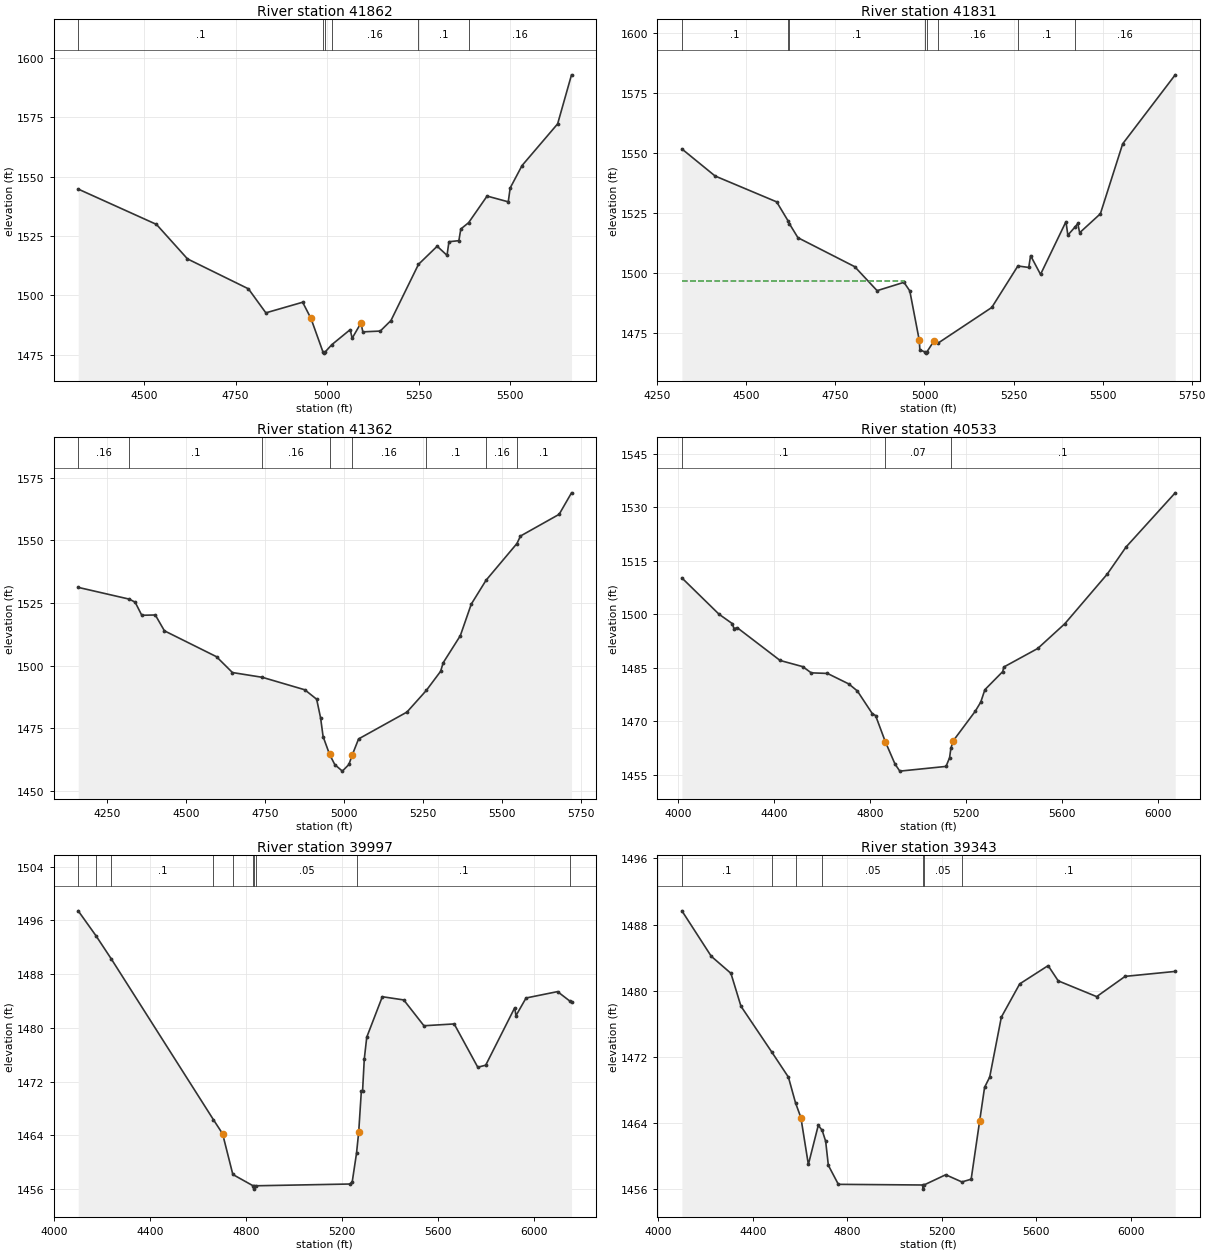
Type RM Length L Ch R = 1 ,41862   ,31,31,31
BEGIN DESCRIPTION:
MCCALL CREEK 83.0
END DESCRIPTION:
XS GIS Cut Line= 4
      2905270.72     10023661.85      2905437.39     10023247.77
      2905614.48      10022825.9      2905481.66     10022404.01
#Sta/Elev= 30
  4320.5 1544.81  4534.1 1529.93  4618.7 1515.41    4785 1502.81  4832.6 1492.69
    4933 1497.16  4955.6 1490.37  4988.4 1476.23  4991.2 1475.73  4994.4 1476.23
  5012.5 1479.28  5062.7 1485.62  5068.1    1482  5091.9 1488.37  5097.3 1484.69
  5144.8 1485.02    5174 1489.46  5249.1 1513.12  5300.1 1520.74    5327 1516.91
  5332.2 1522.64  5359.3 1523.09  5364.6    1528  5385.9 1530.66  5436.3 1541.87
  5494.1 1539.44  5499.3 1545.27  5531.7 1554.72  5628.8 1572.27  5666.7 1592.92
#Mann= 6 ,-1 , 0
  4320.5      .1       0  4988.4     .07       0  4994.4      .1       0
  5012.5     .16       0  5249.1      .1       0  5385.9     .16       0
Bank Sta=4955.6,5091.9
XS Rating Curve= 0 ,0
Exp/Cntr=0.3,0.1

Type RM Length L Ch R = 1 ,41831   ,469,469,469
BEGIN DESCRIPTION:
MCCALL CREEK 82.0
END DESCRIPTION:
XS GIS Cut Line= 4
      2905335.38     10023696.75      2905511.17     10023134.66
      2905658.74     10022835.18      2905526.35     10022392.45
#Sta/Elev= 30
    4319 1551.74  4412.2 1540.49    4585 1529.73  4617.2 1521.79  4620.4 1520.73
  4644.7 1514.83  4804.1 1502.78    4867  1492.8  4942.4 1496.27  4958.8 1492.69
 4985.45 1472.09    4987 1468.22  5000.7 1467.32  5003.4 1466.82  5006.7 1467.32
  5026.1 1471.74  5038.5 1471.02  5188.9 1485.81  5262.2 1503.07  5292.7 1502.45
  5297.9 1507.37  5325.8 1499.56  5397.2  1521.5  5402.5 1515.89  5422.3 1519.23
  5430.4 1520.74  5435.6 1516.89  5493.8 1524.78  5556.4 1553.87  5703.9 1582.57
#Mann= 8 ,-1 , 0
    4319      .1       0  4617.2     .16       0  4620.4      .1       0
  5000.7     .07       0  5006.7      .1       0  5038.5     .16       0
  5262.2      .1       0  5422.3     .16       0
#XS Ineff= 2 , 0
         4942.76 1496.62
Permanent Ineff=
       T       T
Bank Sta=4985.45,5026.1
XS Rating Curve= 0 ,0
Exp/Cntr=0.3,0.1

Type RM Length L Ch R = 1 ,41362   ,829,829,829
BEGIN DESCRIPTION:
MCCALL CREEK 81.0
END DESCRIPTION:
XS GIS Cut Line= 4
       2905680.2     10023755.39      2906039.55     10023229.38
      2905935.39     10022729.38      2905747.88     10022359.58
#Sta/Elev= 30
  4157.6 1531.22  4319.4 1526.52  4337.9 1525.31  4358.9 1520.08  4401.8 1520.19
  4430.7 1513.86  4595.6 1503.52  4646.1 1497.19  4740.9 1495.28  4875.3  1490.3
  4912.8 1486.53  4925.3 1479.06  4933.2 1471.61  4953.6 1464.53  4970.3  1460.4
  4994.2  1457.8  5014.9 1460.45  5025.4 1464.21  5045.6 1470.67  5198.8  1481.4
  5260.1 1490.04  5305.4 1497.68  5313.5 1501.09  5367.8 1511.91  5402.5 1524.53
  5449.2 1534.05  5547.1 1548.74  5558.4 1551.74  5680.8 1560.41    5720    1569
#Mann= 8 ,-1 , 0
  4157.6     .16       0  4319.4      .1       0  4740.9     .16       0
  4953.6     .09       0  5025.4     .16       0  5260.1      .1       0
  5449.2     .16       0  5547.1      .1       0
Bank Sta=4953.6,5025.4
XS Rating Curve= 0 ,0
Exp/Cntr=0.3,0.1

Type RM Length L Ch R = 1 ,40533   ,536,536,536
BEGIN DESCRIPTION:
Mapping XS 38af8499
END DESCRIPTION:
XS GIS Cut Line= 3
      2906867.68     10023651.27      2906659.34     10022333.55
      2906128.11     10021843.99
#Sta/Elev= 30
  4015.4 1510.15  4170.1 1499.99  4225.5 1497.35  4232.5 1495.95  4245.8 1496.22
  4424.8 1487.03  4519.1  1485.3  4554.6 1483.56  4622.1  1483.4  4711.5 1480.44
  4746.8 1478.49  4809.2 1472.13  4822.8  1471.6  4863.3 1464.29  4903.8 1458.01
  4923.8 1456.03  5116.4 1457.35  5131.3 1459.79  5136.7 1462.45  5146.8 1464.55
  5237.9 1472.77  5261.2 1475.36  5278.4 1478.84    5353 1483.93    5357 1485.18
  5498.8 1490.39  5611.7 1497.32  5788.6 1511.23  5866.9 1518.81  6071.9 1533.99
#Mann= 3 ,-1 , 0
  4015.4      .1       0  4863.3     .07       0  5136.7      .1       0
Bank Sta=4863.3,5146.8
XS Rating Curve= 0 ,0
Exp/Cntr=0.3,0.1

Type RM Length L Ch R = 1 ,39997   ,654,654,654
BEGIN DESCRIPTION:
MCCALL CREEK 80.0
END DESCRIPTION:
XS GIS Cut Line= 3
      2907201.01     10023495.03      2907242.68     10022312.72
      2907039.54     10021463.72
#Sta/Elev= 30
  4099.4 1497.42  4173.7  1493.7  4237.7 1490.24    4663 1466.34  4701.1 1464.25
  4743.9 1458.19  4828.1 1456.51  4830.9 1456.01  4834.1 1456.51  4842.2 1456.51
  5231.4 1456.77  5241.4 1457.08  5259.4 1461.36 5268.47 1464.52  5279.4 1470.57
  5284.5 1470.57  5291.7 1475.36    5302 1478.62  5366.9 1484.64  5456.2 1484.16
  5540.3 1480.32  5666.4 1480.59  5764.7 1474.15  5797.7 1474.45  5918.7    1483
  5923.9 1481.82  5965.9 1484.45  6097.2  1485.4  6149.9 1483.95  6155.4 1483.88
#Mann= 10 ,-1 , 0
  4099.4      .1       0  4173.7     .05       0  4237.7      .1       0
    4663     .05       0  4743.9      .1       0  4828.1    .033       0
  4834.1      .1       0  4842.2     .05       0  5259.4      .1       0
  6149.9     .05       0
Bank Sta=4701.1,5268.47
XS Rating Curve= 0 ,0
Exp/Cntr=0.3,0.1

Type RM Length L Ch R = 1 ,39343   ,81,81,81
BEGIN DESCRIPTION:
MCCALL CREEK 79.0
END DESCRIPTION:
XS GIS Cut Line= 3
      2908112.46     10023250.19      2907747.89     10022187.72
      2907102.76     10021469.76
#Sta/Elev= 30
  4099.1 1489.66  4223.4 1484.16  4306.6  1482.1  4349.1 1478.12  4480.9 1472.52
    4550 1469.54  4580.3 1466.41  4602.8 1464.65  4634.5 1458.97  4676.5 1463.72
  4693.1 1463.09  4707.7 1461.78  4719.1 1458.87  4761.4 1456.57  5117.9 1456.49
  5120.6 1455.99  5123.9 1456.49    5216 1457.73  5284.4 1456.86  5323.7 1457.19
  5359.6 1464.23  5380.5  1468.3  5402.2 1469.55  5451.5  1476.8  5529.2 1480.82
  5649.6 1483.03  5692.2 1481.19  5855.1 1479.28  5975.5 1481.73  6187.6 1482.33
#Mann= 7 ,-1 , 0
  4099.1      .1       0  4480.9     .05       0  4580.3      .1       0
  4693.1     .05       0  5117.9    .033       0  5123.9     .05       0
  5284.4      .1       0
Bank Sta=4602.8,5359.6
XS Rating Curve= 0 ,0
Exp/Cntr=0.3,0.1

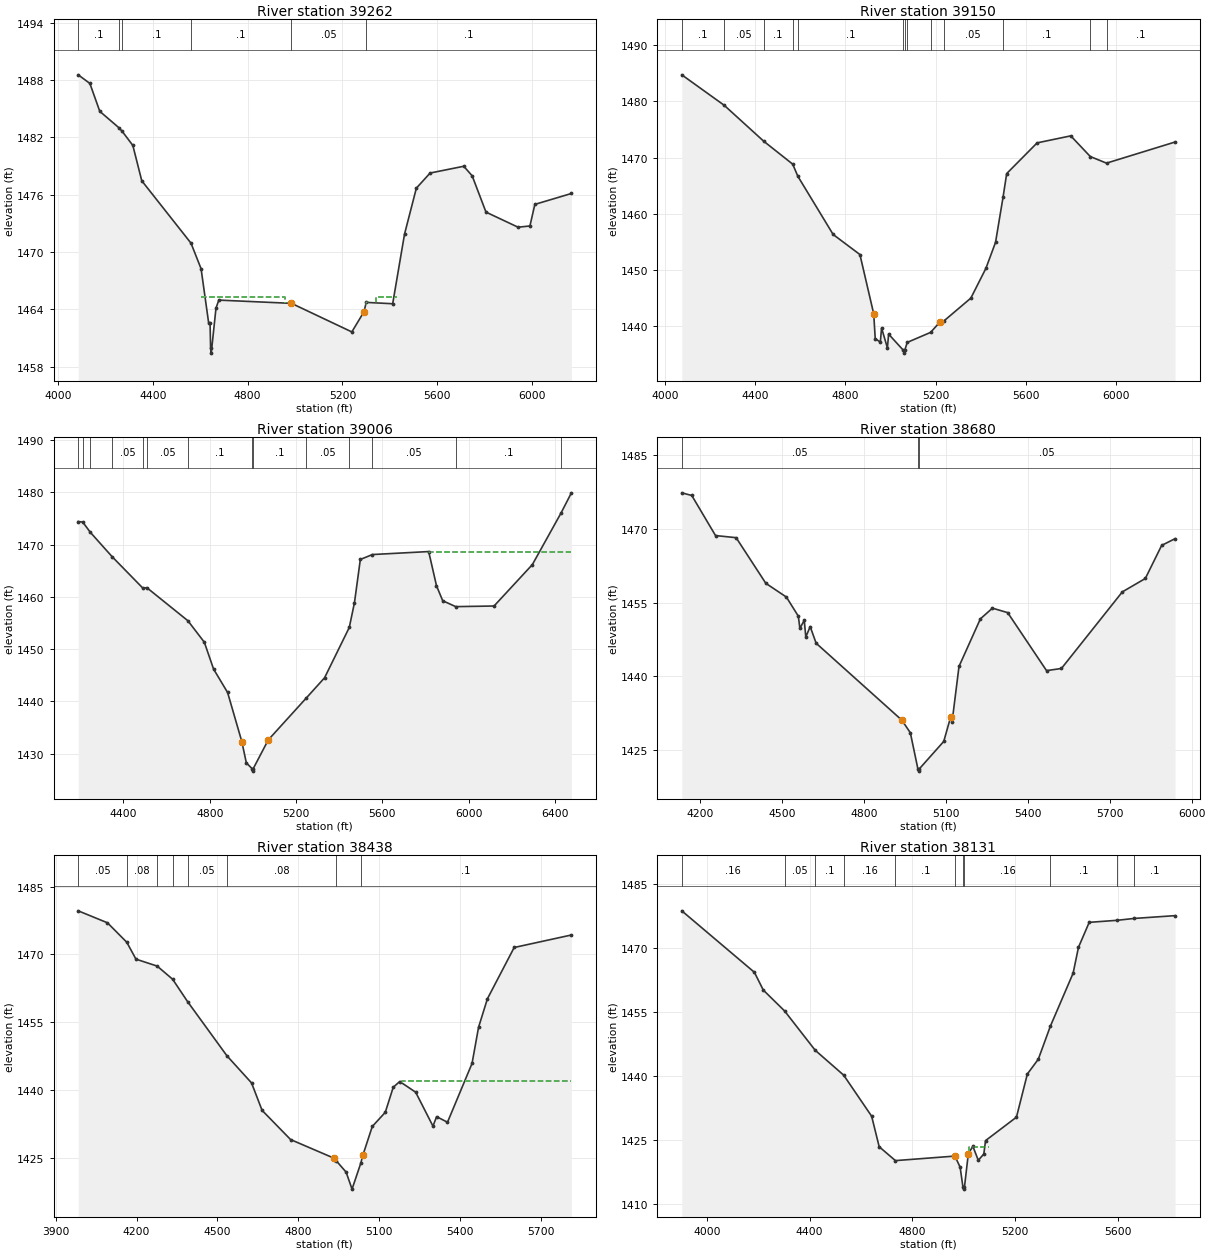
Type RM Length L Ch R = 1 ,39262   ,112,112,112
BEGIN DESCRIPTION:
MCCALL CREEK 78.0
END DESCRIPTION:
XS GIS Cut Line= 3
      2908216.65     10023239.83      2907815.59     10022156.47
        2907259.     10021417.81
#Sta/Elev= 30
  4085.5 1488.56  4134.7 1487.66  4176.5 1484.74  4256.8 1483.03  4271.2 1482.64
  4315.9 1481.17  4353.6 1477.47  4561.2 1470.94  4603.8 1468.26  4635.8 1462.57
  4641.6 1462.59  4643.9 1459.93  4646.6 1459.43  4666.6 1464.14  4678.5 1464.98
    4985 1464.64  5239.5 1461.65    5291 1463.77  5300.2 1464.74  5411.8  1464.6
  5461.8 1471.89  5511.7  1476.7  5569.7 1478.28  5711.6 1478.99    5747 1477.99
  5805.3 1474.19  5940.6 1472.61  5990.6 1472.74  6011.4    1475  6165.6 1476.14
#Mann= 6 ,-1 , 0
  4085.5      .1       0  4256.8     .05       0  4271.2      .1       0
  4561.2      .1       0    4985     .05       0  5300.2      .1       0
#XS Ineff= 3 ,-1
 4605.03 4959.21 1465.28 5297.24 5312.27 1464.83 5341.23 5429.22 1465.28
Permanent Ineff=
       T       T       T
Bank Sta=4985,5291
XS Rating Curve= 0 ,0
Exp/Cntr=0.3,0.1

Type RM Length L Ch R = 1 ,39150   ,144,144,144
BEGIN DESCRIPTION:
MCCALL CREEK 77.0
END DESCRIPTION:
XS GIS Cut Line= 4
      2908407.01     10023198.92      2908018.98     10022396.81
      2907914.81     10022021.81      2907318.49     10021342.16
#Sta/Elev= 30
  4075.2 1484.75  4262.9 1479.33  4437.9 1472.93  4566.4 1468.84  4589.2 1466.68
  4745.6 1456.31  4864.1 1452.74  4925.2 1442.18  4931.9 1437.78  4954.5 1437.13
    4960 1439.65  4985.9 1436.11  4991.1 1438.57  5056.6 1435.68  5059.4 1435.18
  5062.6 1435.68  5073.7 1437.09    5177 1438.87  5218.5 1440.72  5234.3 1440.85
  5355.4 1444.98  5422.1 1450.28  5464.8 1454.92  5498.2    1463  5514.1 1467.16
  5648.9 1472.63  5797.9 1473.88  5884.5 1470.19  5956.2 1469.02  6259.6 1472.78
#Mann= 13 ,-1 , 0
  4075.2      .1       0  4262.9     .05       0  4437.9      .1       0
  4566.4     .05       0  4589.2      .1       0  5056.6     .07       0
  5062.6      .1       0  5073.7     .05       0    5177      .1       0
  5234.3     .05       0  5498.2      .1       0  5884.5     .05       0
  5956.2      .1       0
Bank Sta=4925.2,5218.5
XS Rating Curve= 0 ,0
Exp/Cntr=0.3,0.1

Type RM Length L Ch R = 1 ,39006   ,326,326,326
BEGIN DESCRIPTION:
MCCALL CREEK 76.0
END DESCRIPTION:
XS GIS Cut Line= 4
      2908570.83     10022953.38      2907992.68     10022099.18
      2907690.59     10021588.76      2907524.01     10020948.45
#Sta/Elev= 30
  4190.4 1474.39  4211.3  1474.3  4246.5 1472.34  4347.6 1467.67  4491.1 1461.61
  4508.2 1461.75  4698.9 1455.41    4775  1451.3  4817.9 1446.16  4882.9 1441.68
  4948.8 1432.29  4969.8  1428.2    4996 1427.13  4998.8 1426.63    5002 1427.13
  5071.5 1432.61  5245.9 1440.54  5332.5  1444.5    5447 1454.13    5471 1458.88
  5498.2 1467.14  5554.4 1468.08    5815 1468.65  5851.2 1462.11    5880 1459.24
  5940.2 1458.11    6118 1458.23  6295.5 1466.15  6428.5 1476.03  6476.6 1479.89
#Mann= 14 ,-1 , 0
  4190.4      .1       0  4211.3     .05       0  4246.5      .1       0
  4347.6     .05       0  4491.1      .1       0  4508.2     .05       0
  4698.9      .1       0    4996     .07       0    5002      .1       0
  5245.9     .05       0    5447      .1       0  5554.4     .05       0
  5940.2      .1       0  6428.5     .05       0
#XS Ineff= 2 , 0
                         5816.76         1468.66
Permanent Ineff=
       T       T
Bank Sta=4948.8,5071.5
XS Rating Curve= 0 ,0
Exp/Cntr=0.3,0.1

Type RM Length L Ch R = 1 ,38680   ,180,180,180
BEGIN DESCRIPTION:
MCCALL CREEK 75.0
END DESCRIPTION:
XS GIS Cut Line= 4
      2908732.25     10022838.74      2908424.97     10022286.68
      2908180.18      10021614.8      2908013.71     10021188.23
#Sta/Elev= 30
  4134.3 1477.37  4170.8 1476.83  4257.7 1468.67  4333.1 1468.24  4441.8 1458.95
  4517.2 1456.14  4560.7 1452.26  4566.4 1449.78  4582.4 1451.42  4588.1 1448.02
  4604.1 1450.14  4625.9 1446.75  4939.5 1431.09  4970.6 1428.52  4998.1 1421.21
  5000.9 1420.71  5004.1 1421.21  5092.9 1426.76  5118.1 1431.73  5123.4 1430.76
  5148.7 1442.03  5226.9 1451.71    5271 1453.89  5326.8 1452.98    5469 1441.17
  5523.5 1441.61  5746.3  1457.2  5830.5 1459.93  5890.3 1466.67  5939.1 1468.03
#Mann= 3 ,-1 , 0
  4134.3     .05       0  4998.1     .04       0  5004.1     .05       0
#XS Ineff= 2 , 0
                         5271.59         1453.87
Permanent Ineff=
       T       T
Bank Sta=4939.5,5118.1
XS Rating Curve= 0 ,0
Exp/Cntr=0.3,0.1

Type RM Length L Ch R = 1 ,38438   ,307,307,307
BEGIN DESCRIPTION:
MCCALL CREEK 74.0
END DESCRIPTION:
XS GIS Cut Line= 4
      2908951.92     10022786.62      2908477.98     10021851.76
       2908300.9     10021414.26        2908187.     10021126.92
#Sta/Elev= 30
  3983.6 1479.64  4092.1 1476.99  4163.8 1472.68  4197.8 1468.94  4276.5  1467.4
  4333.8 1464.49  4389.3 1459.53    4535 1447.55  4626.5 1441.53  4665.5 1435.46
  4771.2 1428.99  4932.7 1424.85  4939.8 1424.34  4977.2 1421.78  4999.2 1418.01
  5031.7 1423.76  5039.4 1425.52  5074.3 1431.89  5122.5 1435.02    5152 1440.57
  5176.1 1441.84  5235.2 1439.47  5299.3 1431.96  5312.9 1434.06  5353.2 1432.82
  5444.3 1445.85  5468.4 1453.85  5501.3 1460.17  5600.5 1471.52  5812.8 1474.29
#Mann= 8 ,-1 , 0
  3983.6     .05       0  4163.8     .08       0  4276.5     .05       0
  4333.8     .08       0  4389.3     .05       0    4535     .08       0
  4939.8     .05       0  5031.7      .1       0
#XS Ineff= 2 , 0
                         5184.51         1441.98
Permanent Ineff=
       T       T
Bank Sta=4932.7,5039.4
XS Rating Curve= 0 ,0
Exp/Cntr=0.3,0.1

Type RM Length L Ch R = 1 ,38131   ,465,465,465
BEGIN DESCRIPTION:
Mapping XS de68b203
END DESCRIPTION:
XS GIS Cut Line= 4
      2909216.64      10022609.6       2908820.8     10021765.84
      2908419.76     10021401.26      2908289.55     10020974.15
#Sta/Elev= 30
  3902.7 1478.61  4185.3 1464.21  4220.1 1460.04  4302.8 1455.16  4422.1 1445.94
    4533 1440.11  4641.9 1430.49  4671.3 1423.33  4734.5 1420.08  4965.2 1421.14
  4967.1 1421.02  4986.5 1418.54  4997.4  1413.9  5000.1  1413.4  5003.4  1413.9
 5018.47 1421.74  5036.2 1423.43  5057.1 1420.16  5078.7 1421.62  5085.5 1424.77
  5205.8 1430.26  5248.3 1440.38  5290.9 1443.84  5337.8 1451.57  5426.4 1463.99
  5447.3 1470.06  5489.1 1475.91    5598 1476.39  5662.9 1476.82  5823.2 1477.48
#Mann= 11 ,-1 , 0
  3902.7     .16       0  4302.8     .05       0  4422.1      .1       0
    4533     .16       0  4734.5      .1       0  4967.1     .16       0
  4997.4     .07       0  5003.4     .16       0  5337.8      .1       0
    5598     .05       0  5662.9      .1       0
#XS Ineff= 2 ,-1
 4662.42 4962.67 1420.88  5022.2 5097.39 1423.37
Permanent Ineff=
       T       T
Bank Sta=4965.2,5018.47
XS Rating Curve= 0 ,0
Exp/Cntr=0.3,0.1

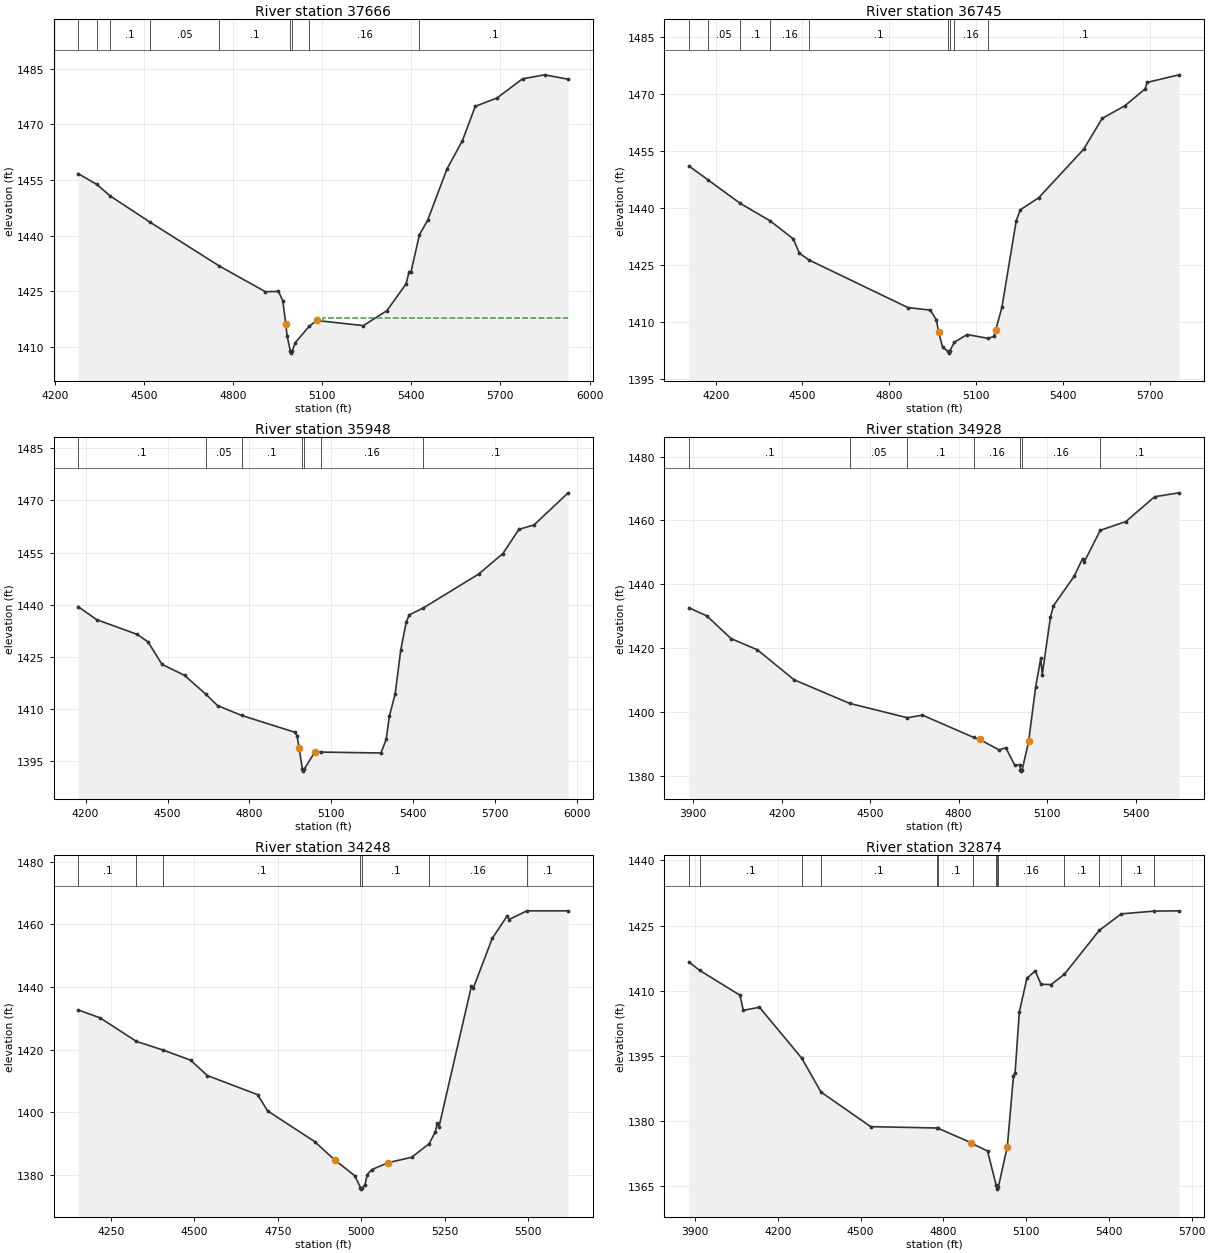
Type RM Length L Ch R = 1 ,37666   ,921,921,921
BEGIN DESCRIPTION:
MCCALL CREEK 73.0
END DESCRIPTION:
XS GIS Cut Line= 3
      2909654.15     10022031.48       2908758.3      10021364.8
      2908483.57     10020908.64
#Sta/Elev= 30
  4278.8 1456.73  4342.2 1453.79  4386.9 1450.69    4521 1443.62  4753.4 1431.84
  4909.3 1424.86  4953.1 1424.97  4967.7 1422.46  4977.7 1416.29  4982.3 1412.91
  4993.4 1408.81  4996.2 1408.31  4999.4 1408.81  5009.4  1411.1  5057.2 1415.61
  5082.4 1417.11  5238.8 1415.73  5318.1 1419.76  5382.7    1427  5392.3 1430.17
    5399 1430.17  5427.6 1440.25  5455.1 1444.11  5520.2 1457.97  5571.8 1465.53
  5615.4 1474.85  5688.6 1477.11  5774.6 1482.28  5848.4 1483.35    5928 1482.17
#Mann= 9 ,-1 , 0
  4278.8     .05       0  4342.2     .16       0  4386.9      .1       0
    4521     .05       0  4753.4      .1       0  4993.4     .07       0
  4999.4      .1       0  5057.2     .16       0  5427.6      .1       0
#XS Ineff= 2 , 0
                         5102.05         1417.65
Permanent Ineff=
       T       T
Bank Sta=4977.7,5082.4
XS Rating Curve= 0 ,0
Exp/Cntr=0.3,0.1

Type RM Length L Ch R = 1 ,36745   ,797,797,797
BEGIN DESCRIPTION:
MCCALL CREEK 72.0
END DESCRIPTION:
XS GIS Cut Line= 2
      2910018.69     10021713.73        2908826.     10020510.62
#Sta/Elev= 30
  4107.6 1451.08  4172.6 1447.47  4285.6  1441.2  4388.3 1436.63  4468.4 1431.89
  4489.6  1428.1  4522.6 1426.33  4864.4 1413.81  4942.1 1413.12  4963.4 1410.52
  4970.4 1407.44  4984.6 1403.34  5002.8 1402.31  5005.6 1401.81  5008.8 1402.31
  5025.4 1404.69  5069.4 1406.71  5141.2 1405.69  5161.4 1406.19  5168.4 1407.93
  5189.7 1413.94  5239.1 1436.67  5253.3 1439.54  5316.9 1442.72  5472.5 1455.52
  5536.1 1463.59  5613.9 1466.89  5684.6 1471.36  5691.7 1473.07  5801.7 1475.06
#Mann= 9 ,-1 , 0
  4107.6      .1       0  4172.6     .05       0  4285.6      .1       0
  4388.3     .16       0  4522.6      .1       0  5002.8     .07       0
  5008.8      .1       0  5025.4     .16       0  5141.2      .1       0
Bank Sta=4970.4,5168.4
XS Rating Curve= 0 ,0
Exp/Cntr=0.3,0.1

Type RM Length L Ch R = 1 ,35948   ,1020,1020,1020
BEGIN DESCRIPTION:
MCCALL CREEK 70.0
END DESCRIPTION:
XS GIS Cut Line= 4
      2910227.04     10021244.98      2909956.22     10020682.51
      2909643.72     10020474.18      2908878.09     10020260.63
#Sta/Elev= 30
  4172.3 1439.45  4240.3 1435.68  4389.1 1431.43  4428.8 1429.25  4479.6 1422.81
  4562.1 1419.64  4640.6 1414.18  4683.2 1410.91  4771.6 1408.08  4966.9 1403.23
  4974.2 1402.26  4981.9 1398.66  4993.9 1392.55  4996.7 1392.05  4999.9 1392.55
    5039 1397.53  5060.4 1397.54  5281.4 1397.27  5300.5 1401.16  5312.6 1407.99
  5333.3 1414.24  5354.1 1426.99  5374.1    1435  5385.2 1437.07  5436.4 1439.03
  5639.3 1448.81  5727.8  1454.7  5786.5 1461.67    5842 1462.96    5967  1472.2
#Mann= 7 ,-1 , 0
  4172.3      .1       0  4640.6     .05       0  4771.6      .1       0
  4993.9     .07       0  4999.9      .1       0  5060.4     .16       0
  5436.4      .1       0
Bank Sta=4981.9,5039
XS Rating Curve= 0 ,0
Exp/Cntr=0.3,0.1

Type RM Length L Ch R = 1 ,34928   ,680,680,680
BEGIN DESCRIPTION:
MCCALL CREEK 68.0
END DESCRIPTION:
XS GIS Cut Line= 3
      2910310.39     10021052.32      2910122.89      10020302.3
      2909997.89     10019422.13
#Sta/Elev= 30
  3885.3 1432.62  3945.7 1430.11  4028.1 1422.98  4117.9 1419.44  4241.6 1410.09
  4430.4 1402.67  4626.5 1398.17  4677.2 1398.99  4851.1    1392  4870.9  1391.4
  4936.7  1388.1    4960 1388.78  4990.3 1383.29  5007.7 1383.48  5009.7 1381.94
  5012.5 1381.44  5015.7 1381.94  5037.5 1390.76    5061 1407.73  5078.6 1416.81
  5083.6 1411.69  5111.5 1429.76  5121.6 1433.26  5192.3 1442.57  5220.4 1448.07
  5225.4  1446.9  5280.5 1456.91  5367.3 1459.66    5465 1467.44  5547.4 1468.65
#Mann= 7 ,-1 , 0
  3885.3      .1       0  4430.4     .05       0  4626.5      .1       0
  4851.1     .16       0  5009.7     .07       0  5015.7     .16       0
  5280.5      .1       0
Bank Sta=4870.9,5037.5
XS Rating Curve= 0 ,0
Exp/Cntr=0.3,0.1

Type RM Length L Ch R = 1 ,34248   ,1374,1374,1374
BEGIN DESCRIPTION:
MCCALL CREEK 66.0
END DESCRIPTION:
XS GIS Cut Line= 2
      2910560.39     10021099.14      2910700.86     10019637.18
#Sta/Elev= 30
  4151.5 1432.66  4217.2 1430.14  4326.6  1422.6    4407 1419.82  4488.5 1416.64
  4538.7 1411.72  4689.4 1405.62  4719.5 1400.43  4860.2 1390.65  4920.5 1384.78
  4980.7 1379.73  4997.8 1375.95  5000.6 1375.45  5003.8 1375.95  5010.9 1376.72
    5018  1380.1  5030.9 1381.64  5081.2 1383.92  5151.5 1385.62  5203.7 1389.96
  5221.8 1393.68    5228 1396.52    5233  1395.3  5330.5 1440.39  5335.6 1439.52
  5392.6 1455.49  5438.1 1462.77  5443.1 1461.53  5496.4  1464.3  5620.2  1464.3
#Mann= 7 ,-1 , 0
  4151.5      .1       0  4326.6     .05       0    4407      .1       0
  4997.8     .07       0  5003.8      .1       0  5203.7     .16       0
  5496.4      .1       0
Bank Sta=4920.5,5081.2
XS Rating Curve= 0 ,0
Exp/Cntr=0.3,0.1

Type RM Length L Ch R = 1 ,32874   ,665,665,665
BEGIN DESCRIPTION:
MCCALL CREEK 65.0
END DESCRIPTION:
XS GIS Cut Line= 3
      2911169.76     10021057.48      2911284.34     10020125.22
       2911731.7     10019417.77
#Sta/Elev= 30
    3878 1416.61  3916.8 1414.67  4063.1 1408.94  4075.3 1405.46  4133.7 1406.17
  4287.2 1394.42  4356.6 1386.65  4536.7 1378.67  4778.1 1378.36  4781.6 1378.28
  4901.9 1374.94  4908.8 1374.63  4960.2 1373.08  4991.4 1365.24  4993.5 1364.78
  4996.3 1364.28  4999.5 1364.78    5032 1374.05  5054.3 1390.33  5060.2  1391.1
  5075.5 1405.08    5103 1412.85  5133.1 1414.55  5154.3 1411.46  5190.8 1411.39
  5238.8 1413.77  5365.3 1423.88  5444.8 1427.68  5563.2 1428.31  5654.3 1428.38
#Mann= 14 ,-1 , 0
    3878     .05       0  3916.8      .1       0  4287.2     .16       0
  4356.6      .1       0  4778.1     .05       0  4781.6      .1       0
  4908.8     .05       0  4991.4     .16       0  4993.5     .07       0
  4999.5     .16       0  5238.8      .1       0  5365.3     .16       0
  5444.8      .1       0  5563.2     .16       0
Bank Sta=4901.9,5032
XS Rating Curve= 0 ,0
Exp/Cntr=0.3,0.1

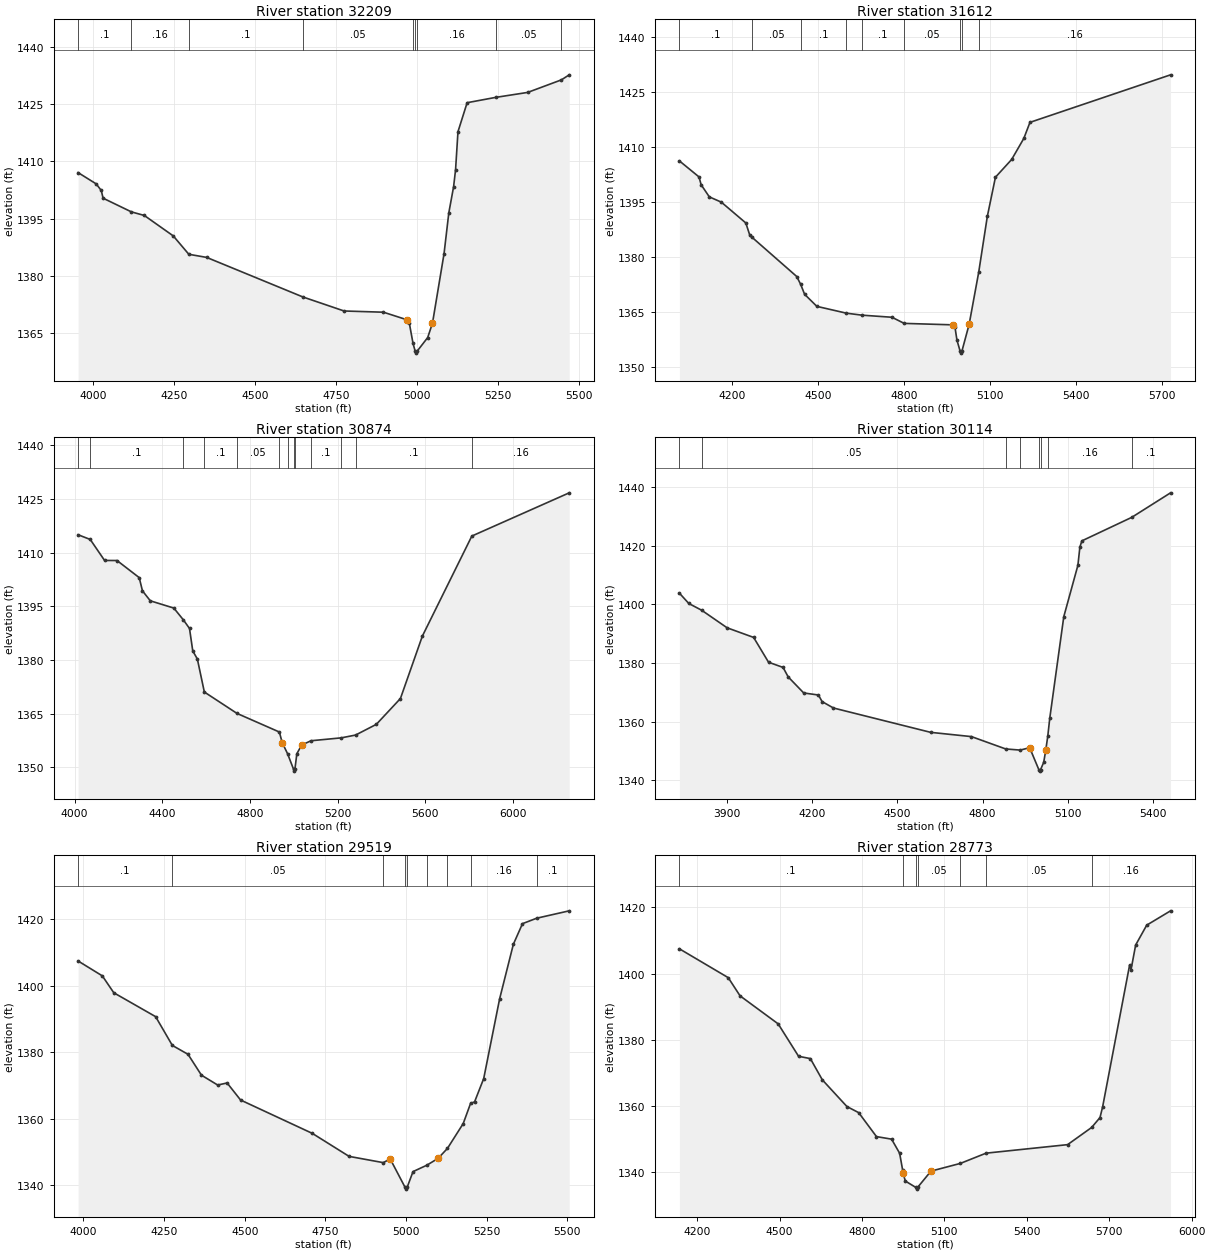
Type RM Length L Ch R = 1 ,32209   ,597,597,597
BEGIN DESCRIPTION:
MCCALL CREEK 64.0
END DESCRIPTION:
XS GIS Cut Line= 3
      2911487.47     10021135.64      2911721.84     10020536.68
      2912227.07     10019823.11
#Sta/Elev= 30
  3953.8 1407.04  4009.5  1404.1  4025.4 1402.37    4031 1400.35  4118.5 1396.77
  4158.4 1395.83  4247.9 1390.48  4295.9 1385.68  4351.1 1384.86  4648.6 1374.51
  4775.6 1370.85  4897.4 1370.53  4968.8 1368.58  4977.4 1367.58  4988.6 1362.39
  4995.3 1360.33  4998.1 1359.83  5001.3 1360.33    5034 1363.91  5048.8 1367.68
  5084.5 1385.85  5099.2 1396.51    5114 1403.35  5120.1 1407.81  5127.5 1417.73
  5155.8 1425.32    5244 1426.71  5342.9 1428.01    5447 1431.29  5471.3 1432.61
#Mann= 9 ,-1 , 0
  3953.8      .1       0  4118.5     .16       0  4295.9      .1       0
  4648.6     .05       0  4988.6     .16       0  4995.3     .07       0
  5001.3     .16       0    5244     .05       0    5447      .1       0
Bank Sta=4968.8,5048.8
XS Rating Curve= 0 ,0
Exp/Cntr=0.3,0.1

Type RM Length L Ch R = 1 ,31612   ,738,738,738
BEGIN DESCRIPTION:
MCCALL CREEK 63.0
END DESCRIPTION:
XS GIS Cut Line= 4
      2911732.29     10021354.36      2912227.05     10020781.47
      2912602.05     10020390.84      2912659.35     10019979.37
#Sta/Elev= 30
  4017.2  1406.2  4085.5 1401.84  4093.1 1399.69  4121.6 1396.39  4163.4 1394.96
  4248.9 1389.28  4263.1 1385.88  4271.2 1385.33  4426.6 1374.68  4440.2 1372.56
  4454.1 1369.83  4496.8 1366.54  4599.5 1364.69  4654.2 1364.14    4759 1363.57
  4801.5  1361.9  4971.6  1361.5  4978.8 1360.86  4985.7 1357.33  4996.9 1354.29
  4999.6 1353.79  5002.9 1354.29  5028.2 1361.63  5061.6 1375.84  5091.7 1391.07
    5120 1401.75  5176.6 1406.59  5219.1 1412.34  5240.5 1416.71  5731.1 1429.67
#Mann= 9 ,-1 , 0
  4017.2      .1       0  4271.2     .05       0  4440.2      .1       0
  4599.5     .05       0  4654.2      .1       0  4801.5     .05       0
  4996.9    .035       0  5002.9     .05       0  5061.6     .16       0
Bank Sta=4971.6,5028.2
XS Rating Curve= 0 ,0
Exp/Cntr=0.3,0.1

Type RM Length L Ch R = 1 ,30874   ,760,760,760
BEGIN DESCRIPTION:
MCCALL CREEK 61.0
END DESCRIPTION:
XS GIS Cut Line= 4
      2911914.54     10021817.93      2912549.97     10021375.22
      2912789.55     10020875.22      2912773.93     10019963.74
#Sta/Elev= 30
  4016.1 1415.03  4071.4 1413.72  4136.9 1407.85  4193.6 1407.83  4294.9 1403.05
  4309.7 1399.36  4345.5 1396.57  4452.8 1394.54  4496.6 1391.22  4524.3 1388.84
  4539.2 1382.56  4560.1 1380.31    4592 1371.08    4741  1365.1  4934.2  1359.9
  4947.4 1356.91  4971.7 1353.83  4999.1 1349.47  5001.9 1348.97  5005.1 1349.47
    5014 1353.84  5036.1 1356.26  5078.6 1357.46  5216.8 1358.27  5281.8 1359.05
  5376.5 1362.04  5486.5 1369.26  5586.5  1386.7  5812.3 1414.67  6256.6 1426.75
#Mann= 13 ,-1 , 0
  4016.1     .16       0  4071.4      .1       0  4496.6     .05       0
    4592      .1       0    4741     .05       0  4934.2      .1       0
  4971.7     .05       0  4999.1    .035       0  5005.1     .05       0
  5078.6      .1       0  5216.8     .05       0  5281.8      .1       0
  5812.3     .16       0
Bank Sta=4947.4,5036.1
XS Rating Curve= 0 ,0
Exp/Cntr=0.3,0.1

Type RM Length L Ch R = 1 ,30114   ,595,595,595
BEGIN DESCRIPTION:
MCCALL CREEK 59.0
END DESCRIPTION:
XS GIS Cut Line= 3
      2912982.26     10022385.64      2913284.34     10021276.26
       2913690.6      10020864.8
#Sta/Elev= 30
    3733 1403.81  3766.1 1400.29  3811.5 1397.98  3900.8 1392.01  3994.1 1388.73
  4046.6 1380.28  4097.7 1378.51  4115.7 1375.28  4170.3 1369.81  4222.1 1369.11
    4235 1366.87  4274.8 1364.69  4617.1 1356.39  4760.5 1354.94  4881.1 1350.73
    4932 1350.35  4965.3 1351.16  4997.6 1343.68  5000.3 1343.18  5003.6 1343.68
  5014.7 1346.17  5021.8 1350.23    5029 1355.07    5036 1361.19  5085.4 1395.82
    5135 1413.29    5142 1419.53  5149.1 1421.63  5324.2 1429.62    5461 1437.99
#Mann= 8 ,-1 , 0
    3733      .1       0  3811.5     .05       0  4881.1      .1       0
    4932     .05       0  4997.6    .035       0  5003.6     .05       0
    5029     .16       0  5324.2      .1       0
Bank Sta=4965.3,5021.8
XS Rating Curve= 0 ,0
Exp/Cntr=0.3,0.1

Type RM Length L Ch R = 1 ,29519   ,746,746,746
BEGIN DESCRIPTION:
MCCALL CREEK 58.0
END DESCRIPTION:
XS GIS Cut Line= 3
      2913039.53     10022489.83      2913492.68     10021870.01
      2914033.93     10021344.37
#Sta/Elev= 30
  3983.5 1407.49  4058.6 1403.01  4094.1 1397.93  4223.8 1390.74  4275.6 1382.09
  4324.2 1379.41  4365.9 1373.13  4416.1 1370.17  4445.4 1370.79  4487.1 1365.66
  4709.5 1355.62  4823.5  1348.7  4929.4 1346.82  4950.8 1347.94  4997.2 1339.35
    5000 1338.85  5003.2 1339.35  5021.6 1344.12  5064.7 1346.06  5099.3  1348.1
  5128.2 1351.09  5177.2 1358.58  5199.9 1364.62  5212.4 1365.11  5240.7 1372.12
  5290.1 1396.13  5332.6 1412.52  5360.9 1418.72    5405 1420.36  5505.8 1422.58
#Mann= 9 ,-1 , 0
  3983.5      .1       0  4275.6     .05       0  4929.4      .1       0
  4997.2     .07       0  5003.2      .1       0  5064.7     .16       0
  5128.2      .1       0  5199.9     .16       0    5405      .1       0
Bank Sta=4950.8,5099.3
XS Rating Curve= 0 ,0
Exp/Cntr=0.3,0.1

Type RM Length L Ch R = 1 ,28773   ,604,604,604
BEGIN DESCRIPTION:
MCCALL CREEK 56.0
END DESCRIPTION:
XS GIS Cut Line= 4
      2913643.71     10023052.32      2914013.51     10022422.09
      2914164.55      10021864.8      2914206.08     10021387.22
#Sta/Elev= 30
  4135.7 1407.47  4313.4 1398.76  4356.4 1393.27  4495.1 1384.81  4569.4 1375.02
  4612.3 1374.32  4655.8 1367.91  4745.3 1359.85  4788.2    1358  4852.9 1350.77
  4907.9    1350  4937.2 1345.74  4947.9 1340.77 4948.86  1339.9    4958 1337.35
  4996.4 1335.41  4999.2 1334.91  5002.4 1335.41  5051.2 1340.34  5158.4 1342.68
  5251.8 1345.77  5548.5 1348.34    5636 1353.53  5666.4 1356.52  5675.8 1359.68
  5774.3 1402.61  5779.4 1401.18  5796.2 1408.62  5836.4 1414.61  5923.2 1418.94
#Mann= 7 ,-1 , 0
  4135.7      .1       0  4947.9     .05       0  4996.4    .035       0
  5002.4     .05       0  5158.4      .1       0  5251.8     .05       0
    5636     .16       0
Bank Sta=4948.86,5051.2
XS Rating Curve= 0 ,0
Exp/Cntr=0.3,0.1