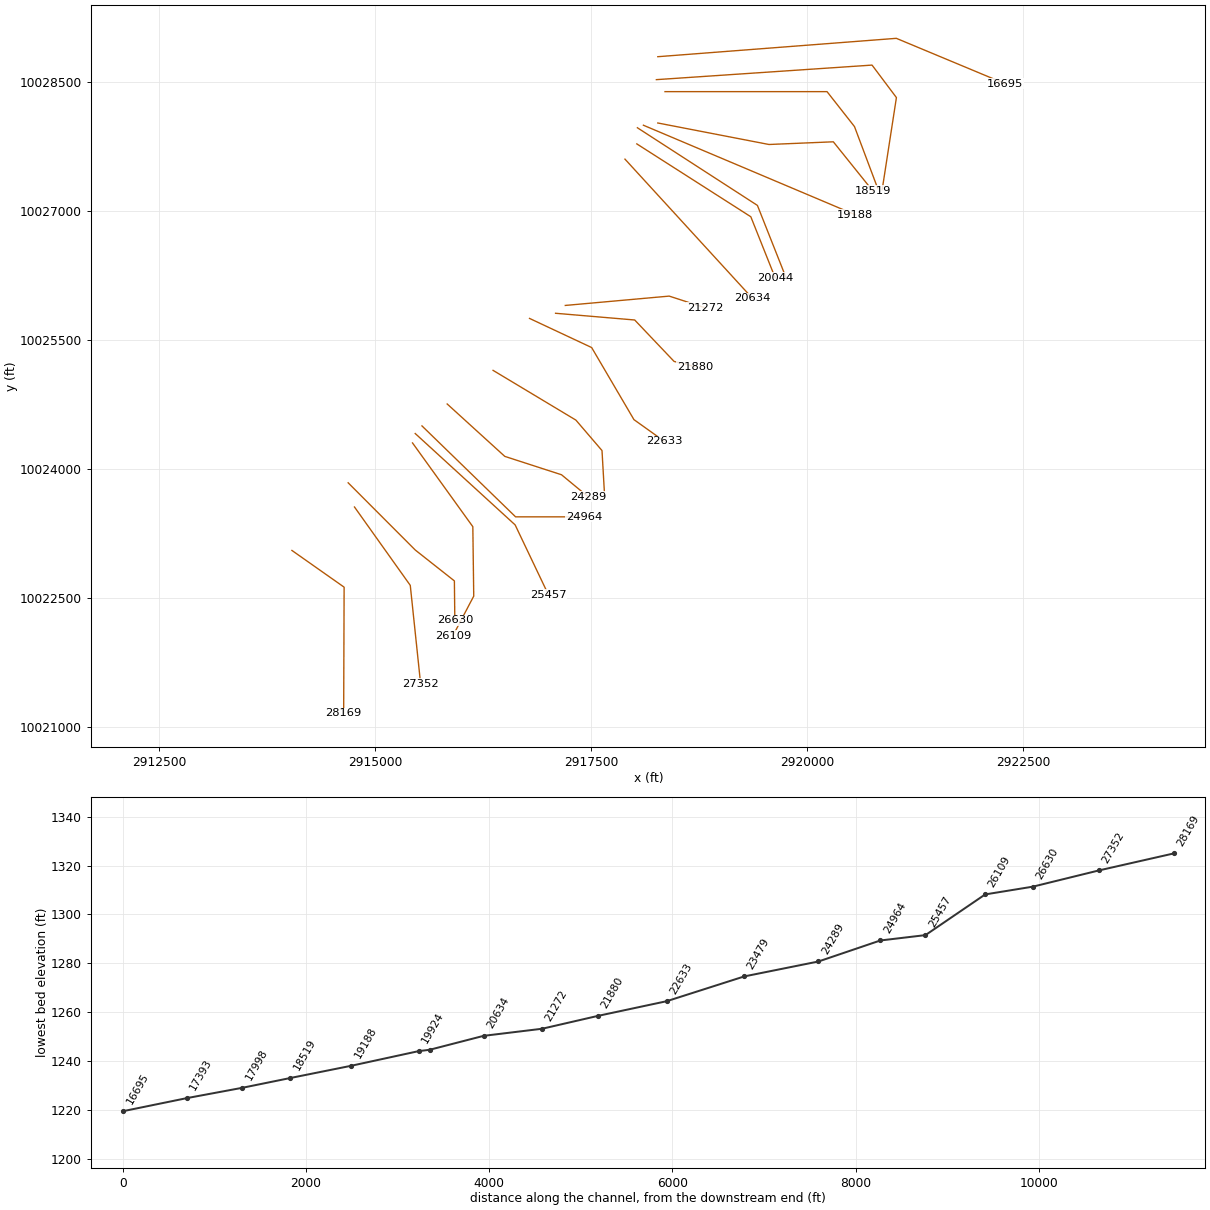
HEC-RAS study MCCALL CREEK.prj: MCCALL CREEK Base Level Engineering

--- MCCALL CREEK.g01 (geometry) --- (continued)

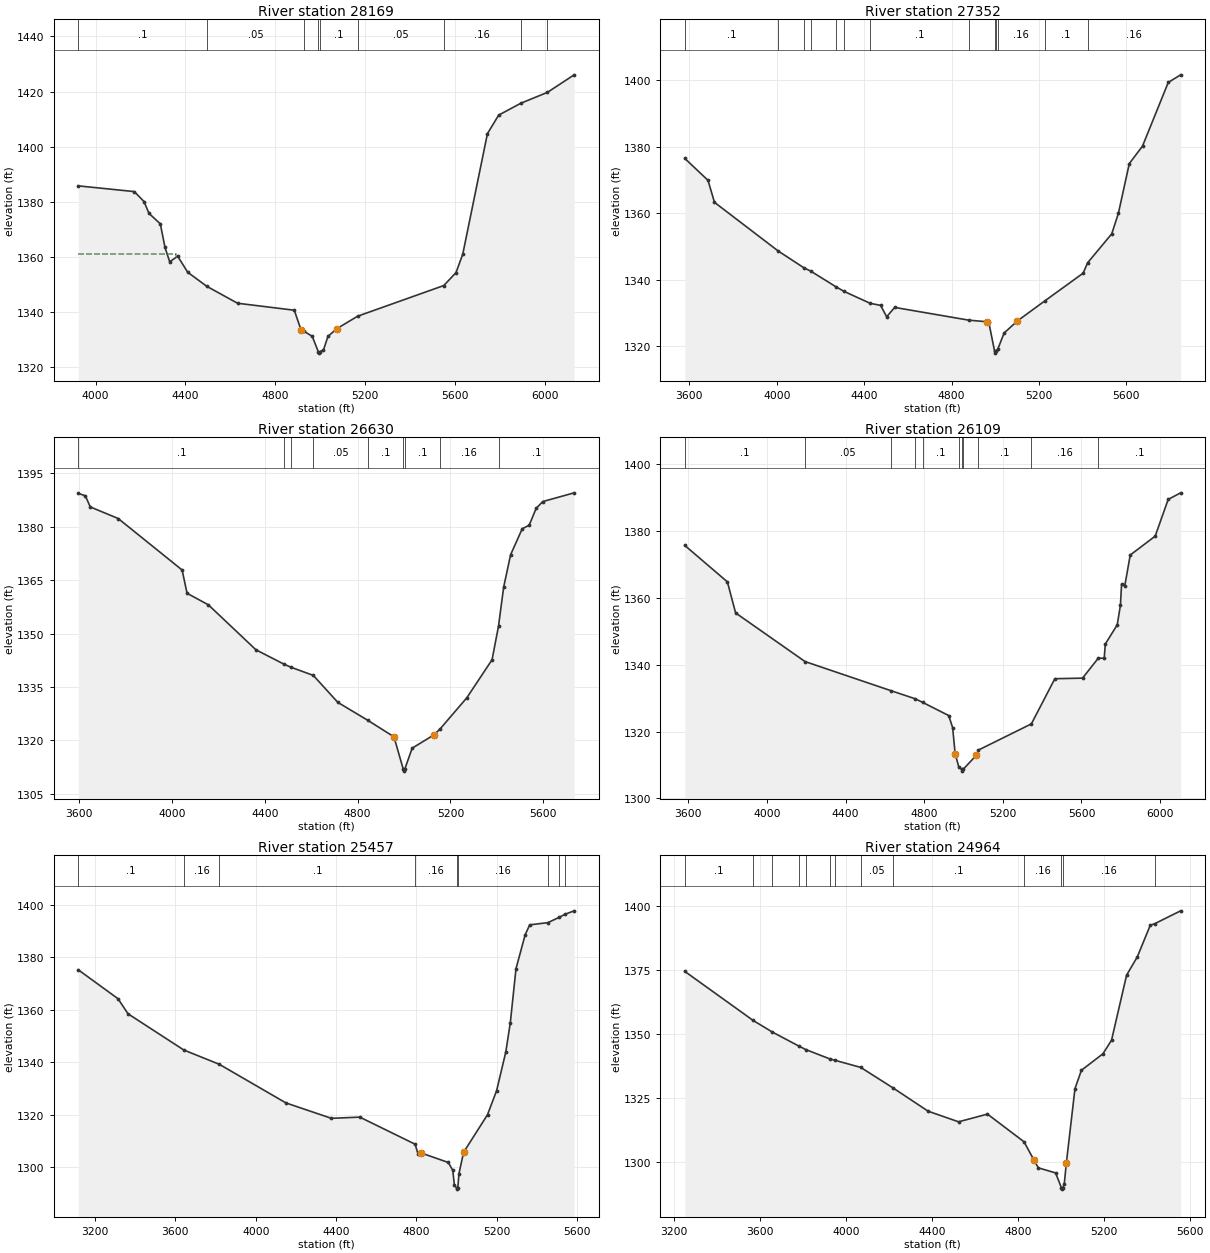
Type RM Length L Ch R = 1 ,28169   ,817,817,817
BEGIN DESCRIPTION:
MCCALL CREEK 54.0
END DESCRIPTION:
XS GIS Cut Line= 3
      2914039.55     10023052.31      2914643.72     10022625.22
      2914638.52     10021157.61
#Sta/Elev= 30
  3923.4 1385.72  4172.6 1383.64    4216 1380.01  4237.9 1375.73  4288.4 1371.93
  4309.3 1363.36  4330.2 1358.14  4365.9 1360.16  4410.2 1354.35  4495.5 1349.22
  4632.4 1343.08  4884.8 1340.55  4914.8 1333.42  4927.9  1332.9  4964.8 1331.07
  4991.8 1325.46  4994.5 1324.96  4997.8 1325.46  5014.8 1326.11  5034.8 1331.04
  5074.8 1333.87  5167.1 1338.38  5550.4 1349.51  5604.8  1354.2  5634.8 1360.86
  5744.8 1404.69  5794.8 1411.42  5892.7 1415.71  6011.5 1419.67  6130.9 1426.06
#Mann= 9 ,-1 , 0
  3923.4      .1       0  4495.5     .05       0  4927.9      .1       0
  4991.8     .07       0  4997.8      .1       0  5167.1     .05       0
  5550.4     .16       0  5892.7     .05       0  6011.5      .1       0
#XS Ineff= 2 , 0
         4357.39 1360.85
Permanent Ineff=
       T       T
Bank Sta=4914.8,5074.8
XS Rating Curve= 0 ,0
Exp/Cntr=0.3,0.1

Type RM Length L Ch R = 1 ,27352   ,722,722,722
BEGIN DESCRIPTION:
MCCALL CREEK 53.0
END DESCRIPTION:
XS GIS Cut Line= 3
      2914763.54     10023557.47      2915409.34     10022646.05
      2915529.14     10021500.23
#Sta/Elev= 30
  3579.2 1376.45  3685.4 1369.87    3715 1363.27  4007.9  1348.6  4126.5 1343.53
    4155 1342.65    4272 1337.88  4308.1 1336.54  4427.2 1332.97  4475.4 1332.34
    4503 1328.92  4539.7 1331.73  4879.3  1327.9    4960 1327.44    4970  1327.4
  4997.2 1318.51  4999.9 1318.01  5003.2 1318.51  5012.5 1319.36  5040.4 1324.03
  5100.7 1327.64  5225.6 1333.63  5402.4 1342.02  5422.5 1345.11  5533.1 1353.82
  5563.3 1359.93  5613.5 1374.91  5673.9 1380.15  5791.6 1399.25  5848.3 1401.54
#Mann= 13 ,-1 , 0
  3579.2      .1       0  4007.9     .05       0  4126.5      .1       0
    4155     .05       0    4272      .1       0  4308.1     .05       0
  4427.2      .1       0  4879.3     .05       0  4997.2    .035       0
  5003.2     .05       0  5012.5     .16       0  5225.6      .1       0
  5422.5     .16       0
#XS Ineff= 2 , 0
         4539.77 1331.69
Permanent Ineff=
       T       T
Bank Sta=4960,5100.7
XS Rating Curve= 0 ,0
Exp/Cntr=0.3,0.1

Type RM Length L Ch R = 1 ,26630   ,521,521,521
BEGIN DESCRIPTION:
MCCALL CREEK 52.0
END DESCRIPTION:
XS GIS Cut Line= 4
      2914690.59     10023838.76      2915466.64     10023057.51
      2915919.76     10022698.13      2915924.97     10022239.79
#Sta/Elev= 30
  3595.7 1389.37    3626 1388.66  3647.2 1385.55  3767.5  1382.3  4043.2 1367.84
  4064.5  1361.3  4156.4 1358.06  4361.5 1345.43  4484.2 1341.34  4513.9  1340.5
  4608.9 1338.24  4714.7 1330.66  4843.5 1325.64  4956.6    1321  4996.9 1311.86
  4999.7 1311.36  5002.9 1311.86  5035.2 1317.81  5128.1  1321.5  5155.3 1323.19
  5270.7 1331.95  5379.6 1342.64  5407.5  1352.1  5429.6 1363.02  5459.6 1372.12
  5509.6 1379.41  5539.6 1380.41  5569.6 1385.13  5597.9 1387.05  5733.6 1389.51
#Mann= 9 ,-1 , 0
  3595.7      .1       0  4484.2     .05       0  4513.9      .1       0
  4608.9     .05       0  4843.5      .1       0  4996.9     .07       0
  5002.9      .1       0  5155.3     .16       0  5407.5      .1       0
Bank Sta=4956.6,5128.1
XS Rating Curve= 0 ,0
Exp/Cntr=0.3,0.1

Type RM Length L Ch R = 1 ,26109   ,652,652,652
BEGIN DESCRIPTION:
MCCALL CREEK 50.0
END DESCRIPTION:
XS GIS Cut Line= 4
      2915435.38     10024302.31       2916133.3     10023328.34
      2916143.72     10022521.05      2915904.11     10022062.67
#Sta/Elev= 30
  3581.8 1375.63  3798.5 1364.74  3840.3 1355.46  4193.7 1340.92  4632.3 1332.19
  4755.2 1329.78  4792.8  1328.7  4924.6 1324.79  4944.6 1321.18 4957.39 1313.39
  4976.5 1309.29  4991.6 1308.68  4994.4 1308.18  4997.6 1308.68  5064.7 1312.89
  5074.8 1314.45  5345.2  1322.3  5464.7  1335.8  5605.4 1335.97  5686.3 1341.98
  5715.8 1341.88  5721.4 1346.17    5782 1351.89  5798.4 1357.78  5804.1 1364.07
  5820.5 1363.56  5848.2 1372.76  5975.1  1378.4  6041.3 1389.38  6104.6 1391.35
#Mann= 11 ,-1 , 0
  3581.8      .1       0  4193.7     .05       0  4632.3      .1       0
  4755.2     .05       0  4792.8      .1       0  4976.5     .05       0
  4991.6    .035       0  4997.6     .05       0  5074.8      .1       0
  5345.2     .16       0  5686.3      .1       0
Bank Sta=4957.39,5064.7
XS Rating Curve= 0 ,0
Exp/Cntr=0.3,0.1

Type RM Length L Ch R = 1 ,25457   ,493,493,493
BEGIN DESCRIPTION:
MCCALL CREEK 49.0
END DESCRIPTION:
XS GIS Cut Line= 3
      2915466.63     10024411.68      2916622.89     10023349.18
       2917007.8     10022537.74
#Sta/Elev= 30
  3116.8 1375.18  3314.7 1364.15  3364.1 1358.42    3642  1344.6  3818.9 1339.14
  4150.2 1324.42  4376.5 1318.54  4518.1    1319  4793.6 1308.66  4807.2  1305.1
  4824.4  1305.3  4958.8 1301.69  4980.9 1298.68  4989.1 1292.93    5000 1292.03
  5002.8 1291.53    5006 1292.03  5011.8 1297.45  5034.6 1305.55  5153.8 1319.92
  5199.2 1329.11  5244.7 1343.78  5267.4 1355.04  5295.7 1375.64  5341.2 1388.54
  5363.9 1392.35  5454.5 1393.19  5510.8 1395.23  5540.7 1396.41  5585.2  1397.7
#Mann= 9 ,-1 , 0
  3116.8      .1       0    3642     .16       0  3818.9      .1       0
  4793.6     .16       0    5000     .07       0    5006     .16       0
  5454.5      .1       0  5510.8     .16       0  5540.7      .1       0
Bank Sta=4824.4,5034.6
XS Rating Curve= 0 ,0
Exp/Cntr=0.3,0.1

Type RM Length L Ch R = 1 ,24964   ,675,675,675
BEGIN DESCRIPTION:
MCCALL CREEK 48.0
END DESCRIPTION:
XS GIS Cut Line= 3
      2915544.73     10024500.25      2916628.09     10023442.93
      2917419.79     10023442.93
#Sta/Elev= 30
  3250.9 1374.36  3568.7  1355.2  3657.6 1350.69  3781.3 1345.19    3813 1343.85
  3925.2 1340.18    3948 1339.67    4069 1336.86  4217.9 1328.92  4382.6 1319.75
    4524 1315.62  4658.3 1318.63  4828.2 1307.82  4875.1 1300.57  4895.1 1297.63
  4975.1 1295.66  5002.1 1289.83  5004.8 1289.33  5008.1 1289.83  5015.1 1291.16
  5025.1 1299.56  5065.1 1328.56  5095.1 1335.75  5195.1 1342.18  5235.1 1347.46
  5305.1 1372.88  5355.1 1380.04  5415.1 1392.35    5437 1393.03  5556.4 1398.01
#Mann= 13 ,-1 , 0
  3250.9      .1       0  3568.7     .16       0  3657.6      .1       0
  3781.3     .16       0    3813      .1       0  3925.2     .16       0
    3948      .1       0    4069     .05       0  4217.9      .1       0
  4828.2     .16       0  5002.1     .07       0  5008.1     .16       0
    5437      .1       0
Bank Sta=4875.1,5025.1
XS Rating Curve= 0 ,0
Exp/Cntr=0.3,0.1

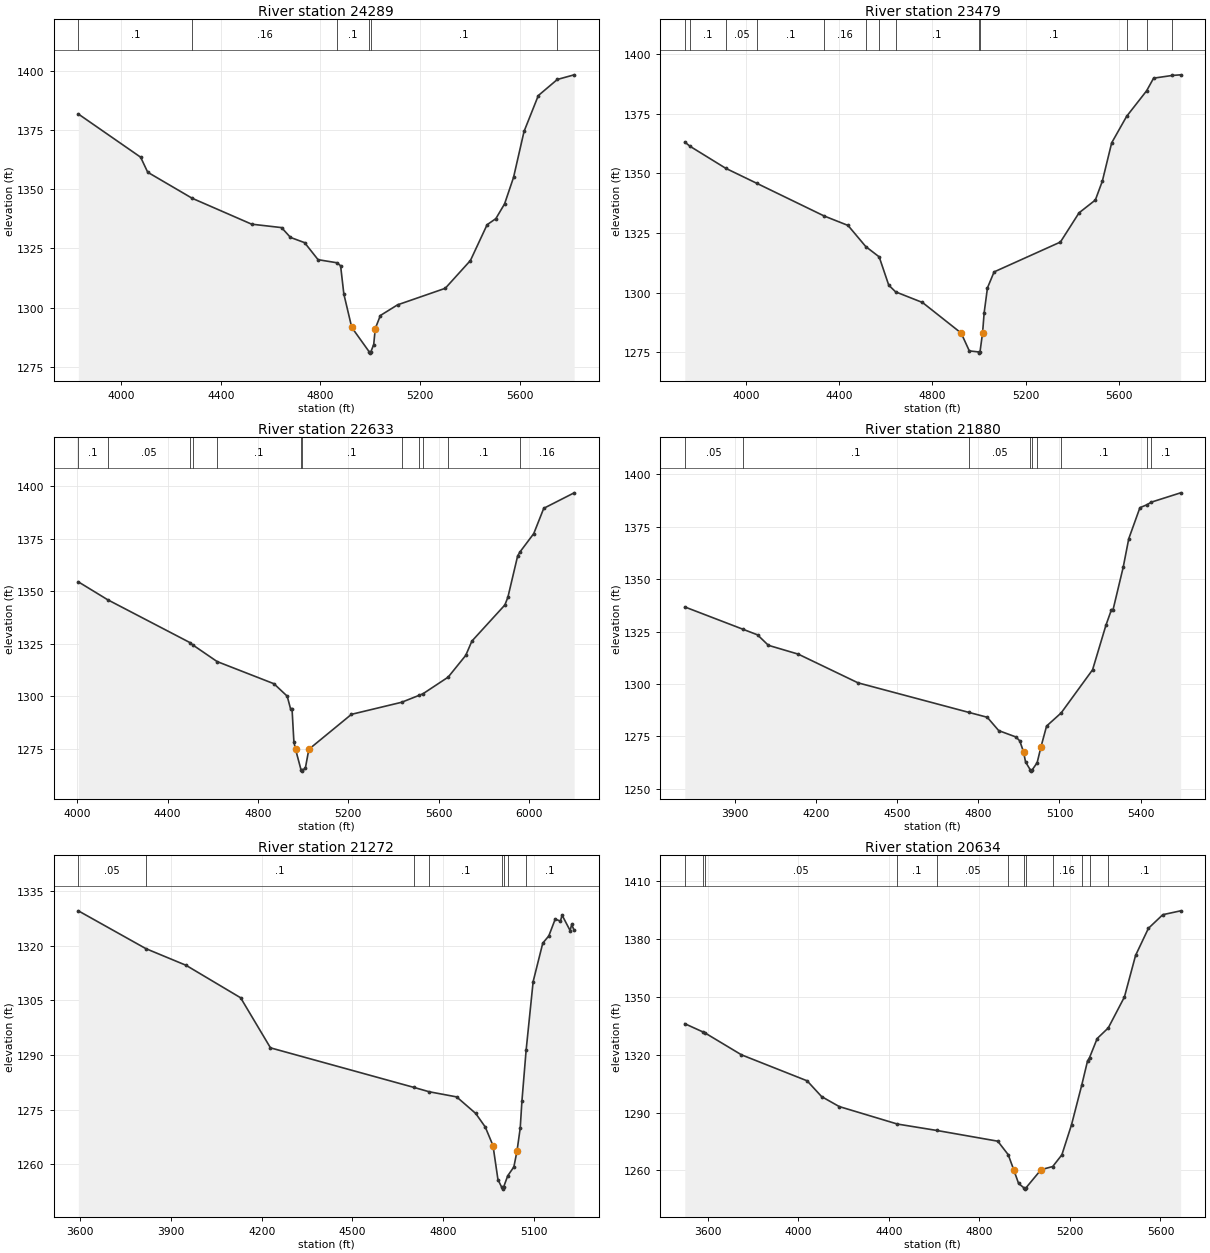
Type RM Length L Ch R = 1 ,24289   ,810,810,810
BEGIN DESCRIPTION:
MCCALL CREEK 46.0
END DESCRIPTION:
XS GIS Cut Line= 4
      2915836.39     10024755.46      2916503.09     10024146.05
      2917159.34     10023932.51      2917465.78     10023678.02
#Sta/Elev= 30
  3827.6 1381.82  4077.9 1363.56  4106.3  1357.2  4284.9  1346.2  4523.8 1335.25
    4644  1333.8  4679.8 1329.65  4736.5 1327.44  4790.6 1320.24  4866.8 1318.93
  4881.1 1317.67  4894.2  1305.7  4925.8 1291.63  4996.4 1281.24  4999.2 1280.74
  5002.4 1281.24  5014.1 1284.36  5020.4 1291.11  5040.8 1296.64  5109.9 1301.15
  5301.5 1308.14  5402.6 1319.89  5469.6 1335.02  5504.7 1337.58  5539.9 1343.85
  5575.8 1355.02    5618 1374.46  5675.3 1389.61  5751.7 1396.42  5819.3 1398.38
#Mann= 6 ,-1 , 0
  3827.6      .1       0  4284.9     .16       0  4866.8      .1       0
  4996.4     .07       0  5002.4      .1       0  5751.7     .16       0
Bank Sta=4925.8,5020.4
XS Rating Curve= 0 ,0
Exp/Cntr=0.3,0.1

Type RM Length L Ch R = 1 ,23479   ,846,846,846
BEGIN DESCRIPTION:
MCCALL CREEK 44.0
END DESCRIPTION:
XS GIS Cut Line= 4
      2916367.67     10025146.06      2917326.01     10024567.93
      2917628.09     10024213.76      2917659.29     10023667.77
#Sta/Elev= 30
  3735.2 1363.06    3758 1361.27  3911.9 1352.03  4046.2 1345.71  4334.3 1332.09
  4436.9 1328.13  4513.3 1319.26  4570.8 1314.97    4612 1303.11  4641.6 1300.29
    4757 1295.85  4923.3 1283.04  4958.4 1275.56  4998.3 1275.13    5001 1274.63
  5004.3 1275.13  5015.5 1283.21  5022.1 1291.49  5036.4 1301.99  5064.9 1308.66
    5350 1321.17  5430.1 1333.41  5500.2 1338.77  5530.3  1346.7  5570.4 1362.74
  5634.7 1373.84  5720.6 1384.54  5750.6 1389.83  5831.8 1390.98  5866.8 1391.23
#Mann= 13 ,-1 , 0
  3735.2     .05       0    3758      .1       0  3911.9     .05       0
  4046.2      .1       0  4334.3     .16       0  4513.3      .1       0
  4570.8     .16       0  4641.6      .1       0  4998.3     .07       0
  5004.3      .1       0  5634.7     .16       0  5720.6      .1       0
  5831.8     .16       0
Bank Sta=4923.3,5015.5
XS Rating Curve= 0 ,0
Exp/Cntr=0.3,0.1

Type RM Length L Ch R = 1 ,22633   ,753,753,753
BEGIN DESCRIPTION:
MCCALL CREEK 42.0
END DESCRIPTION:
XS GIS Cut Line= 4
      2916789.58     10025750.21       2917508.3     10025411.68
      2917997.89     10024573.13      2918346.82     10024323.15
#Sta/Elev= 30
  4005.2 1354.49  4134.9 1345.99    4501 1325.51  4510.8 1324.57  4619.5 1316.59
    4871 1306.05  4929.7 1300.14  4945.4  1293.8  4951.2    1294  4959.4 1278.31
  4966.9 1274.79  4991.2    1265  4993.9  1264.5  4997.2    1265  5009.9 1265.82
  5025.6 1274.88  5214.1  1291.5  5436.1 1297.23    5515 1300.59  5531.1 1301.31
  5642.2 1309.19    5720 1319.53  5747.3 1326.33  5893.3  1343.5  5906.7 1347.23
  5949.8 1366.84  5961.1 1368.85  6021.1 1377.44  6065.3 1389.45  6199.9 1396.81
#Mann= 12 ,-1 , 0
  4005.2      .1       0  4134.9     .05       0    4501      .1       0
  4510.8     .05       0  4619.5      .1       0  4991.2     .07       0
  4997.2      .1       0  5436.1     .05       0    5515      .1       0
  5531.1     .05       0  5642.2      .1       0  5961.1     .16       0
Bank Sta=4966.9,5025.6
XS Rating Curve= 0 ,0
Exp/Cntr=0.3,0.1

Type RM Length L Ch R = 1 ,21880   ,608,608,608
BEGIN DESCRIPTION:
MCCALL CREEK 41.0
END DESCRIPTION:
XS GIS Cut Line= 4
      2917090.79     10025810.11      2918006.57     10025731.99
       2918462.3     10025250.22      2918704.37      10025189.7
#Sta/Elev= 30
  3715.7 1336.73  3929.8 1326.13  3984.3 1323.43  4024.5 1318.44  4134.9 1314.23
  4355.7 1300.55  4764.7 1286.48    4833 1284.15  4875.5 1277.78    4939 1274.75
  4953.2 1272.91  4967.3 1267.56  4974.6 1262.85  4992.6 1258.97  4995.4 1258.47
  4998.6 1258.97  5017.4 1262.48  5031.2 1269.85  5052.3 1279.96  5106.1  1286.2
  5222.2 1306.77  5271.5 1327.99  5292.1 1335.48    5298 1335.48  5335.3 1355.62
  5355.9 1369.25  5397.1 1384.04    5422 1385.38  5439.8  1386.7  5547.5 1391.12
#Mann= 9 ,-1 , 0
  3715.7     .05       0  3929.8      .1       0  4764.7     .05       0
  4992.6    .035       0  4998.6     .05       0  5017.4     .16       0
  5106.1      .1       0    5422     .16       0  5439.8      .1       0
Bank Sta=4967.3,5031.2
XS Rating Curve= 0 ,0
Exp/Cntr=0.3,0.1

Type RM Length L Ch R = 1 ,21272   ,638,638,638
BEGIN DESCRIPTION:
MCCALL CREEK 40.0
END DESCRIPTION:
XS GIS Cut Line= 3
      2917203.58     10025901.26      2918405.87     10026009.77
       2918818.2     10025875.22
#Sta/Elev= 30
  3593.3 1329.59  3817.2  1319.2  3949.6 1314.65  4130.4 1305.73  4229.2 1291.99
  4704.9 1281.11  4754.5 1279.94  4845.3 1278.53  4908.4 1273.99    4940 1270.27
  4965.6 1265.17    4982 1255.84  4994.5 1253.72  4997.3 1253.22  5000.5 1253.72
  5014.3 1256.87  5034.7 1259.32  5045.1 1263.69  5055.7 1269.97  5061.3 1277.34
  5075.2  1291.3  5098.5 1310.19  5130.4 1320.74  5150.3  1322.7  5171.4  1327.3
  5188.9 1326.78  5194.1 1328.42  5220.8 1324.18    5226 1325.85  5234.2 1324.22
#Mann= 8 ,-1 , 0
  3593.3     .05       0  3817.2      .1       0  4704.9     .05       0
  4754.5      .1       0  4994.5     .07       0  5000.5      .1       0
  5014.3     .16       0  5075.2      .1       0
Bank Sta=4965.6,5045.1
XS Rating Curve= 0 ,0
Exp/Cntr=0.3,0.1

Type RM Length L Ch R = 1 ,20634   ,590,590,590
BEGIN DESCRIPTION:
MCCALL CREEK 39.0
END DESCRIPTION:
XS GIS Cut Line= 2
      2917893.71     10027602.66      2919369.42     10025983.72
#Sta/Elev= 30
  3498.4 1336.04  3580.5 1331.67  3586.2 1331.36  3748.8 1319.91  4038.7 1306.45
  4102.9 1298.27  4180.6 1293.11  4437.7 1284.04  4611.4 1280.73  4881.2 1275.16
  4927.3 1268.17  4952.2 1260.17  4973.1 1253.26  4998.5 1250.82  5001.2 1250.32
  5004.5 1250.82  5072.4  1260.4  5123.9 1262.03  5164.3 1268.08  5206.9 1283.65
  5252.1  1304.2  5277.8 1316.77  5286.7  1318.5  5320.4 1328.37  5369.3 1333.85
  5440.7 1349.88    5490 1371.44  5546.7 1385.47  5610.2 1392.53    5689 1394.53
#Mann= 12 ,-1 , 0
  3498.4     .05       0  3580.5      .1       0  3586.2     .05       0
  4437.7      .1       0  4611.4     .05       0  4927.3      .1       0
  4998.5     .07       0  5004.5      .1       0  5123.9     .16       0
  5252.1      .1       0  5286.7     .16       0  5369.3      .1       0
Bank Sta=4952.2,5072.4
XS Rating Curve= 0 ,0
Exp/Cntr=0.3,0.1

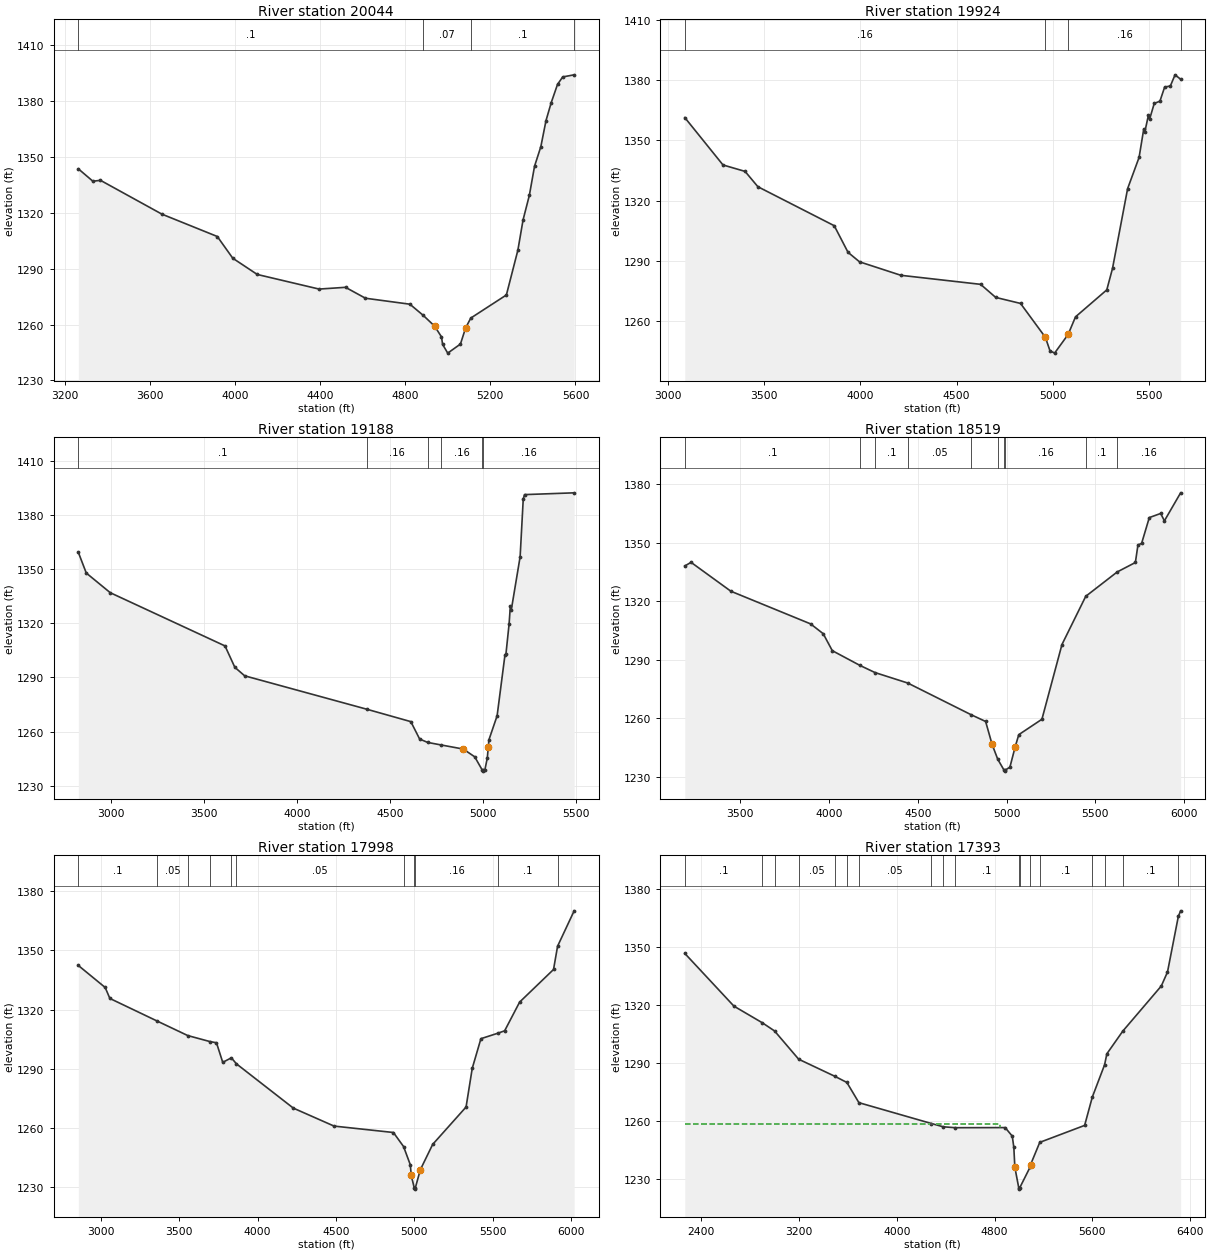
Type RM Length L Ch R = 1 ,20044   ,120,120,120
BEGIN DESCRIPTION:
MCCALL CREEK 38.0
END DESCRIPTION:
XS GIS Cut Line= 3
       2918030.9     10027779.71      2919350.32     10026932.51
      2919631.56      10026224.2
#Sta/Elev= 30
  3263.8 1343.69  3332.2 1337.03  3367.9 1337.51  3656.7 1319.32  3916.9 1307.31
  3989.6 1295.63  4104.7  1286.9  4395.2 1279.05  4519.4 1279.99  4613.2 1274.12
    4822 1270.91  4884.3 1264.94  4938.1 1259.12  4970.4 1253.35  4975.8 1249.27
  4999.8 1244.61  5059.5 1249.49  5083.8 1258.15  5108.1 1263.46  5275.4 1275.87
  5329.4 1299.95  5353.8 1316.24  5383.4 1329.47  5407.7 1345.08  5437.4 1355.64
  5461.7 1369.67  5486.1 1379.27  5515.7 1389.08  5540.1  1393.1  5593.9 1394.23
#Mann= 4 ,-1 , 0
  3263.8      .1       0  4884.3     .07       0  5108.1      .1       0
  5593.9      .1       0
Bank Sta=4938.1,5083.8
XS Rating Curve= 0 ,0
Exp/Cntr=0.3,0.1

Type RM Length L Ch R = 1 ,19924   ,736,736,736
BEGIN DESCRIPTION:
MCCALL CREEK 36.0
END DESCRIPTION:
XS GIS Cut Line= 3
       2918037.8     10027967.24      2919426.71     10027064.45
      2919763.47     10026210.38
#Sta/Elev= 30
  3088.3 1361.38  3286.6 1337.78  3401.3 1334.57  3467.8 1326.94  3864.3 1307.52
  3935.9 1294.26  3995.5 1289.54  4210.5 1282.82  4624.3 1278.32  4702.7 1271.81
  4831.6 1268.81  4960.6 1251.94  4984.4 1245.26  5008.5 1244.06  5078.8 1253.36
  5117.1 1262.13  5279.5 1275.56  5309.2 1286.23  5387.7    1326  5447.2 1341.54
  5471.6 1355.79    5477 1354.24    5496 1362.68  5501.4 1360.44  5525.8 1368.39
  5555.5 1369.57  5579.9 1376.56  5609.6 1377.12    5634 1382.67  5662.9 1380.47
#Mann= 4 ,-1 , 0
  3088.3     .16       0  4960.6     .07       0  5078.8     .16       0
  5662.9      .1       0
Bank Sta=4960.6,5078.8
XS Rating Curve= 0 ,0
Exp/Cntr=0.3,0.1

Type RM Length L Ch R = 1 ,19188   ,669,669,669
BEGIN DESCRIPTION:
MCCALL CREEK 35.0
END DESCRIPTION:
XS GIS Cut Line= 2
      2918107.27     10027996.74      2920560.37     10026955.08
#Sta/Elev= 30
  2822.7 1359.39  2865.4  1347.9  2994.5 1336.98  3611.2 1307.48  3663.9 1295.63
  3716.7 1290.92  4372.6 1272.41  4609.9 1265.51  4657.2 1255.87  4700.1 1253.99
  4771.1 1252.61  4891.8 1250.31  4953.4    1246  4994.3 1238.57  4997.1 1238.07
  5000.3 1238.57  5007.7 1238.67    5021 1245.36 5026.14 1251.31  5029.4 1255.35
  5073.7 1268.76  5115.6 1302.23    5121 1302.85  5138.1 1319.65  5144.7 1329.42
  5150.1 1327.59  5197.4 1356.94  5214.1 1388.89  5221.1 1391.38  5487.8 1392.37
#Mann= 6 ,-1 , 0
  2822.7      .1       0  4372.6     .16       0  4700.1      .1       0
  4771.1     .16       0  4994.3     .07       0  5000.3     .16       0
Bank Sta=4891.8,5026.14
XS Rating Curve= 0 ,0
Exp/Cntr=0.3,0.1

Type RM Length L Ch R = 1 ,18519   ,521,521,521
BEGIN DESCRIPTION:
MCCALL CREEK 33.0
END DESCRIPTION:
XS GIS Cut Line= 4
      2918273.88      10028022.8      2919560.39     10027772.79
      2920305.18     10027804.04       2920763.5     10027231.13
#Sta/Elev= 30
  3189.6 1338.05  3224.8  1339.9  3448.9 1325.11  3897.3  1308.4  3968.5 1303.36
  4019.4 1294.69  4175.4 1287.12  4260.1 1283.47  4443.8 1278.13    4800 1261.93
  4882.1 1258.45  4918.6 1246.71  4950.2 1239.15  4985.7 1233.53  4988.4 1233.03
  4991.7 1233.53  5018.7 1235.03  5048.7 1245.54  5068.8  1251.7  5198.9 1259.58
  5311.7 1297.84  5445.5 1322.51  5622.5 1334.98  5724.7 1339.82  5739.1 1348.72
  5759.9 1349.63  5803.1 1362.81  5867.1 1364.92    5888 1361.14  5979.3 1375.48
#Mann= 10 ,-1 , 0
  3189.6      .1       0  4175.4     .05       0  4260.1      .1       0
  4443.8     .05       0    4800      .1       0  4950.2     .16       0
  4985.7     .07       0  4991.7     .16       0  5445.5      .1       0
  5622.5     .16       0
Bank Sta=4918.6,5048.7
XS Rating Curve= 0 ,0
Exp/Cntr=0.3,0.1

Type RM Length L Ch R = 1 ,17998   ,605,605,605
BEGIN DESCRIPTION:
MCCALL CREEK 32.0
END DESCRIPTION:
XS GIS Cut Line= 4
      2918357.24     10028387.37      2920232.26     10028387.37
      2920549.97     10027981.12      2920820.52     10027257.92
#Sta/Elev= 30
  2856.9 1342.33  3028.1 1331.18  3058.1 1325.62  3361.8  1314.1    3555 1306.82
  3695.1 1303.81  3738.1 1303.18  3778.1 1293.26  3833.1 1295.55  3865.4 1292.51
  4228.1 1270.09  4488.1 1260.98  4866.8 1257.73  4931.5 1250.62  4974.4 1241.42
  4980.7 1235.98  5000.1 1229.55  5002.9 1229.05  5006.1 1229.55  5038.6 1238.89
  5117.3 1251.71  5330.3 1270.64  5369.7 1290.24    5425 1305.24    5534 1308.04
  5576.4 1309.24  5671.9 1323.77  5888.2 1340.29  5914.1 1352.09  6019.8    1370
#Mann= 11 ,-1 , 0
  2856.9      .1       0  3361.8     .05       0    3555      .1       0
  3695.1     .05       0  3833.1      .1       0  3865.4     .05       0
  4931.5     .16       0  5000.1     .07       0  5006.1     .16       0
    5534      .1       0  5914.1     .16       0
Bank Sta=4980.7,5038.6
XS Rating Curve= 0 ,0
Exp/Cntr=0.3,0.1

Type RM Length L Ch R = 1 ,17393   ,698,698,698
BEGIN DESCRIPTION:
MCCALL CREEK 30.0
END DESCRIPTION:
XS GIS Cut Line= 4
      2918257.52     10028526.76      2920753.16     10028696.03
      2921035.28     10028318.43      2920870.53     10027247.56
#Sta/Elev= 30
  2266.2 1346.71  2668.1 1319.45  2901.8 1310.79  3000.4 1306.62  3197.6 1292.01
  3493.4 1283.18    3592 1279.99  3690.6 1269.53  4283.4 1258.76  4380.7 1257.06
  4479.3 1256.59    4887 1256.65  4945.2 1252.23  4957.9 1246.42  4966.3 1236.11
  4998.7 1225.33  5001.4 1224.83  5004.7 1225.33  5091.1 1236.23    5095 1237.52
  5170.1 1249.01  5537.1 1257.78  5599.9 1272.42  5700.1 1289.07  5719.2 1294.82
    5849  1306.5  6164.4 1329.87    6215 1337.09  6303.8 1365.89  6322.4 1368.73
#Mann= 18 ,-1 , 0
  2266.2      .1       0  2901.8     .05       0  3000.4     .16       0
  3197.6     .05       0  3493.4     .16       0    3592      .1       0
  3690.6     .05       0  4283.4      .1       0  4380.7     .05       0
  4479.3      .1       0  4998.7     .07       0  5004.7      .1       0
  5091.1     .16       0  5170.1      .1       0  5599.9     .05       0
  5700.1     .16       0    5849      .1       0  6303.8     .16       0
#XS Ineff= 2 , 0
         4847.89 1258.65
Permanent Ineff=
       T       T
Bank Sta=4966.3,5095
XS Rating Curve= 0 ,0
Exp/Cntr=0.3,0.1

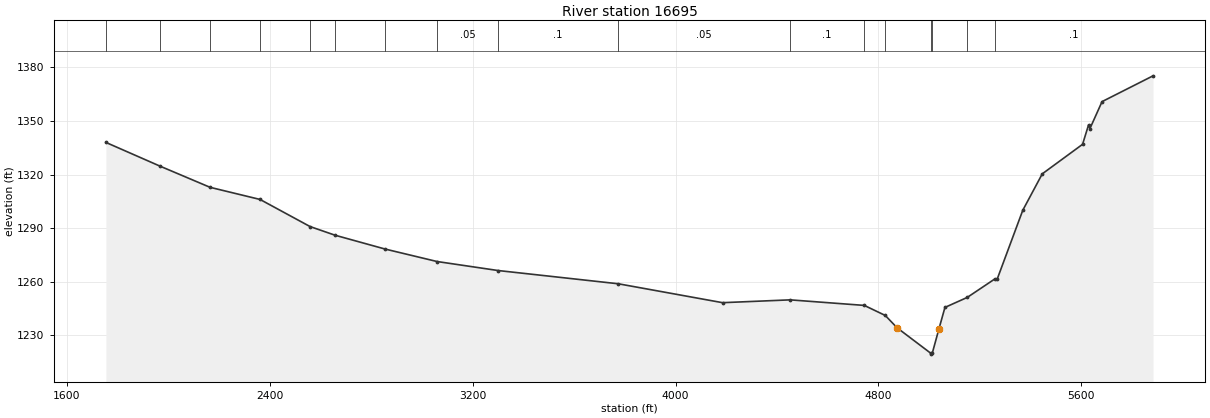
Type RM Length L Ch R = 1 ,16695   ,676,676,676
BEGIN DESCRIPTION:
MCCALL CREEK 29.0
END DESCRIPTION:
XS GIS Cut Line= 3
      2918273.93     10028793.62      2921034.34     10029007.16
      2922289.51     10028481.14
#Sta/Elev= 30
  1753.5 1338.02    1967 1324.73  2164.3 1312.88  2361.5 1306.08  2558.7  1290.9
  2657.4 1286.05  2854.6 1278.31  3059.3 1271.33  3299.8 1266.29  3774.4 1258.86
  4185.3 1248.28    4452 1249.86  4744.4 1246.75  4827.1 1241.12  4873.6 1234.23
  5006.4 1219.97  5009.1 1219.47  5012.4 1219.97  5038.6 1233.55  5062.4 1245.63
  5150.4 1251.23  5258.7 1261.53  5268.9 1261.65  5369.4 1300.05  5446.2 1320.42
  5605.1 1336.96  5628.9 1347.89  5634.3 1345.81  5681.9 1360.86  5883.1 1375.31
#Mann= 17 ,-1 , 0
  1753.5     .05       0    1967     .16       0  2164.3      .1       0
  2361.5     .16       0  2558.7     .05       0  2657.4     .16       0
  2854.6      .1       0  3059.3     .05       0  3299.8      .1       0
  3774.4     .05       0    4452      .1       0  4744.4     .16       0
  4827.1      .1       0  5006.4     .07       0  5012.4      .1       0
  5150.4     .16       0  5258.7      .1       0
Bank Sta=4873.6,5038.6
XS Rating Curve= 0 ,0
Exp/Cntr=0.3,0.1