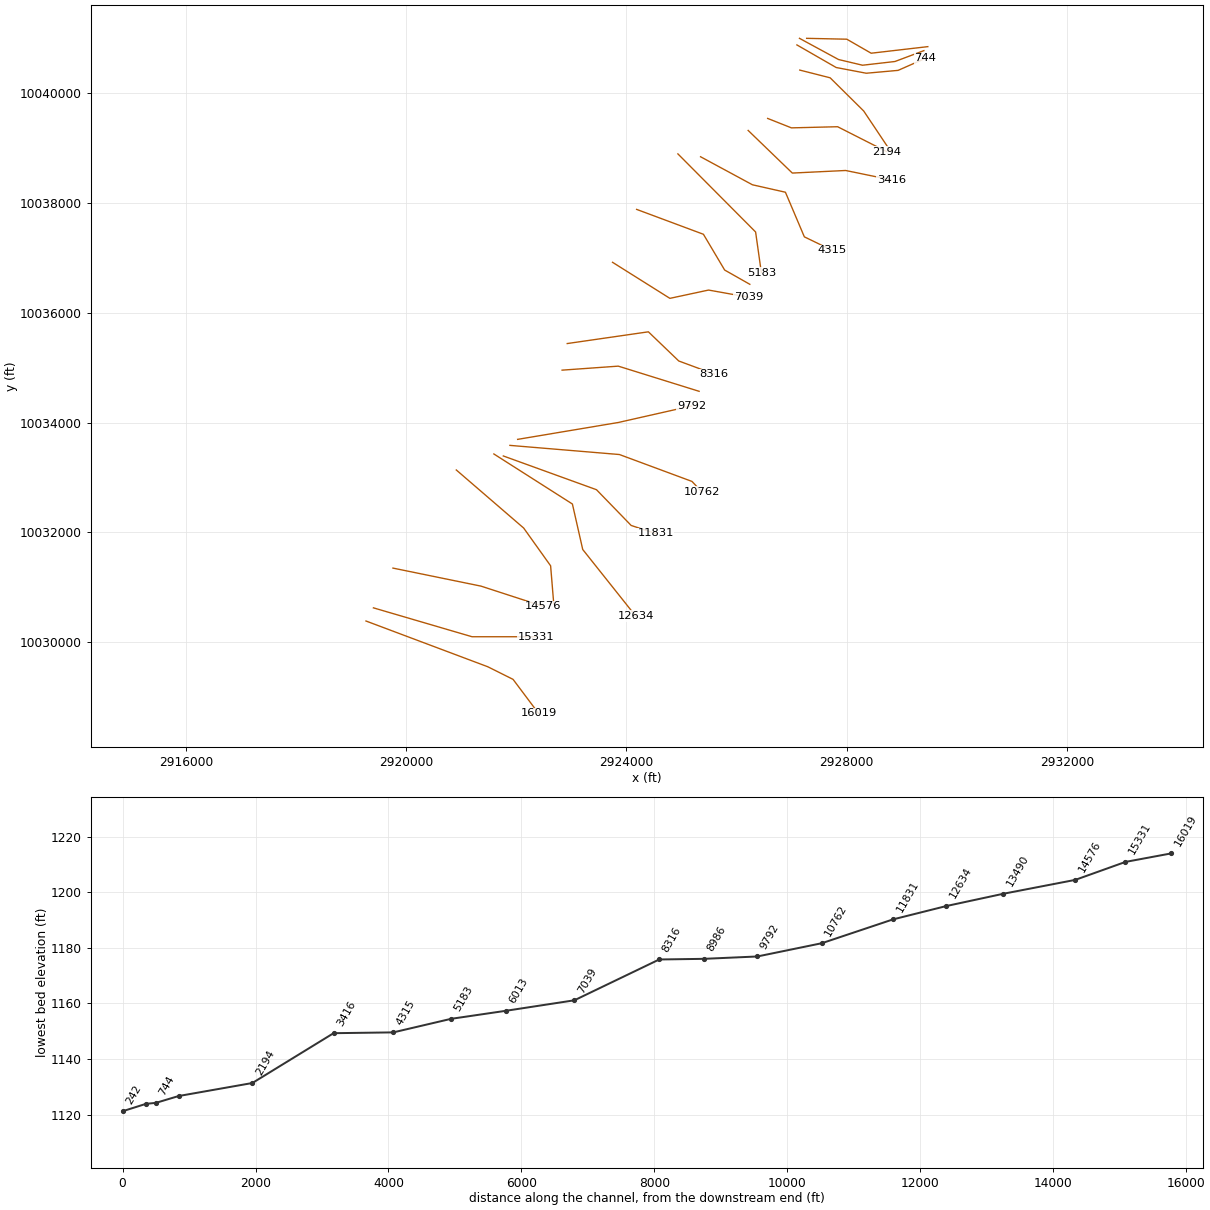
HEC-RAS study MCCALL CREEK.prj: MCCALL CREEK Base Level Engineering

--- MCCALL CREEK.g01 (geometry) --- (continued)

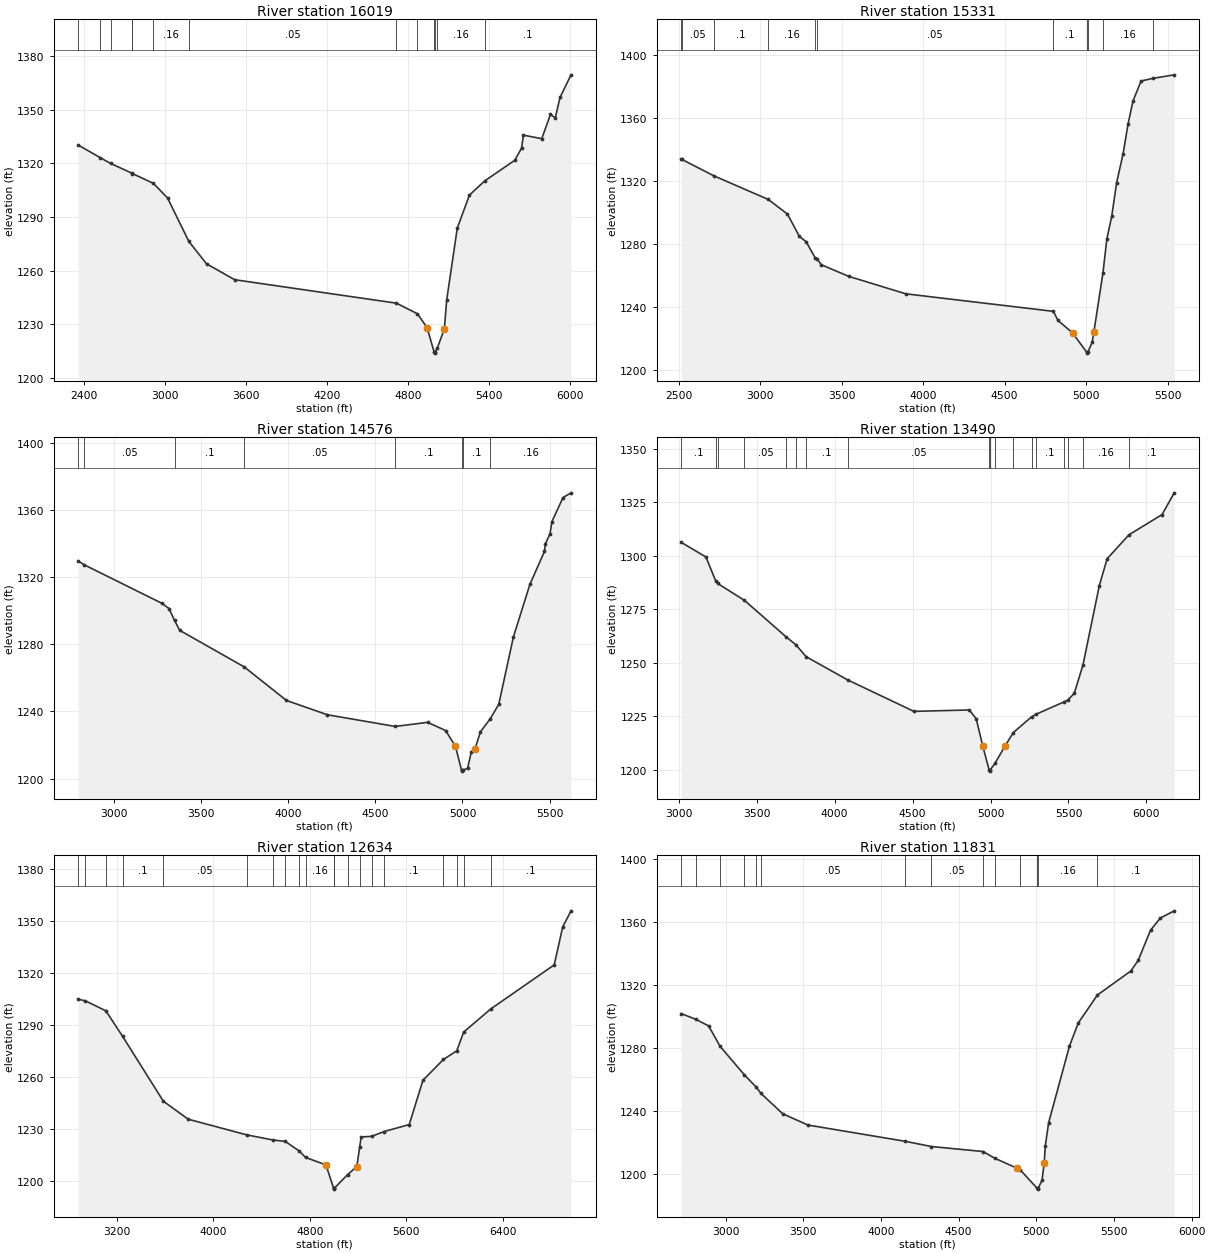
Type RM Length L Ch R = 1 ,16019   ,688,688,688
BEGIN DESCRIPTION:
MCCALL CREEK 28.0
END DESCRIPTION:
XS GIS Cut Line= 4
      2919268.74     10030387.36      2921482.26     10029554.04
      2921940.59     10029324.87      2922403.79     10028705.54
#Sta/Elev= 30
  2357.2 1330.16  2519.1 1323.18  2596.7  1319.9  2756.4  1314.4  2758.9 1314.24
  2915.1 1308.73  3019.4 1300.56  3176.8 1276.35  3307.9 1263.85  3516.6 1254.96
  4714.9 1241.87  4870.5 1235.94  4941.7 1228.22  4994.3 1214.48  4997.1 1213.98
  5000.3 1214.48  5018.9 1217.05    5070 1227.59  5086.8 1243.53  5165.4 1283.76
  5255.6 1302.24  5368.9 1310.14  5591.2 1321.65  5641.2 1328.39  5655.8 1335.67
  5791.3 1333.71  5855.9 1347.27  5891.3 1345.29  5926.7 1356.78  6008.2 1369.36
#Mann= 13 ,-1 , 0
  2357.2      .1       0  2519.1     .05       0  2596.7      .1       0
  2756.4     .05       0  2758.9      .1       0  2915.1     .16       0
  3176.8     .05       0  4714.9     .16       0  4870.5      .1       0
  4994.3     .07       0  5000.3      .1       0  5018.9     .16       0
  5368.9      .1       0
Bank Sta=4941.7,5070
XS Rating Curve= 0 ,0
Exp/Cntr=0.3,0.1

Type RM Length L Ch R = 1 ,15331   ,755,755,755
BEGIN DESCRIPTION:
MCCALL CREEK 26.0
END DESCRIPTION:
XS GIS Cut Line= 3
      2919404.09     10030626.97       2921195.8     10030100.91
      2922352.06     10030100.91
#Sta/Elev= 30
  2516.8 1333.63  2520.3 1333.63  2716.3 1323.25    3050 1308.28  3167.5 1299.02
  3240.5 1284.89  3282.2 1281.51  3336.5 1271.49  3349.4 1270.42    3376 1266.88
  3543.9 1259.54  3893.4  1248.5  4799.2 1237.39  4826.8 1231.66  4916.8 1223.72
  5003.8 1211.42  5006.6 1210.92  5009.8 1211.42  5036.8 1217.79  5046.8 1224.02
  5102.9 1261.64  5126.8 1283.19  5156.8 1297.64  5186.8 1318.88  5226.8 1337.33
  5256.8 1355.99  5286.8 1370.54  5336.8 1383.33  5407.6    1385  5540.4 1387.26
#Mann= 11 ,-1 , 0
  2516.8      .1       0  2520.3     .05       0  2716.3      .1       0
    3050     .16       0  3336.5      .1       0  3349.4     .05       0
  4799.2      .1       0  5003.8     .07       0  5009.8      .1       0
  5102.9     .16       0  5407.6      .1       0
Bank Sta=4916.8,5046.8
XS Rating Curve= 0 ,0
Exp/Cntr=0.3,0.1

Type RM Length L Ch R = 1 ,14576   ,1086,1086,1086
BEGIN DESCRIPTION:
MCCALL CREEK 25.0
END DESCRIPTION:
XS GIS Cut Line= 3
      2919758.27     10031350.92      2921357.26     10031022.79
      2922492.65     10030653.01
#Sta/Elev= 30
  2796.2 1329.61  2831.4 1327.33  3276.2 1304.42    3317 1301.31  3348.6 1294.27
  3378.3 1288.32  3748.1 1266.55  3990.8 1246.54  4225.6 1238.02  4614.5 1231.07
    4800 1233.52    4903 1228.65  4959.6 1219.29  4994.7 1204.96  4997.5 1204.46
  5000.7 1204.96  5029.3 1206.15  5050.1 1215.66  5071.3 1217.49  5102.9 1227.85
  5159.4 1235.65    5208 1244.25  5292.2 1284.42  5386.8 1315.73  5470.3 1335.35
  5475.6 1339.82  5502.2 1345.92    5513 1353.11  5576.6 1367.41  5622.6 1370.22
#Mann= 8 ,-1 , 0
  2796.2      .1       0  2831.4     .05       0  3348.6      .1       0
  3748.1     .05       0  4614.5      .1       0  4994.7     .07       0
  5000.7      .1       0  5159.4     .16       0
Bank Sta=4959.6,5071.3
XS Rating Curve= 0 ,0
Exp/Cntr=0.3,0.1

Type RM Length L Ch R = 1 ,13490   ,856,856,856
BEGIN DESCRIPTION:
MCCALL CREEK 23.0
END DESCRIPTION:
XS GIS Cut Line= 4
      2920909.33     10033137.38       2922133.3     10032080.08
      2922622.89     10031392.58      2922680.18     10030694.64
#Sta/Elev= 30
  3017.1 1306.29  3174.6 1299.48  3236.5 1288.42  3249.3 1287.13  3421.7 1279.22
  3689.4 1262.14  3751.4  1258.5  3816.9 1252.93  4083.9 1242.05  4508.4 1227.37
  4864.2 1228.02  4908.4 1223.89  4950.2 1211.23  4991.5 1199.95  4994.2 1199.45
  4997.5 1199.95  5029.2 1203.15  5095.3 1211.41  5146.4 1217.48  5263.6 1224.81
  5289.9 1225.94  5470.8 1231.77  5494.9 1232.56  5537.6 1235.81  5593.3 1249.05
  5698.1 1286.14  5748.3 1298.68  5888.3 1309.85  6100.6 1319.31  6178.8 1329.46
#Mann= 18 ,-1 , 0
  3017.1      .1       0  3236.5     .05       0  3249.3      .1       0
  3421.7     .05       0  3689.4      .1       0  3751.4     .05       0
  3816.9      .1       0  4083.9     .05       0  4991.5    .035       0
  4997.5     .05       0  5029.2      .1       0  5146.4     .16       0
  5263.6     .05       0  5289.9      .1       0  5470.8     .05       0
  5494.9      .1       0  5593.3     .16       0  5888.3      .1       0
Bank Sta=4950.2,5095.3
XS Rating Curve= 0 ,0
Exp/Cntr=0.3,0.1

Type RM Length L Ch R = 1 ,12634   ,803,803,803
BEGIN DESCRIPTION:
MCCALL CREEK 21.0
END DESCRIPTION:
XS GIS Cut Line= 4
       2921591.6     10033429.06      2923018.72     10032517.58
      2923206.22     10031689.45      2924168.64     10030477.32
#Sta/Elev= 30
  2877.8 1304.69  2938.5  1303.7  3107.3 1297.98  3246.8 1283.17  3584.2 1245.81
  3791.2 1235.39  4276.6 1226.36  4491.4 1223.45  4596.7 1222.57  4714.2 1216.94
  4764.3 1213.34    4934 1209.03  4997.4 1195.54  5000.2 1195.04  5003.4 1195.54
  5113.8 1203.45  5190.3 1208.06  5213.7 1219.34  5226.4 1225.15  5313.6 1225.51
  5413.5 1228.22  5625.2 1232.32  5738.9 1257.87  5909.2 1269.91  6019.6 1274.87
  6076.8  1285.7  6300.8    1299  6828.4 1324.49  6898.8 1346.43    6968 1355.69
#Mann= 20 ,-1 , 0
  2877.8      .1       0  2938.5      .1       0  3107.3     .16       0
  3246.8      .1       0  3584.2     .05       0  4276.6      .1       0
  4491.4     .05       0  4596.7      .1       0  4714.2     .05       0
  4764.3     .16       0  4997.4     .07       0  5003.4     .16       0
  5113.8     .05       0  5213.7     .16       0  5313.6      .1       0
  5413.5      .1       0  5909.2     .16       0  6019.6      .1       0
  6076.8     .16       0  6300.8      .1       0
Bank Sta=4934,5190.3
XS Rating Curve= 0 ,0
Exp/Cntr=0.3,0.1

Type RM Length L Ch R = 1 ,11831   ,1069,1069,1069
BEGIN DESCRIPTION:
MCCALL CREEK 20.0
END DESCRIPTION:
XS GIS Cut Line= 4
      2921763.55     10033392.57      2923456.22       10032778.
      2924086.43     10032126.95      2924529.14     10031981.12
#Sta/Elev= 30
    2715 1301.71  2807.9 1298.13  2890.5 1293.93  2963.9 1280.99  3120.5 1262.84
  3197.2    1255  3227.1 1251.06  3367.4 1238.12  3528.8 1230.97  4157.1  1220.6
  4324.7 1217.29    4657 1214.13  4733.2 1209.81  4873.9 1203.63  4895.8 1202.55
  5005.5 1190.73  5008.2 1190.23  5011.5 1190.73  5036.7 1195.79  5050.7 1206.99
  5057.9 1217.77    5079 1232.34  5213.5 1281.18  5270.1 1295.81  5392.9 1313.53
  5608.1  1328.8  5655.7 1335.53  5735.2 1354.75  5798.8  1362.5    5888 1367.06
#Mann= 14 ,-1 , 0
    2715      .1       0  2807.9     .16       0  2963.9      .1       0
  3120.5     .05       0  3197.2      .1       0  3227.1     .05       0
  4157.1      .1       0  4324.7     .05       0    4657      .1       0
  4733.2     .05       0  4895.8     .16       0  5005.5     .07       0
  5011.5     .16       0  5392.9      .1       0
Bank Sta=4873.9,5050.7
XS Rating Curve= 0 ,0
Exp/Cntr=0.3,0.1

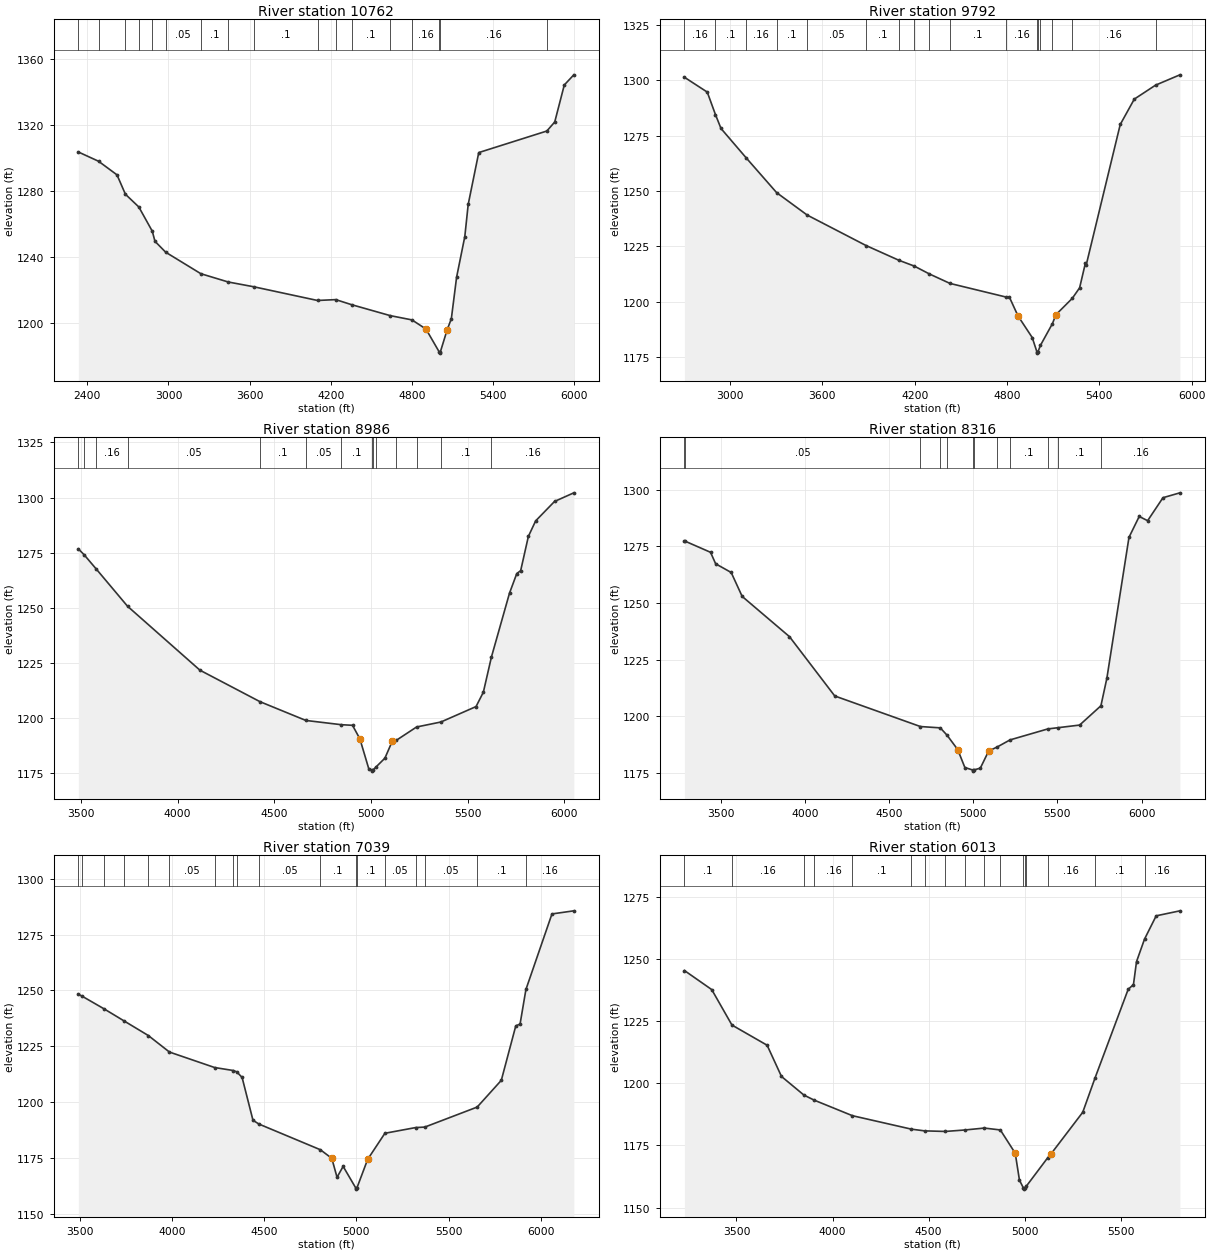
Type RM Length L Ch R = 1 ,10762   ,970,970,970
BEGIN DESCRIPTION:
MCCALL CREEK 18.0
END DESCRIPTION:
XS GIS Cut Line= 4
      2921883.29     10033585.29      2923872.89     10033418.62
      2925190.59     10032929.04      2925371.75     10032737.53
#Sta/Elev= 30
  2333.1 1303.67  2482.8 1298.05  2619.3 1289.79  2681.5 1278.05  2780.8 1270.31
  2880.2 1255.65  2900.3 1249.49  2979.5 1242.88  3239.8 1229.84  3442.2 1224.82
  3631.4 1221.92  4102.8 1213.61  4237.8 1214.13  4354.7 1211.07  4641.4 1204.41
  4801.4 1201.83    4905 1196.31  5004.7 1182.18  5007.5 1181.68  5010.7 1182.18
    5061 1195.57    5093  1202.6  5131.8 1227.72  5192.6 1252.41  5217.6 1271.87
  5295.7 1303.31  5799.3 1316.38  5857.8 1321.85  5928.6 1344.31    5999 1350.46
#Mann= 17 ,-1 , 0
  2333.1      .1       0  2482.8     .16       0  2681.5      .1       0
  2780.8     .16       0  2880.2      .1       0  2979.5     .05       0
  3239.8      .1       0  3442.2     .05       0  3631.4      .1       0
  4102.8     .05       0  4237.8     .16       0  4354.7      .1       0
  4641.4     .05       0  4801.4     .16       0  5004.7     .07       0
  5010.7     .16       0  5799.3      .1       0
Bank Sta=4905,5061
XS Rating Curve= 0 ,0
Exp/Cntr=0.3,0.1

Type RM Length L Ch R = 1 ,9792    ,806,806,806
BEGIN DESCRIPTION:
MCCALL CREEK 16.0
END DESCRIPTION:
XS GIS Cut Line= 3
      2922023.94     10033694.66      2923852.05     10034001.95
      2925184.43     10034303.82
#Sta/Elev= 30
    2704  1301.3  2852.4 1294.61  2905.9 1284.43  2941.8  1278.2  3104.6 1265.02
  3303.3 1249.27  3501.9 1239.16  3884.1 1225.43  4097.9 1218.77  4197.2 1216.17
  4296.5 1212.59  4429.8 1208.34  4795.2 1202.18  4815.1 1202.25  4871.9 1193.65
  4964.2 1183.93  4994.9 1177.41  4997.7 1176.91  5000.9 1177.41  5017.5 1180.41
  5095.8 1190.26    5118 1194.23  5224.4 1201.61  5272.1 1206.36  5310.1 1217.63
  5315.2 1216.73  5536.1 1280.01  5627.4 1291.45  5765.5 1297.74  5923.9  1302.4
#Mann= 17 ,-1 , 0
    2704     .16       0  2905.9      .1       0  3104.6     .16       0
  3303.3      .1       0  3501.9     .05       0  3884.1      .1       0
  4097.9     .05       0  4197.2     .16       0  4296.5     .05       0
  4429.8      .1       0  4795.2     .16       0  4994.9     .07       0
  5000.9     .16       0  5017.5     .05       0  5095.8      .1       0
  5224.4     .16       0  5765.5      .1       0
Bank Sta=4871.9,5118
XS Rating Curve= 0 ,0
Exp/Cntr=0.3,0.1

Type RM Length L Ch R = 1 ,8986    ,670,670,670
BEGIN DESCRIPTION:
MCCALL CREEK 14.0
END DESCRIPTION:
XS GIS Cut Line= 3
      2922831.24     10034955.08      2923852.05       10035028.
      2925320.79     10034569.67
#Sta/Elev= 30
  3486.9 1276.79    3517 1274.12  3580.2  1267.6  3741.4 1250.79  4115.7 1221.81
  4426.4 1207.53  4663.4 1199.03    4847  1197.1  4904.6 1196.83  4942.8 1190.68
  4988.4 1177.23  5004.8 1176.56  5007.5 1176.06  5010.8 1176.56  5026.3 1177.95
  5072.2 1181.94  5110.5 1189.68    5131 1190.02  5235.8 1196.06  5361.6 1198.32
  5543.4 1205.32  5581.2 1211.84  5622.7  1227.7  5716.4 1256.73  5754.1 1265.62
  5774.1 1266.91  5813.9 1282.43  5851.6 1289.48  5949.1 1298.27  6048.9 1302.19
#Mann= 14 ,-1 , 0
  3486.9     .16       0    3517     .05       0  3580.2     .16       0
  3741.4     .05       0  4426.4      .1       0  4663.4     .05       0
    4847      .1       0  5004.8     .07       0  5010.8      .1       0
  5026.3     .16       0    5131      .1       0  5235.8     .05       0
  5361.6      .1       0  5622.7     .16       0
Bank Sta=4942.8,5110.5
XS Rating Curve= 0 ,0
Exp/Cntr=0.3,0.1

Type RM Length L Ch R = 1 ,8316    ,1277,1277,1277
BEGIN DESCRIPTION:
MCCALL CREEK 13.0
END DESCRIPTION:
XS GIS Cut Line= 4
      2922924.93     10035439.45      2924398.93       10035653.
      2924951.01     10035121.75      2925595.16     10034882.79
#Sta/Elev= 30
  3285.3  1277.3  3288.9  1277.3  3440.4 1272.38  3470.8 1267.31    3563 1263.48
  3628.2 1252.92  3909.2 1235.16  4178.1 1208.99  4686.8  1195.5  4804.8 1194.92
  4845.2 1191.66  4908.3 1185.34  4950.7 1177.43  4997.1 1176.33  4999.8 1175.83
  5003.1 1176.33  5042.5 1177.14  5092.2 1184.71  5142.7 1186.48  5219.1 1189.61
  5443.4 1194.45  5504.7    1195  5632.3 1196.15  5758.7 1204.66  5794.1 1216.82
  5925.4 1278.98  5986.1 1288.19  6036.2 1286.33  6127.3 1296.47  6227.9 1298.62
#Mann= 12 ,-1 , 0
  3285.3      .1       0  3288.9     .05       0  4686.8      .1       0
  4804.8     .05       0  4845.2     .16       0  4997.1     .07       0
  5003.1     .16       0  5142.7     .05       0  5219.1      .1       0
  5443.4     .05       0  5504.7      .1       0  5758.7     .16       0
Bank Sta=4908.3,5092.2
XS Rating Curve= 0 ,0
Exp/Cntr=0.3,0.1

Type RM Length L Ch R = 1 ,7039    ,1026,1026,1026
BEGIN DESCRIPTION:
MCCALL CREEK 11.0
END DESCRIPTION:
XS GIS Cut Line= 4
      2923747.93     10036918.59      2924789.55     10036262.37
      2925492.68     10036413.41      2926215.02     10036283.49
#Sta/Elev= 30
  3493.4  1248.3  3513.1 1247.46  3632.9 1241.76  3742.3 1236.31  3872.6 1229.83
  3987.1 1222.44    4232 1215.52  4332.9 1214.19  4351.9 1213.57  4380.6  1211.1
  4439.6 1191.94  4471.7 1190.25  4804.7 1178.76  4866.6 1174.92  4894.9 1166.44
    4928 1171.32  4996.5 1161.65  4999.3 1161.15  5002.5 1161.65  5060.9 1174.47
  5154.2 1186.12  5320.3 1188.67  5370.2 1188.89  5654.1 1197.84  5784.8  1209.8
  5863.3 1234.17  5886.4 1234.94  5918.2 1250.43  6059.2  1284.2  6177.6 1285.59
#Mann= 18 ,-1 , 0
  3493.4      .1       0  3513.1     .05       0  3632.9      .1       0
  3742.3     .16       0  3872.6      .1       0  3987.1     .05       0
    4232      .1       0  4332.9     .16       0  4351.9      .1       0
  4471.7     .05       0  4804.7      .1       0  4996.5     .07       0
  5002.5      .1       0  5154.2     .05       0  5320.3      .1       0
  5370.2     .05       0  5654.1      .1       0  5918.2     .16       0
Bank Sta=4866.6,5060.9
XS Rating Curve= 0 ,0
Exp/Cntr=0.3,0.1

Type RM Length L Ch R = 1 ,6013    ,830,830,830
BEGIN DESCRIPTION:
MCCALL CREEK 9.0
END DESCRIPTION:
XS GIS Cut Line= 4
      2924185.39     10037882.16      2925398.93     10037429.04
      2925784.34       10036778.      2926241.64     10036518.17
#Sta/Elev= 30
  3229.4 1245.31  3371.5 1237.64  3476.7 1223.38  3659.7 1215.26  3734.4  1202.7
  3851.1 1195.22  3905.1 1193.16  4103.6 1186.92  4410.3 1181.51  4478.8 1180.82
  4587.1 1180.59  4690.4 1181.19  4789.3 1181.95    4873 1181.19  4950.5 1171.83
  4972.5 1160.98  4992.8 1157.89  4995.5 1157.39  4998.8 1157.89  5007.8 1158.53
  5119.3 1169.99  5135.2 1171.41  5301.7  1188.3  5365.1 1201.98  5538.2 1237.77
  5565.6 1239.65  5581.4 1248.86  5623.1 1257.94  5683.8 1267.31  5807.3 1269.32
#Mann= 17 ,-1 , 0
  3229.4      .1       0  3476.7     .16       0  3851.1      .1       0
  3905.1     .16       0  4103.6      .1       0  4410.3     .05       0
  4478.8      .1       0  4587.1     .05       0  4690.4      .1       0
  4789.3     .05       0    4873      .1       0  4992.8     .07       0
  4998.8      .1       0  5007.8     .05       0  5119.3     .16       0
  5365.1      .1       0  5623.1     .16       0
Bank Sta=4950.5,5135.2
XS Rating Curve= 0 ,0
Exp/Cntr=0.3,0.1

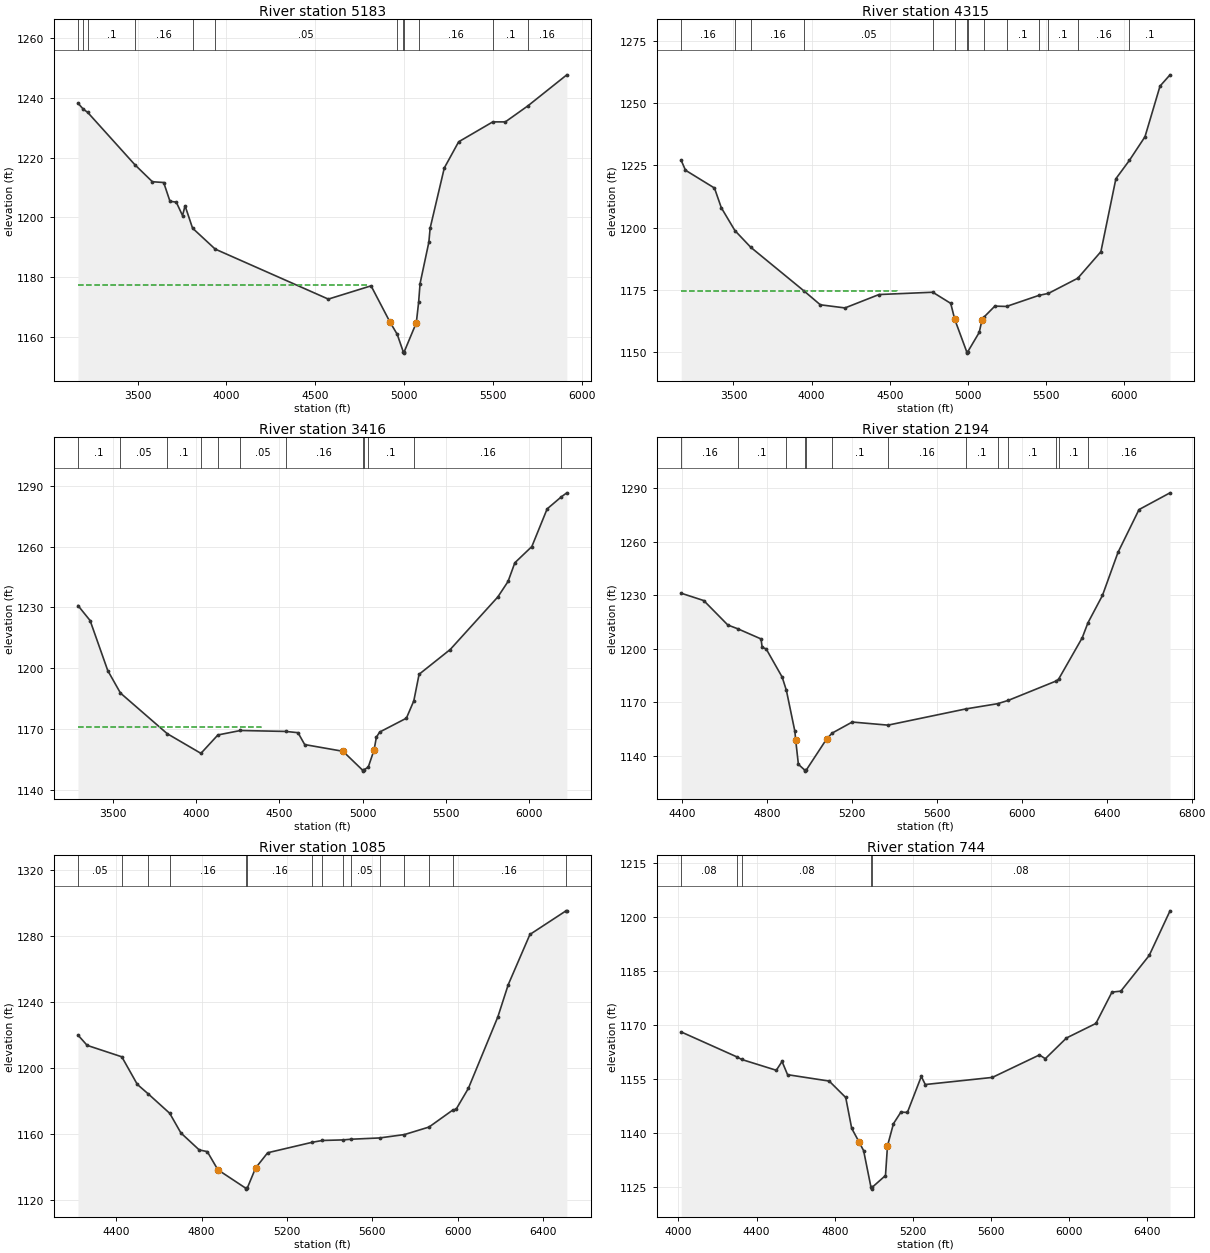
Type RM Length L Ch R = 1 ,5183    ,868,868,868
BEGIN DESCRIPTION:
MCCALL CREEK 8.0
END DESCRIPTION:
XS GIS Cut Line= 3
      2924935.37     10038892.59      2926346.84      10037470.7
      2926451.01     10036731.11
#Sta/Elev= 30
  3164.7 1238.27  3194.1  1236.3  3219.3 1235.19  3485.3 1217.61  3583.3 1211.94
  3646.9 1211.68  3682.3 1205.38  3717.6 1205.11    3753 1200.58  3767.1 1203.89
  3809.3 1196.38  3936.6 1189.36  4573.2 1172.59  4813.6 1177.04  4919.7 1164.94
  4960.8 1160.79  4994.5 1154.98  4997.2 1154.48  5000.5 1154.98  5068.2 1164.65
  5081.2 1171.46  5089.4  1177.8  5138.9  1191.7    5146 1196.37  5225.7 1216.56
  5306.5 1225.33  5498.6 1232.01  5569.1    1232  5696.1 1237.38  5915.1 1247.78
#Mann= 12 ,-1 , 0
  3164.7      .1       0  3194.1     .05       0  3219.3      .1       0
  3485.3     .16       0  3809.3      .1       0  3936.6     .05       0
  4960.8      .1       0  4994.5     .07       0  5000.5      .1       0
  5081.2     .16       0  5498.6      .1       0  5696.1     .16       0
#XS Ineff= 2 , 0
          4798.3  1177.4
Permanent Ineff=
       T       T
Bank Sta=4919.7,5068.2
XS Rating Curve= 0 ,0
Exp/Cntr=0.3,0.1

Type RM Length L Ch R = 1 ,4315    ,899,899,899
BEGIN DESCRIPTION:
MCCALL CREEK 7.0
END DESCRIPTION:
XS GIS Cut Line= 5
      2925346.82     10038840.51      2926289.55     10038330.08
      2926888.51     10038194.66      2927232.26     10037382.16
      2927736.09     10037138.04
#Sta/Elev= 30
  3165.3 1226.93  3192.8 1222.98  3378.3 1215.83    3422 1207.94  3509.1 1198.77
  3610.5 1192.07    3954 1174.41  4055.5    1169  4213.4 1167.74    4431 1173.11
  4775.2 1174.04  4890.1 1169.57  4916.1  1163.1  4992.7 1150.11  4995.5 1149.61
  4998.7 1150.11  5072.2 1157.89  5090.5 1162.94  5104.4 1164.16  5172.4 1168.46
  5247.1 1168.34  5454.9 1172.78  5515.2 1173.57  5703.5 1179.67  5851.1 1190.31
    5947 1219.57  6033.6 1226.95  6133.2 1236.41  6229.5 1256.74  6293.5 1261.25
#Mann= 14 ,-1 , 0
  3165.3     .16       0  3509.1      .1       0  3610.5     .16       0
    3954     .05       0  4775.2      .1       0  4916.1     .05       0
  4992.7    .035       0  4998.7     .05       0  5104.4     .16       0
  5247.1      .1       0  5454.9     .05       0  5515.2      .1       0
  5703.5     .16       0  6033.6      .1       0
#XS Ineff= 2 , 0
         4545.17 1174.52
Permanent Ineff=
       T       T
Bank Sta=4916.1,5090.5
XS Rating Curve= 0 ,0
Exp/Cntr=0.3,0.1

Type RM Length L Ch R = 1 ,3416    ,1222,1222,1222
BEGIN DESCRIPTION:
MCCALL CREEK 6.0
END DESCRIPTION:
XS GIS Cut Line= 4
      2926211.44     10039319.65      2927013.51     10038543.62
      2927982.26      10038590.5      2928814.22      10038418.9
#Sta/Elev= 30
    3290 1230.94  3362.8 1223.55  3468.8 1198.88  3545.2 1187.79  3825.9 1167.78
  4028.3 1158.08  4130.2 1167.15  4265.8 1169.35    4539 1168.88  4611.2 1168.27
  4651.3 1162.41  4881.6 1159.09  4998.7 1149.82  5001.4 1149.32  5004.7 1149.82
  5033.1 1151.31 5068.18 1159.82  5081.8 1166.06  5101.8 1168.59    5262 1175.41
  5306.6 1183.97  5338.3 1197.06  5525.2 1209.27  5811.1 1235.18  5872.4  1242.8
  5913.2 1252.02  6015.3 1260.02  6107.2 1278.58  6191.3 1284.45  6225.4  1286.5
#Mann= 12 ,-1 , 0
    3290      .1       0  3545.2     .05       0  3825.9      .1       0
  4028.3     .05       0  4130.2      .1       0  4265.8     .05       0
    4539     .16       0  4998.7     .07       0  5004.7     .16       0
  5033.1      .1       0  5306.6     .16       0  6191.3      .1       0
#XS Ineff= 2 , 0
         4390.06 1170.84
Permanent Ineff=
       T       T
Bank Sta=4881.6,5068.18
XS Rating Curve= 0 ,0
Exp/Cntr=0.3,0.1

Type RM Length L Ch R = 1 ,2194    ,1109,1109,1109
BEGIN DESCRIPTION:
MCCALL CREEK 5.0
END DESCRIPTION:
XS GIS Cut Line= 4
      2926565.62      10039538.4      2926997.89     10039366.54
      2927836.43     10039387.37       2928727.1     10038934.22
#Sta/Elev= 30
  4394.8 1231.16  4501.1 1227.05  4614.5 1213.34  4661.7 1211.21    4771 1205.53
  4776.4 1200.82  4795.3 1199.92  4870.6 1184.13  4890.5 1176.66  4930.6 1153.63
 4934.09 1149.06    4947 1135.21  4977.6  1131.9  4980.3  1131.4  4983.6  1131.9
  5080.6 1149.52  5106.4 1152.75  5200.7 1158.93  5369.1 1157.19  5736.2 1166.29
  5886.1 1169.22  5936.4 1171.09  6162.2 1181.97  6173.3 1183.01  6284.5 1206.19
  6311.2 1214.55  6379.6  1229.9  6452.8 1254.03    6552 1278.07  6698.1 1287.46
#Mann= 13 ,-1 , 0
  4394.8     .16       0  4661.7      .1       0  4890.5     .16       0
  4977.6     .07       0  4983.6     .16       0  5106.4      .1       0
  5369.1     .16       0  5736.2      .1       0  5886.1     .16       0
  5936.4      .1       0  6162.2     .05       0  6173.3      .1       0
  6311.2     .16       0
Bank Sta=4934.09,5080.6
XS Rating Curve= 0 ,0
Exp/Cntr=0.3,0.1

Type RM Length L Ch R = 1 ,1085    ,341,341,341
BEGIN DESCRIPTION:
MCCALL CREEK 4.0
END DESCRIPTION:
XS GIS Cut Line= 4
       2927148.9     10040418.63      2927701.01       10040278.
      2928310.39     10039673.83      2928789.56     10038955.06
#Sta/Elev= 30
  4220.1 1219.91  4263.1 1213.68  4425.5 1206.76  4498.2 1190.08  4550.6  1184.2
  4650.2 1172.58  4702.7 1160.69  4788.3 1150.45  4826.4  1149.4  4875.9 1138.43
  5007.3 1127.22    5010 1126.72  5013.3 1127.22  5052.7 1139.48  5109.3 1148.72
  5318.4 1155.06  5365.8 1156.15  5463.4  1156.5  5499.8  1156.9  5633.8 1157.68
  5750.8 1159.73  5865.7 1164.27  5976.3 1174.47  5993.3 1175.15  6050.4 1187.71
  6188.6 1230.97    6237 1250.35  6338.8 1280.77  6507.9 1295.05  6511.8 1295.06
#Mann= 15 ,-1 , 0
  4220.1     .05       0  4425.5     .16       0  4550.6      .1       0
  4650.2     .16       0  5007.3     .07       0  5013.3     .16       0
  5318.4      .1       0  5365.8     .05       0  5463.4      .1       0
  5499.8     .05       0  5633.8      .1       0  5750.8     .16       0
  5865.7     .05       0  5976.3     .16       0  6507.9      .1       0
Bank Sta=4875.9,5052.7
XS Rating Curve= 0 ,0
Exp/Cntr=0.3,0.1

Type RM Length L Ch R = 1 ,744     ,152,152,152
BEGIN DESCRIPTION:
MCCALL CREEK 3.0
END DESCRIPTION:
XS GIS Cut Line= 5
      2927096.87     10040876.94      2927810.39      10040465.5
      2928357.26     10040361.33      2928935.39     10040413.41
      2929430.17     10040632.16
#Sta/Elev= 30
  4014.3 1168.04  4299.6 1161.09  4324.3 1160.37    4501 1157.37  4530.5 1159.82
  4558.7 1156.14  4771.8 1154.36  4856.3 1149.79  4886.9  1141.2    4925 1137.37
    4948 1134.97  4985.7 1124.77  4988.4 1124.27  4991.7 1124.77  5059.9 1128.06
  5070.1 1136.32  5100.7  1142.5  5138.8 1145.73  5171.9 1145.62  5243.1 1155.64
  5263.5  1153.4  5606.7 1155.38  5847.7 1161.64  5877.8 1160.59  5986.1 1166.36
  6136.8 1170.41    6219 1179.14  6264.3  1179.4  6409.5 1189.34  6516.1 1201.77
#Mann= 5 ,-1 , 0
  4014.3     .08       0  4299.6     .05       0  4324.3     .08       0
  4985.7     .07       0  4991.7     .08       0
Bank Sta=4925,5070.1
XS Rating Curve= 0 ,0
Exp/Cntr=0.3,0.1

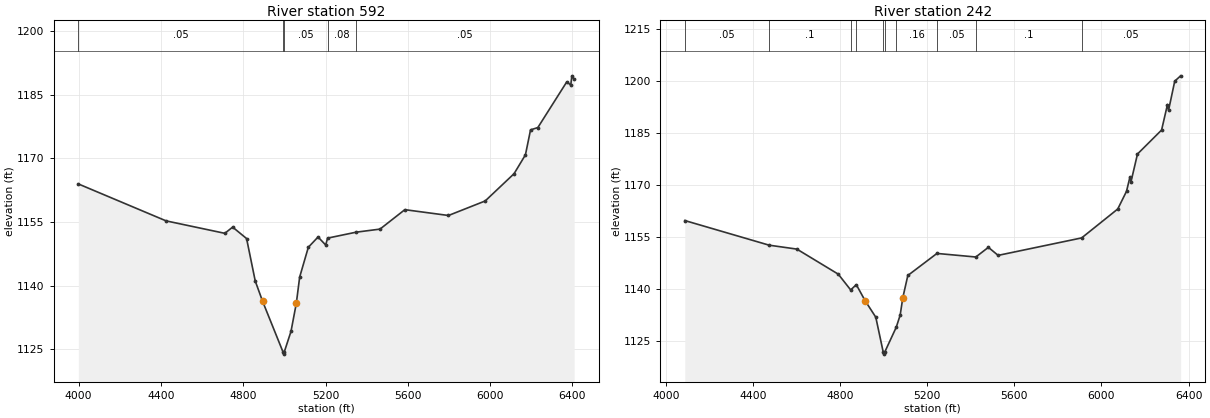
Type RM Length L Ch R = 1 ,592     ,350,350,350
BEGIN DESCRIPTION:
MCCALL CREEK 2.0
END DESCRIPTION:
XS GIS Cut Line= 5
       2927143.7     10040996.76      2927852.05     10040611.33
      2928289.55     10040507.16      2928878.09     10040574.87
      2929403.84     10040772.67
#Sta/Elev= 30
  3998.4 1163.98  4425.1 1155.28  4710.5 1152.35  4748.5 1153.81  4816.3 1151.12
  4858.4 1141.12  4893.7 1136.39  4993.4  1124.4  4996.2  1123.9  4999.4  1124.4
  5032.2 1129.25  5058.1 1135.88  5074.3 1142.04  5116.5 1149.07  5163.7 1151.48
  5200.8  1149.6  5210.2 1151.22  5349.1 1152.62  5464.8 1153.34  5585.6 1157.92
  5797.7 1156.55  5976.2 1159.97  6116.7  1166.4  6171.8 1170.83  6196.7 1176.71
  6232.2 1177.26  6372.7 1188.01  6392.2 1187.28  6397.6 1189.44  6408.7 1188.58
#Mann= 5 ,-1 , 0
  3998.4     .05       0  4993.4     .04       0  4999.4     .05       0
  5210.2     .08       0  5349.1     .05       0
Bank Sta=4893.7,5058.1
XS Rating Curve= 0 ,0
Exp/Cntr=0.3,0.1

Type RM Length L Ch R = 1 ,242     ,0,0,0
BEGIN DESCRIPTION:
MCCALL CREEK 1.0
END DESCRIPTION:
XS GIS Cut Line= 4
      2927273.95     10040996.74      2928003.09     10040981.12
       2928445.8     10040725.91      2929475.26      10040845.5
#Sta/Elev= 30
    4087 1159.79  4474.4 1152.68  4601.6 1151.55  4791.7 1144.32  4848.7 1139.77
  4874.5 1141.29  4914.9 1136.67    4964  1131.9  4998.4 1121.75  5001.1 1121.25
  5004.4 1121.75  5057.9    1129    5076 1132.52    5088 1137.51  5111.1 1143.94
  5244.8  1150.3  5423.3 1149.27    5481 1152.06  5525.7 1149.74  5909.3 1154.78
    6075 1163.12  6115.2 1168.22    6131 1172.34  6136.1 1171.05  6165.6 1178.98
  6276.3  1185.9  6303.3 1193.25  6308.3  1191.6  6336.7 1200.01  6363.7 1201.54
#Mann= 10 ,-1 , 0
    4087     .05       0  4474.4      .1       0  4848.7     .16       0
  4874.5      .1       0  4998.4     .07       0  5004.4      .1       0
  5057.9     .16       0  5244.8     .05       0  5423.3      .1       0
  5909.3     .05       0
Bank Sta=4914.9,5088
XS Rating Curve= 0 ,0
Exp/Cntr=0.3,0.1

Chan Stop Cuts=-1
Use User Specified Reach Order=0
Composite Channel Slope=5