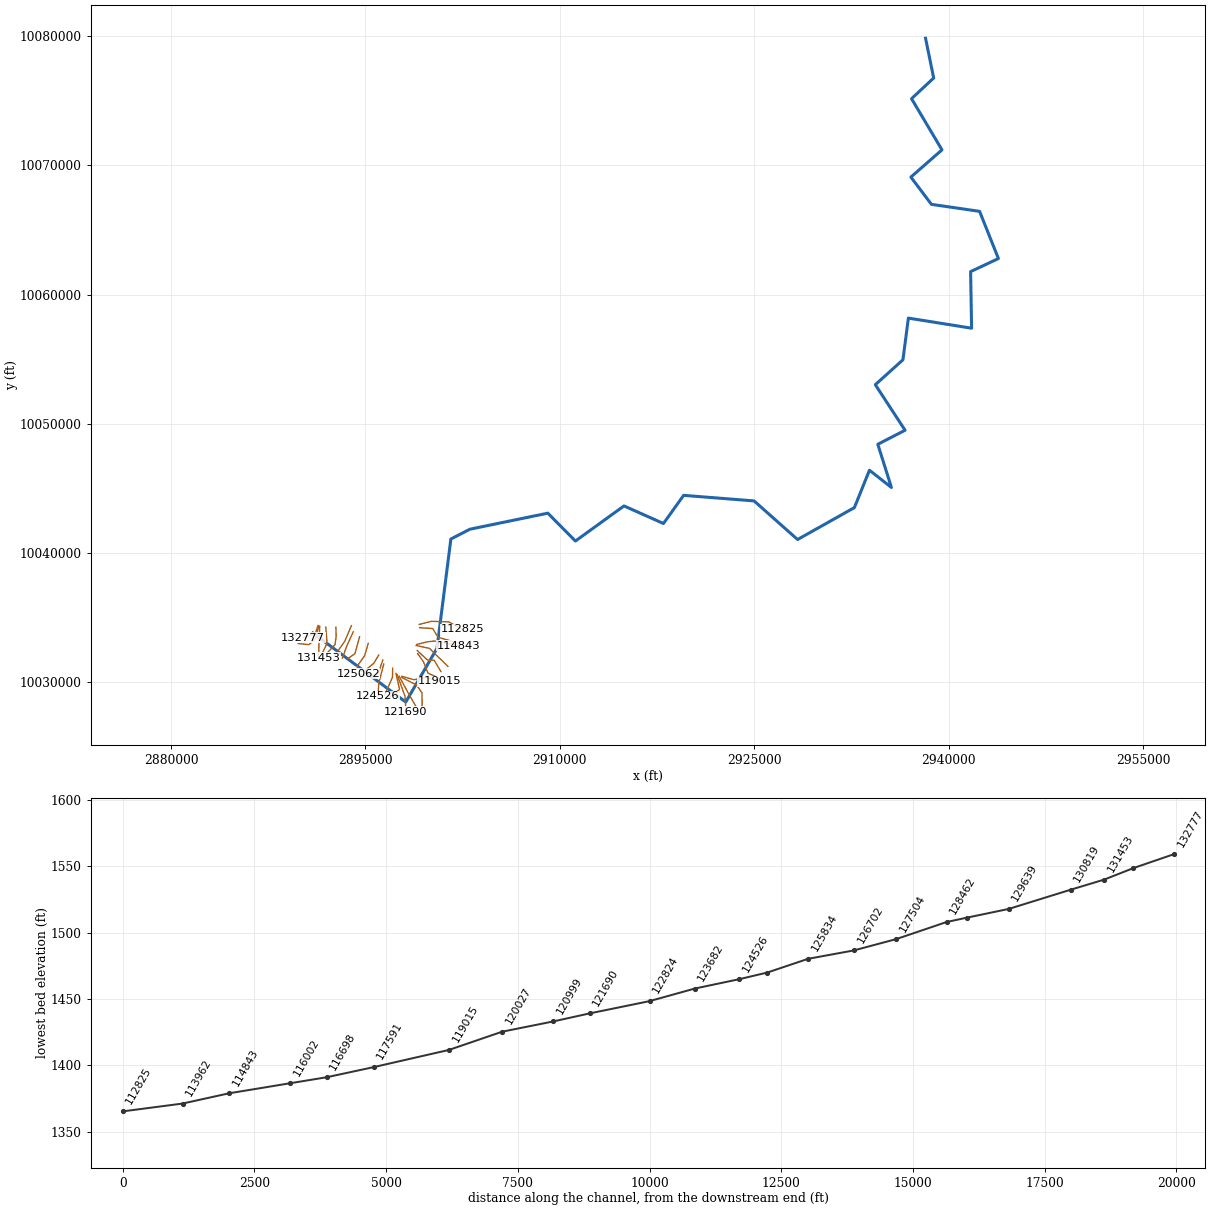
--- MILLER CREEK.prj (project) ---

Proj Title=MILLER CREEK Base Level Engineering
Current Plan=p01
Default Exp/Contr=0.3,0.1
English Units
Geom File=g01
Flow File=f01
Plan File=p01
Y Axis Title=Elevation
X Axis Title(PF)=Main Channel Distance
X Axis Title(XS)=Station
BEGIN DESCRIPTION:
MILLER CREEK
END DESCRIPTION:
DSS Export Rating Curves= 0
DSS Export Rating Curve Sorted= 0
DSS Export Volume Flow Curves= 0
DXF OffsetX= 0
DXF OffsetY= 0
DXF ScaleX= 1
DXF ScaleY= 10

--- MILLER CREEK.p01 (plan) ---

Plan Title=Multiple Run
Short Identifier=Multiple
Geom File=g01
Flow File=f01
Subcritical Flow
K Sum by GR= 0
Std Step Tol= 0.01
Critical Tol= 0.01
Num of Std Step Trials= 20
Max Error Tol= 0.3
Flow Tol Ratio= 0.001
Split Flow NTrial= 30
Split Flow Tol= 0.02
Split Flow Ratio= 0.02
Log Output Level= 0
Friction Slope Method= 1
Unsteady Friction Slope Method= 2
Unsteady Bridges Friction Slope Method= 1
Parabolic Critical Depth
Global Vel Dist=  1 , 1 , 1
Global Log Level= 0
CheckData=True
Encroach Param= -1, 0, 0, 0
BEGIN DESCRIPTION:
Multiple Run
END DESCRIPTION:

--- MILLER CREEK.f01 (steady flow) ---

Flow Title=Multiple
Program Version=4.10
Number of Profiles= 7
Profile Names=10-year,25-year,50-year,1pct_min,100-year,1pct_plu,500-year
River Rch & RM=MILLER CREEK,Reach-1         ,132777
     873    1265    1606    1495    2022    2734    3211
River Rch & RM=MILLER CREEK,Reach-1         ,131453
    1886    2828    3673    3484    4711    6372    7783
River Rch & RM=MILLER CREEK,Reach-1         ,124526
    2842    4338    5702    5465    7391    9996   12475
River Rch & RM=MILLER CREEK,Reach-1         ,119015
    3185    4879    6428    6174    8349   11291   14147
River Rch & RM=MILLER CREEK,Reach-1         ,116002
    3364    5158    6798    6530    8831   11943   14970
River Rch & RM=MILLER CREEK,Reach-1         ,112124
    3601    5532    7301    7022    9496   12843   16134
River Rch & RM=MILLER CREEK,Reach-1         ,110229
    3819    5873    7755    7461   10090   13646   17154
River Rch & RM=MILLER CREEK,Reach-1         ,106077
    3950    6076    8025    7721   10442   14122   17754
River Rch & RM=MILLER CREEK,Reach-1         ,103276
    5999    9357   12478   12107   16374   22144   28313
River Rch & RM=MILLER CREEK,Reach-1         ,98420
    6627   10354   13823   13424   18155   24552   31441
River Rch & RM=MILLER CREEK,Reach-1         ,91893
    6991   10925   14587   14165   19156   25907   33170
River Rch & RM=MILLER CREEK,Reach-1         ,87259
    7214   11270   15045   14604   19751   26711   34174
River Rch & RM=MILLER CREEK,Reach-1         ,86848
    7214   11270   15045   14604   19751   26711   34174
River Rch & RM=MILLER CREEK,Reach-1         ,80856
    7639   11937   15937   15470   20922   28294   36195
River Rch & RM=MILLER CREEK,Reach-1         ,76297
    7999   12517   16728   16253   21980   29725   38093
River Rch & RM=MILLER CREEK,Reach-1         ,75496
    7999   12517   16728   16253   21980   29725   38093
River Rch & RM=MILLER CREEK,Reach-1         ,73885
    8277   12950   17306   16812   22736   30748   39390
River Rch & RM=MILLER CREEK,Reach-1         ,72920
    8277   12950   17306   16812   22736   30748   39390
River Rch & RM=MILLER CREEK,Reach-1         ,68138
   10680   16801   22540   21970   29712   40183   51810
River Rch & RM=MILLER CREEK,Reach-1         ,60339
   10702   16815   22538   21948   29682   40141   51656
River Rch & RM=MILLER CREEK,Reach-1         ,56144
   12019   18911   25374   24730   33444   45229   58288
River Rch & RM=MILLER CREEK,Reach-1         ,47561
   12142   19102   25630   24978   33781   45684   58868
River Rch & RM=MILLER CREEK,Reach-1         ,45501
   12035   18902   25332   24656   33345   45095   57962
River Rch & RM=MILLER CREEK,Reach-1         ,39583
   12336   19365   25945   25244   34140   46170   59299
River Rch & RM=MILLER CREEK,Reach-1         ,32845
   13947   21953   29467   28721   38841   52528   67686
River Rch & RM=MILLER CREEK,Reach-1         ,30919
   13882   21825   29271   28505   38550   52135   67063
River Rch & RM=MILLER CREEK,Reach-1         ,26230
   13872   21791   29212   28431   38450   51999   66814
River Rch & RM=MILLER CREEK,Reach-1         ,21434
   14163   22237   29797   28988   39203   53017   68057
River Rch & RM=MILLER CREEK,Reach-1         ,14029
   14144   22185   29708   28881   39058   52821   67709
River Rch & RM=MILLER CREEK,Reach-1         ,8209
   14061   22026   29469   28621   38707   52347   66974
Boundary for River Rch & Prof#=MILLER CREEK,Reach-1         , 1
Up Type= 0
Dn Type= 3
Dn Slope=0.004
Boundary for River Rch & Prof#=MILLER CREEK,Reach-1         , 2
Up Type= 0
Dn Type= 3
Dn Slope=0.004
Boundary for River Rch & Prof#=MILLER CREEK,Reach-1         , 3
Up Type= 0
Dn Type= 3
Dn Slope=0.004
Boundary for River Rch & Prof#=MILLER CREEK,Reach-1         , 4
Up Type= 0
Dn Type= 3
Dn Slope=0.004
Boundary for River Rch & Prof#=MILLER CREEK,Reach-1         , 5
Up Type= 0
Dn Type= 3
Dn Slope=0.004
Boundary for River Rch & Prof#=MILLER CREEK,Reach-1         , 6
Up Type= 0
Dn Type= 3
Dn Slope=0.004
Boundary for River Rch & Prof#=MILLER CREEK,Reach-1         , 7
Up Type= 0
Dn Type= 3
Dn Slope=0.004
DSS Import GetInterval= 0
DSS Import GetPeak= 0
DSS Import FillOption= 0

--- MILLER CREEK.g01 (geometry) ---

Geom Title=Existing Conditions
Program Version=4.10

River Reach=MILLER CREEK    ,Reach-1
Reach XY= 30
      2890941.44       10033799.      2898111.01     10028449.19
       2900519.5     10032608.06      2901592.17     10041072.26
      2903060.35     10041830.62      2909073.26     10043073.23
      2911202.51     10040916.15      2914950.61     10043633.79
      2917997.67     10042273.67       2919553.9     10044453.42
      2924989.21     10044022.88      2928348.47     10041033.73
      2932732.89     10043504.42      2933895.92     10046398.06
      2935589.49     10045062.29      2934540.52     10048407.88
       2936644.3     10049493.62      2934348.07     10053020.74
      2936478.25     10054949.31      2936898.66     10058178.27
       2941777.3     10057394.94      2941701.34     10061776.76
      2943847.86     10062787.63      2942394.19     10066443.73
      2938678.47     10066983.73      2937091.31     10069094.91
      2939491.12     10071203.82      2937142.55     10075164.65
      2938851.14      10076767.8      2938223.41     10079845.45

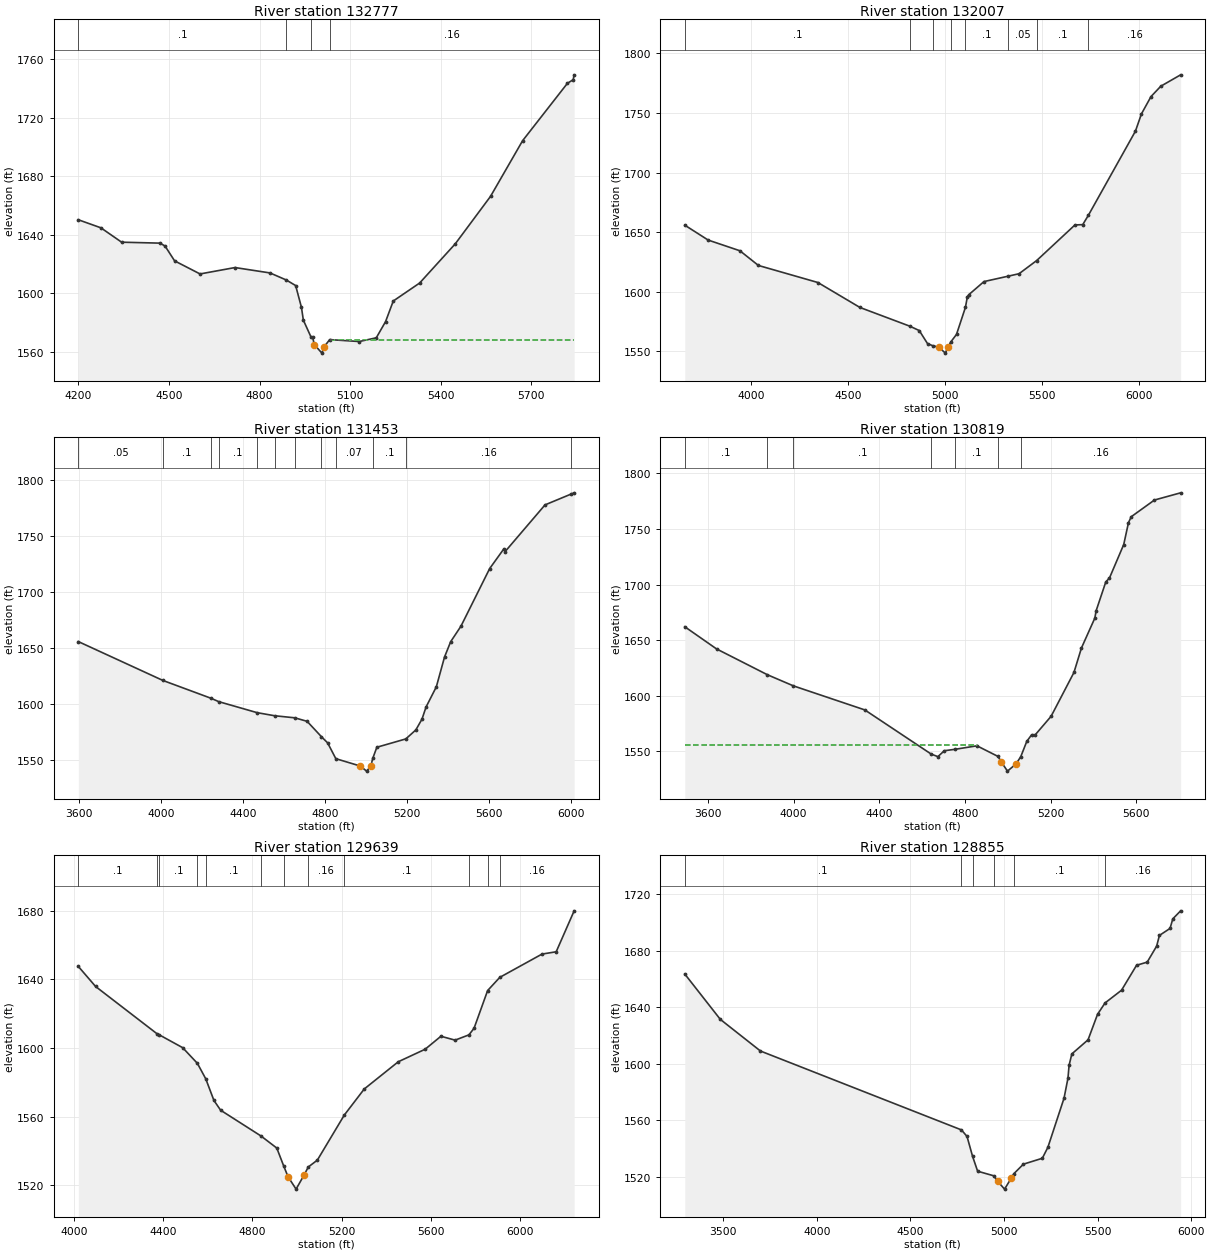
Type RM Length L Ch R = 1 ,132777  ,770,770,770
BEGIN DESCRIPTION:
MILLER CREEK 229.0
END DESCRIPTION:
XS GIS Cut Line= 3
      2891337.96     10034376.44      2891134.84     10033761.86
      2890197.59     10033428.62
#Sta/Elev= 30
  4199.8  1650.2  4274.5  1644.7  4343.2 1634.87  4470.1 1634.23    4487 1632.24
  4518.6 1622.11  4602.9 1613.17  4718.7 1617.54  4834.6 1613.86  4888.6 1609.02
  4919.5 1605.23  4938.7 1590.32    4945 1581.58  4970.5 1569.99  4975.9 1569.75
  4981.2 1564.91  5006.4 1559.05    5013 1563.19  5032.2 1568.29  5130.1 1566.98
  5186.5 1569.52  5217.3 1580.61  5242.8 1594.68  5330.1 1606.96  5448.1 1633.76
  5564.9 1666.21  5671.1 1704.25  5819.6 1743.49  5838.5 1745.91  5841.8 1749.26
#Mann= 4 ,-1 , 0
  4199.8      .1       0  4888.6     .16       0  4970.5     .07       0
  5032.2     .16       0
#XS Ineff= 2 , 0
                         5031.96         1568.32
Permanent Ineff=
       T       T
Bank Sta=4981.2,5013
XS Rating Curve= 0 ,0
Exp/Cntr=0.3,0.1

Type RM Length L Ch R = 1 ,132007  ,554,554,554
BEGIN DESCRIPTION:
MILLER CREEK 228.0
END DESCRIPTION:
XS GIS Cut Line= 4
      2891390.04     10034350.38      2891150.46     10033334.78
      2890634.84     10032892.07      2889806.74     10032980.61
#Sta/Elev= 30
  3657.6 1655.85    3778 1643.36  3941.8 1634.38  4037.1 1622.07  4343.6 1607.78
  4560.4 1586.86  4818.6 1571.09  4866.2 1567.49    4909 1556.51  4937.5 1554.67
    4966 1553.71  5000.9 1548.57  5015.4  1554.1  5029.7 1558.15  5058.2 1564.27
  5104.1 1586.89  5114.2 1595.81  5121.9 1597.62  5199.8 1608.56  5325.9 1613.13
  5380.7 1615.15  5471.4 1626.18  5668.7 1656.03  5708.9  1656.3  5737.7 1664.05
  5980.5 1734.65  6011.7 1749.21  6060.9 1763.69  6111.2 1772.34  6213.5  1781.9
#Mann= 8 ,-1 , 0
  3657.6      .1       0  4818.6     .16       0  4937.5     .07       0
  5029.7     .16       0  5104.1      .1       0  5325.9     .05       0
  5471.4      .1       0  5737.7     .16       0
Bank Sta=4966,5015.4
XS Rating Curve= 0 ,0
Exp/Cntr=0.3,0.1

Type RM Length L Ch R = 1 ,131453  ,634,634,634
BEGIN DESCRIPTION:
MILLER CREEK 226.0
END DESCRIPTION:
XS GIS Cut Line= 3
      2891473.38     10034298.32      2891421.29     10033308.74
      2891384.84     10031881.66
#Sta/Elev= 30
  3596.1 1655.53  4008.6 1620.84    4244 1604.89  4281.2 1601.91    4468  1592.1
  4553.3 1589.35  4652.1 1587.49  4712.1 1584.35  4782.1 1570.59  4812.1 1565.13
  4852.1 1551.02  4972.2 1544.41  5001.9 1539.91  5022.2 1544.05  5032.2 1551.28
  5052.2 1561.22  5193.3 1568.64  5242.3 1576.67  5272.3 1586.28  5292.3 1597.18
  5342.3 1615.14  5382.3 1641.76  5412.3 1655.44  5462.3 1669.23  5602.4 1720.67
  5672.1  1738.4  5677.1  1735.7  5872.5 1777.54  5999.9 1787.21  6014.6  1788.3
#Mann= 12 ,-1 , 0
  3596.1     .05       0  4008.6      .1       0    4244     .05       0
  4281.2      .1       0    4468     .05       0  4553.3      .1       0
  4652.1     .05       0  4782.1      .1       0  4852.1     .07       0
  5032.2      .1       0  5193.3     .16       0  5999.9      .1       0
Bank Sta=4972.2,5022.2
XS Rating Curve= 0 ,0
Exp/Cntr=0.3,0.1

Type RM Length L Ch R = 1 ,130819  ,1180,1180,1180
BEGIN DESCRIPTION:
MILLER CREEK 225.0
END DESCRIPTION:
XS GIS Cut Line= 3
      2891936.92      10034251.4      2892041.09     10033006.66
      2891583.09     10032043.83
#Sta/Elev= 30
  3492.3 1662.07  3640.5 1642.16  3878.3 1618.92  3999.7 1608.92  4332.9 1587.33
  4643.2  1547.6  4674.1 1545.35  4704.2 1550.64  4754.7 1551.95  4856.6 1555.07
    4955 1545.51  4970.1  1540.6  4999.1 1532.32  5038.3 1538.65    5061 1545.24
  5089.3 1559.11    5112    1565  5129.1 1565.05  5202.8  1581.6  5309.4 1620.96
  5344.6 1643.04  5407.2 1669.94  5412.8 1676.31  5458.2 1702.36  5475.4 1705.93
  5541.9 1735.94  5564.1 1755.65  5577.3 1760.99  5685.3 1775.95  5807.6 1782.43
#Mann= 7 ,-1 , 0
  3492.3      .1       0  3878.3     .05       0  3999.7      .1       0
  4643.2     .05       0  4754.7      .1       0    4955     .07       0
    5061     .16       0
#XS Ineff= 2 , 0
         4856.25 1555.57
Permanent Ineff=
       T       T
Bank Sta=4970.1,5038.3
XS Rating Curve= 0 ,0
Exp/Cntr=0.3,0.1

Type RM Length L Ch R = 1 ,129639  ,784,784,784
BEGIN DESCRIPTION:
MILLER CREEK 223.0
END DESCRIPTION:
XS GIS Cut Line= 4
      2892718.17     10034240.99        2892739.     10033537.91
      2892655.67     10032902.49      2892056.69     10032261.84
#Sta/Elev= 30
  4019.8 1647.45  4097.1 1635.79  4373.4 1608.15  4382.5 1607.62  4487.3 1600.15
  4553.2 1591.03  4590.7 1582.01  4627.3 1569.42  4657.3 1563.74    4838 1548.75
  4908.9 1541.71  4939.2 1531.49  4959.4 1524.98  4995.3  1517.8    5030 1525.74
  5050.1  1530.7  5090.5 1534.67  5211.5 1560.95  5300.7  1576.1  5453.2 1591.96
  5573.4 1599.24  5644.2  1606.8  5707.7 1604.54  5769.7 1607.61  5792.7 1611.47
  5853.4  1633.4  5907.9 1641.09  6097.1 1654.65  6160.6 1655.99  6241.1 1679.83
#Mann= 12 ,-1 , 0
  4019.8      .1       0  4373.4     .05       0  4382.5      .1       0
  4553.2     .05       0  4590.7      .1       0    4838     .16       0
  4939.2     .07       0  5050.1     .16       0  5211.5      .1       0
  5769.7     .16       0  5853.4      .1       0  5907.9     .16       0
Bank Sta=4959.4,5030
XS Rating Curve= 0 ,0
Exp/Cntr=0.3,0.1

Type RM Length L Ch R = 1 ,128855  ,393,393,393
BEGIN DESCRIPTION:
MILLER CREEK 221.0
END DESCRIPTION:
XS GIS Cut Line= 3
      2893916.08     10034366.02      2893405.67      10033157.7
      2892640.04     10032063.94
#Sta/Elev= 30
  3295.2 1663.65  3484.7 1631.55  3699.3 1609.11  4772.1 1553.25  4801.8 1548.62
  4831.4 1534.52  4858.4 1524.01  4944.7 1520.75  4965.7 1516.81  5002.1 1511.32
    5039 1519.32    5052 1522.28  5102.6 1528.99  5203.7 1533.17  5233.3 1540.89
  5319.7 1575.74  5340.6 1589.89  5346.7 1599.14  5361.5  1607.1  5447.8 1617.06
  5498.4  1635.1  5538.6 1643.18  5626.6 1652.19  5706.8 1669.86  5763.5 1672.07
    5814 1683.41  5828.8    1691  5885.5 1695.95  5900.3 1702.74    5942 1708.41
#Mann= 6 ,-1 , 0
  3295.2      .1       0  4772.1     .05       0  4831.4      .1       0
  4944.7     .07       0    5052      .1       0  5538.6     .16       0
Bank Sta=4965.7,5039
XS Rating Curve= 0 ,0
Exp/Cntr=0.3,0.1

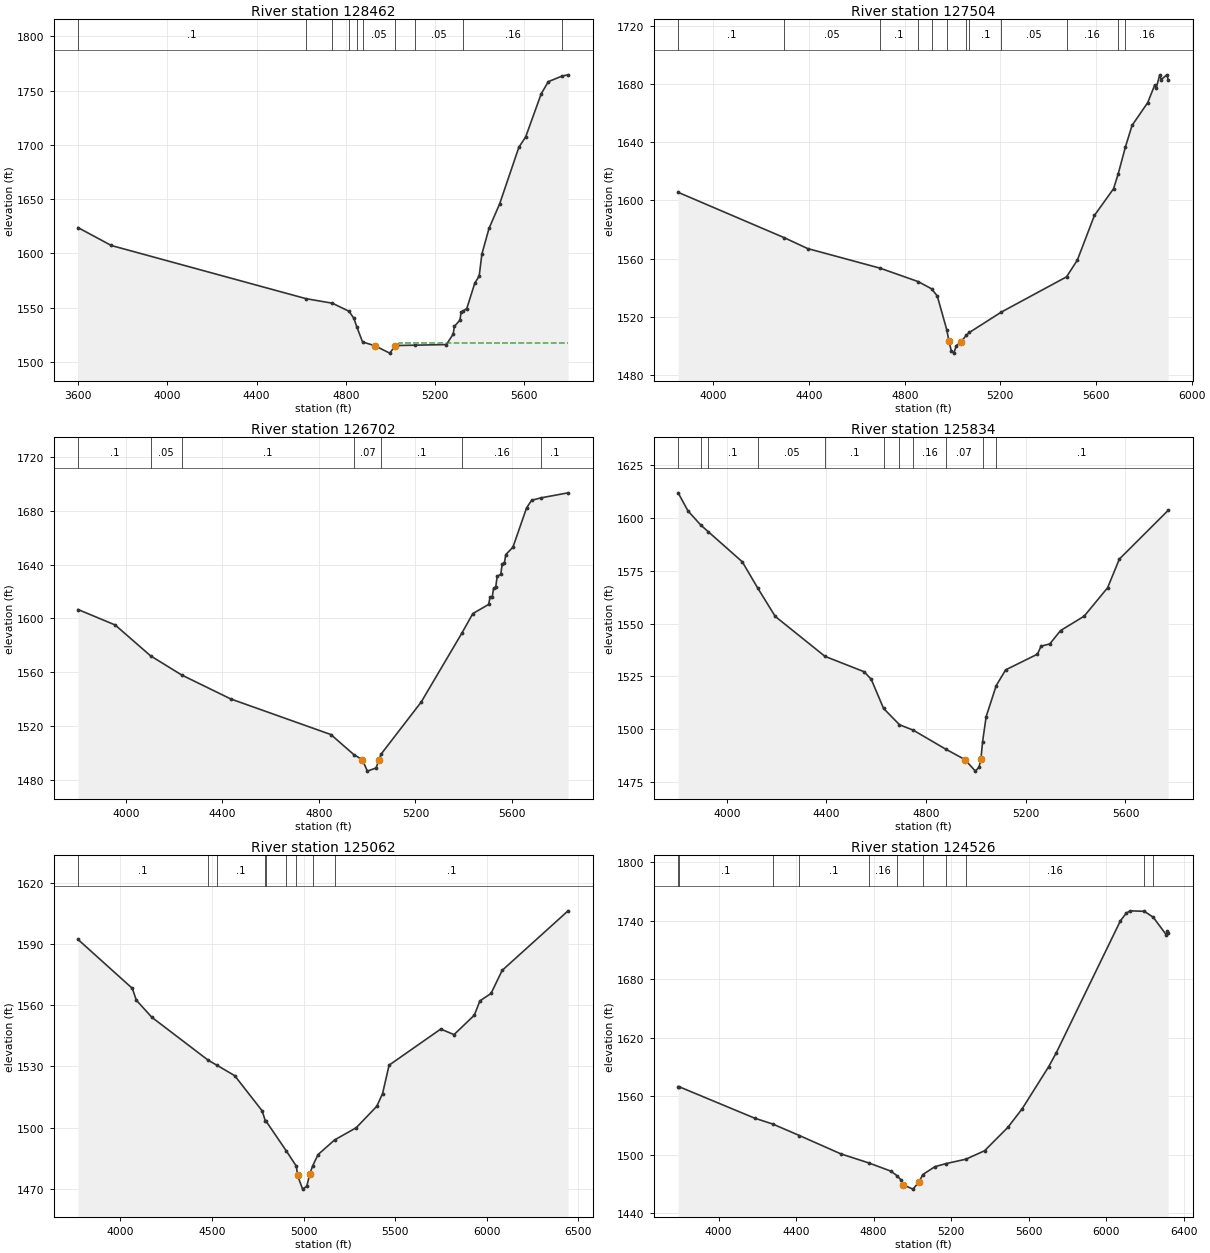
Type RM Length L Ch R = 1 ,128462  ,958,958,958
BEGIN DESCRIPTION:
MILLER CREEK 220.0
END DESCRIPTION:
XS GIS Cut Line= 3
      2894056.69     10033881.62      2893561.92     10032793.11
      2893218.17     10031850.41
#Sta/Elev= 30
  3598.6 1623.73    3748 1607.24  4622.1 1558.18    4740 1554.01  4814.3 1546.59
  4836.2 1540.18  4850.2 1531.89  4875.4 1518.27  4931.2 1514.75  4997.4 1507.97
  5022.9 1514.96  5111.7 1515.32  5251.3 1515.84    5282 1525.48  5287.3 1532.62
  5312.5  1538.4  5317.8 1545.78  5326.2 1546.66  5343.1 1549.08    5379 1572.46
  5398.9  1579.2    5411 1599.43  5442.9 1622.98  5490.6 1645.62  5576.9 1697.86
  5607.5 1707.43  5677.1 1747.12    5709 1758.33  5770.9 1763.55  5797.7 1764.65
#Mann= 10 ,-1 , 0
  3598.6      .1       0  4622.1     .05       0    4740      .1       0
  4814.3     .05       0  4850.2    .035       0  4875.4     .05       0
  5022.9      .1       0  5111.7     .05       0  5326.2     .16       0
  5770.9      .1       0
#XS Ineff= 2 , 0
                         5038.26         1517.18
Permanent Ineff=
       T       T
Bank Sta=4931.2,5022.9
XS Rating Curve= 0 ,0
Exp/Cntr=0.3,0.1

Type RM Length L Ch R = 1 ,127504  ,802,802,802
BEGIN DESCRIPTION:
MILLER CREEK 218.0
END DESCRIPTION:
XS GIS Cut Line= 3
      2894546.29     10033506.63      2894192.13     10032199.36
      2893624.72     10031798.53
#Sta/Elev= 30
  3852.6 1605.61    4297 1574.38    4394 1566.97  4697.6 1553.45  4856.3 1544.25
  4912.4 1539.29  4936.2 1534.38  4976.1 1511.02  4984.9 1503.45  4995.3 1496.34
  5005.3 1495.08    5016 1500.14  5036.7 1503.05  5057.4 1507.33  5070.4 1509.28
  5203.9 1523.27  5476.7 1547.51  5521.9 1558.99  5593.3  1589.7  5673.3 1608.08
  5692.4 1618.03  5723.3    1637  5750.8 1651.62  5816.1 1667.24  5845.7 1679.42
  5851.8 1677.41  5866.6 1686.33  5872.7  1683.1  5896.2 1686.37  5901.7 1683.08
#Mann= 12 ,-1 , 0
  3852.6      .1       0    4297     .05       0  4697.6      .1       0
  4856.3     .05       0  4912.4     .16       0  4976.1     .07       0
  5057.4     .16       0  5070.4      .1       0  5203.9     .05       0
  5476.7     .16       0  5692.4      .1       0  5723.3     .16       0
Bank Sta=4984.9,5036.7
XS Rating Curve= 0 ,0
Exp/Cntr=0.3,0.1

Type RM Length L Ch R = 1 ,126702  ,868,868,868
BEGIN DESCRIPTION:
MILLER CREEK 216.0
END DESCRIPTION:
XS GIS Cut Line= 3
      2895218.17     10033001.44      2894936.92     10032037.91
      2894343.29     10031199.53
#Sta/Elev= 30
  3801.7  1606.6  3955.6 1595.11  4102.2 1572.22  4230.9 1558.01  4434.8 1540.17
  4849.7 1513.74  4944.5  1498.9  4980.2 1495.01  5000.9 1486.58  5036.8 1488.93
  5048.3 1494.74  5057.7  1499.2  5223.9 1537.88  5393.1 1589.23    5438 1603.61
  5503.2 1610.34  5509.4 1615.67    5518 1615.58  5524.1 1622.48  5532.8 1623.26
  5538.9 1631.12  5553.7  1632.8  5559.8 1640.28  5568.5 1640.89  5574.6 1647.38
  5604.2 1652.91  5660.7 1682.04  5681.6 1687.72  5720.7 1689.53  5832.7 1693.25
#Mann= 7 ,-1 , 0
  3801.7      .1       0  4102.2     .05       0  4230.9      .1       0
  4944.5     .07       0  5057.7      .1       0  5393.1     .16       0
  5720.7      .1       0
Bank Sta=4980.2,5048.3
XS Rating Curve= 0 ,0
Exp/Cntr=0.3,0.1

Type RM Length L Ch R = 1 ,125834  ,772,772,772
BEGIN DESCRIPTION:
MILLER CREEK 214.0
END DESCRIPTION:
XS GIS Cut Line= 4
      2896025.47     10032090.01      2895645.25     10031454.57
      2894962.96     10030892.07      2894624.46      10030845.2
#Sta/Elev= 30
  3804.7 1611.76  3844.4 1603.21  3895.1 1596.59    3925 1593.46  4062.2 1579.17
    4124 1566.79  4194.4 1553.37    4394  1534.5    4551 1527.24  4579.6 1523.67
  4629.1  1509.9    4693 1502.19    4749 1499.58    4878 1490.69  4955.8 1485.72
  4997.6 1480.27  5012.2 1482.16    5020 1486.19  5026.5 1494.18  5040.9 1506.06
  5081.3  1520.7    5119 1528.11  5246.7 1535.54  5261.1 1539.32  5296.2 1540.37
  5339.3 1546.67  5434.3 1553.51  5528.3 1566.93  5575.3 1580.46  5771.2 1603.48
#Mann= 11 ,-1 , 0
  3804.7      .1       0  3895.1     .05       0    3925      .1       0
    4124     .05       0    4394      .1       0  4629.1     .05       0
    4693      .1       0    4749     .16       0    4878     .07       0
  5026.5     .16       0  5081.3      .1       0
Bank Sta=4955.8,5020
XS Rating Curve= 0 ,0
Exp/Cntr=0.3,0.1

Type RM Length L Ch R = 1 ,125062  ,536,536,536
BEGIN DESCRIPTION:
MILLER CREEK 212.0
END DESCRIPTION:
XS GIS Cut Line= 4
      2896343.17     10031704.57      2896009.84     10030735.82
      2895457.75     10030464.99       2894432.6     10030626.31
#Sta/Elev= 30
  3768.1 1592.15  4065.1 1568.19  4086.2 1562.46  4171.4 1554.07  4480.2 1532.99
  4527.7 1530.57    4624  1525.5  4773.7 1508.32  4791.6 1503.29  4794.9 1503.29
  4905.5 1488.73  4961.2 1481.13  4967.2 1476.66    4995 1469.96  5017.7 1471.37
  5034.7 1477.57  5050.3 1481.41  5079.7  1486.9  5169.6 1494.03  5287.6    1500
  5400.1 1510.49  5431.9 1516.75  5467.5 1530.64  5749.6 1548.31  5822.3 1545.59
  5933.2 1555.11  5963.6  1562.1  6024.3 1565.72  6085.1 1577.02  6445.3 1606.18
#Mann= 9 ,-1 , 0
  3768.1      .1       0  4480.2     .05       0  4527.7      .1       0
  4791.6     .05       0  4794.9      .1       0  4905.5     .16       0
  4961.2     .07       0  5050.3     .16       0  5169.6      .1       0
Bank Sta=4967.2,5034.7
XS Rating Curve= 0 ,0
Exp/Cntr=0.3,0.1

Type RM Length L Ch R = 1 ,124526  ,844,844,844
BEGIN DESCRIPTION:
MILLER CREEK 211.0
END DESCRIPTION:
XS GIS Cut Line= 3
      2896410.89      10031386.9      2896030.67     10029918.11
      2895962.99     10028908.18
#Sta/Elev= 30
  3790.7 1569.89  3796.3 1569.79  4186.5 1537.57    4278 1531.69  4416.9 1519.81
  4630.7 1501.03  4774.1 1491.81  4888.9 1483.34  4919.9 1478.76  4941.7  1474.2
  4950.9 1469.52  5002.3 1464.91  5033.5 1471.94  5053.2 1479.81  5116.2  1487.9
  5173.1 1491.05  5275.9 1495.58  5372.4 1504.22  5492.7  1528.2  5566.5 1547.22
  5703.2  1590.3  5743.3 1604.89    6074 1739.96  6104.1 1747.72  6124.1 1750.06
    6197 1749.56  6243.2  1743.5  6311.3 1725.26  6316.3 1729.46  6320.1 1726.86
#Mann= 11 ,-1 , 0
  3790.7     .05       0  3796.3      .1       0    4278     .05       0
  4416.9      .1       0  4774.1     .16       0  4919.9     .07       0
  5053.2     .16       0  5173.1      .1       0  5275.9     .16       0
    6197      .1       0  6243.2     .16       0
Bank Sta=4950.9,5033.5
XS Rating Curve= 0 ,0
Exp/Cntr=0.3,0.1

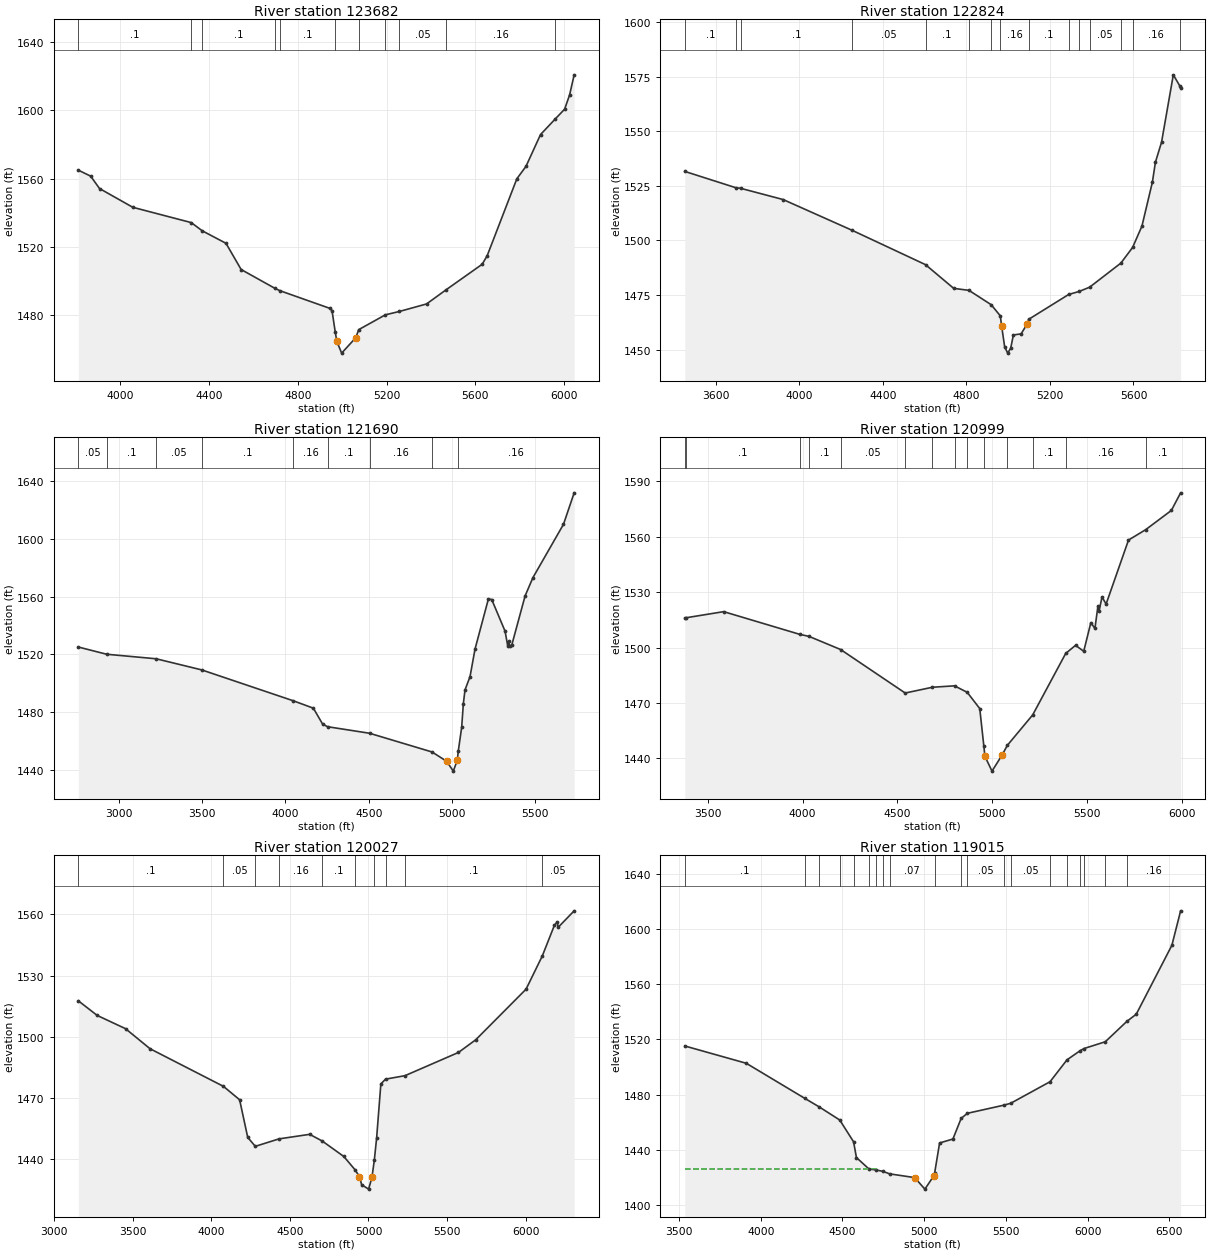
Type RM Length L Ch R = 1 ,123682  ,858,858,858
BEGIN DESCRIPTION:
MILLER CREEK 209.0
END DESCRIPTION:
XS GIS Cut Line= 3
      2897098.38     10031069.19      2897087.96     10030371.24
      2896468.17     10028964.99
#Sta/Elev= 30
  3810.9 1564.97  3866.4 1561.47  3906.4 1554.22  4056.4 1543.23  4319.7 1534.28
  4369.9 1529.43  4476.4 1522.16  4544.7 1506.81  4697.3 1495.77  4719.9 1494.39
  4945.2 1484.04  4954.3 1482.81  4968.5 1470.49  4976.1 1464.73  4997.7 1457.86
  5061.8 1466.95  5074.5  1471.6  5194.8 1480.28  5257.9 1482.25  5380.5 1486.65
  5468.9 1494.98  5631.1 1509.88  5653.7  1514.9  5787.4 1559.93  5828.5 1567.18
  5894.1 1585.81  5961.5 1595.09  6002.8 1600.68  6025.2 1609.05  6045.7 1620.78
#Mann= 11 ,-1 , 0
  3810.9      .1       0  4319.7     .05       0  4369.9      .1       0
  4697.3     .05       0  4719.9      .1       0  4968.5     .07       0
  5074.5      .1       0  5194.8     .16       0  5257.9     .05       0
  5468.9     .16       0  5961.5      .1       0
Bank Sta=4976.1,5061.8
XS Rating Curve= 0 ,0
Exp/Cntr=0.3,0.1

Type RM Length L Ch R = 1 ,122824  ,1134,1134,1134
BEGIN DESCRIPTION:
MILLER CREEK 207.0
END DESCRIPTION:
XS GIS Cut Line= 3
       2897353.6     10030662.86      2897634.84     10029428.53
       2896745.3     10028767.88
#Sta/Elev= 30
  3451.7 1531.64  3696.8 1524.15    3719 1523.91  3922.6 1518.75  4254.3  1504.6
  4604.2 1488.93  4739.2 1478.07  4812.3 1477.15  4918.6 1470.59  4962.3 1465.48
  4968.7  1460.8  4983.3 1451.23  4997.7  1448.4  5012.1 1450.65    5025 1456.73
  5061.9 1457.21  5089.7 1461.57  5098.1 1463.88    5290 1475.29    5340 1476.65
  5390.1 1478.61  5539.6 1489.64  5595.7  1496.8  5640.5  1506.6  5690.5 1526.73
  5705.1 1535.89  5734.4 1545.04  5790.7 1575.89  5823.3 1570.56  5825.7 1569.79
#Mann= 15 ,-1 , 0
  3451.7      .1       0  3696.8     .05       0    3719      .1       0
  4254.3     .05       0  4604.2      .1       0  4812.3     .16       0
  4918.6     .07       0  4962.3     .16       0  5098.1      .1       0
    5290     .05       0    5340      .1       0  5390.1     .05       0
  5539.6      .1       0  5595.7     .16       0  5823.3      .1       0
Bank Sta=4968.7,5089.7
XS Rating Curve= 0 ,0
Exp/Cntr=0.3,0.1

Type RM Length L Ch R = 1 ,121690  ,691,691,691
BEGIN DESCRIPTION:
MILLER CREEK 205.0
END DESCRIPTION:
XS GIS Cut Line= 3
      2897447.33     10030579.58       2898051.5     10028897.28
      2898129.63     10027709.74
#Sta/Elev= 30
  2756.3 1525.06  2926.2 1520.07  3224.1 1516.92  3497.4 1509.23  4047.8 1487.83
  4167.7 1482.74  4223.8 1471.64  4253.8  1469.9  4505.1 1465.39  4880.7 1452.42
  4968.3 1445.99  5008.1 1439.18    5032 1446.69  5038.4 1453.32  5058.5 1469.57
  5068.5 1485.96  5078.5 1495.39  5108.6 1504.59  5138.6 1523.67  5218.8 1558.29
  5238.8 1557.95    5319 1536.03  5334.7 1526.05  5339.7  1528.9  5349.1 1525.43
  5359.1 1526.36  5439.3 1560.44    5486 1573.03  5669.8 1609.99  5733.9 1631.77
#Mann= 9 ,-1 , 0
  2756.3     .05       0  2926.2      .1       0  3224.1     .05       0
  3497.4      .1       0  4047.8     .16       0  4253.8      .1       0
  4505.1     .16       0  4880.7     .07       0  5038.4     .16       0
Bank Sta=4968.3,5032
XS Rating Curve= 0 ,0
Exp/Cntr=0.3,0.1

Type RM Length L Ch R = 1 ,120999  ,972,972,972
BEGIN DESCRIPTION:
MILLER CREEK 203.0
END DESCRIPTION:
XS GIS Cut Line= 3
      2897603.59     10030444.14      2898280.67     10029183.74
      2898868.91     10028158.22
#Sta/Elev= 30
  3379.6 1516.09  3385.6 1516.15  3584.4 1519.47  3985.5 1507.18  4034.5 1506.07
  4200.9 1498.96  4541.1 1475.41  4684.8 1478.55    4801  1479.3    4868 1475.79
    4934    1467  4955.6 1446.67  4961.3 1441.15  4998.5 1433.13  5051.9 1441.85
  5079.3 1447.08    5213 1463.57  5386.8 1496.82  5438.8 1501.23    5482 1498.02
  5519.4  1513.5    5541 1510.38  5556.8 1522.46  5562.5 1519.56  5578.3 1527.44
  5599.9 1523.58  5717.9 1558.22  5808.5 1563.86  5943.7 1574.26  5992.6  1583.8
#Mann= 14 ,-1 , 0
  3379.6     .05       0  3385.6      .1       0  3985.5     .05       0
  4034.5      .1       0  4200.9     .05       0  4541.1      .1       0
  4684.8     .16       0    4801      .1       0    4868     .16       0
  4955.6     .07       0  5079.3     .16       0    5213      .1       0
  5386.8     .16       0  5808.5      .1       0
Bank Sta=4961.3,5051.9
XS Rating Curve= 0 ,0
Exp/Cntr=0.3,0.1

Type RM Length L Ch R = 1 ,120027  ,1012,1012,1012
BEGIN DESCRIPTION:
MILLER CREEK 200.0
END DESCRIPTION:
XS GIS Cut Line= 4
      2897811.95     10030350.39      2898947.34     10029761.86
        2899364.     10029162.91      2899374.41     10028017.93
#Sta/Elev= 30
  3154.6 1517.66  3274.6  1510.5  3454.8 1504.01  3610.7 1494.18  4077.2 1475.76
  4180.4 1469.17    4232 1450.73  4280.1 1446.35  4431.2 1450.01  4626.1 1452.23
  4706.1 1448.94  4843.1 1441.38  4914.7 1434.84  4942.8 1431.48  4956.5 1427.54
  5000.8 1425.38    5022 1431.15  5036.9 1439.42  5051.7 1450.36  5078.7 1476.93
  5108.4 1479.27  5232.3 1480.98  5572.3 1492.36  5682.3 1498.58  6002.3 1523.38
  6105.5 1539.65  6182.3 1554.63  6200.7 1556.36  6205.7 1553.62  6308.1 1561.76
#Mann= 10 ,-1 , 0
  3154.6      .1       0  4077.2     .05       0  4280.1      .1       0
  4431.2     .16       0  4706.1      .1       0  4914.7     .07       0
  5036.9      .1       0  5108.4     .16       0  5232.3      .1       0
  6105.5     .05       0
Bank Sta=4942.8,5022
XS Rating Curve= 0 ,0
Exp/Cntr=0.3,0.1

Type RM Length L Ch R = 1 ,119015  ,1424,1424,1424
BEGIN DESCRIPTION:
MILLER CREEK 198.0
END DESCRIPTION:
XS GIS Cut Line= 4
      2897806.72     10030444.15      2898744.21     10030178.53
      2899692.13     10030355.61      2900743.82     10030053.64
#Sta/Elev= 30
  3535.8 1515.26  3911.8 1502.74  4270.8 1477.27  4357.5 1471.19  4483.4 1461.69
  4568.1 1445.92  4585.7 1434.47  4662.4 1426.21  4707.8 1425.47  4748.5 1424.46
  4789.2 1422.67  4941.8 1419.98  5004.4 1411.63 5059.09 1421.28  5063.9 1423.19
  5094.4 1445.06  5175.8 1447.89  5226.4 1462.88  5264.7 1466.53  5488.1 1472.42
  5529.2 1473.77    5770 1489.39  5873.9 1505.25  5955.2 1511.93  5977.8 1513.41
    6108 1518.33  6239.8 1533.07  6297.2 1538.24  6515.2 1588.14  6568.7  1613.1
#Mann= 20 ,-1 , 0
  3535.8      .1       0  4270.8     .16       0  4357.5     .05       0
  4483.4      .1       0  4568.1     .16       0  4662.4      .1       0
  4707.8     .16       0  4748.5      .1       0  4789.2     .07       0
  5063.9      .1       0  5226.4     .16       0  5264.7     .05       0
  5488.1      .1       0  5529.2     .05       0    5770      .1       0
  5873.9     .05       0  5955.2      .1       0  5977.8     .05       0
    6108      .1       0  6239.8     .16       0
#XS Ineff= 2 , 0
          4717.2 1426.25
Permanent Ineff=
       T       T
Bank Sta=4941.8,5059.09
XS Rating Curve= 0 ,0
Exp/Cntr=0.3,0.1

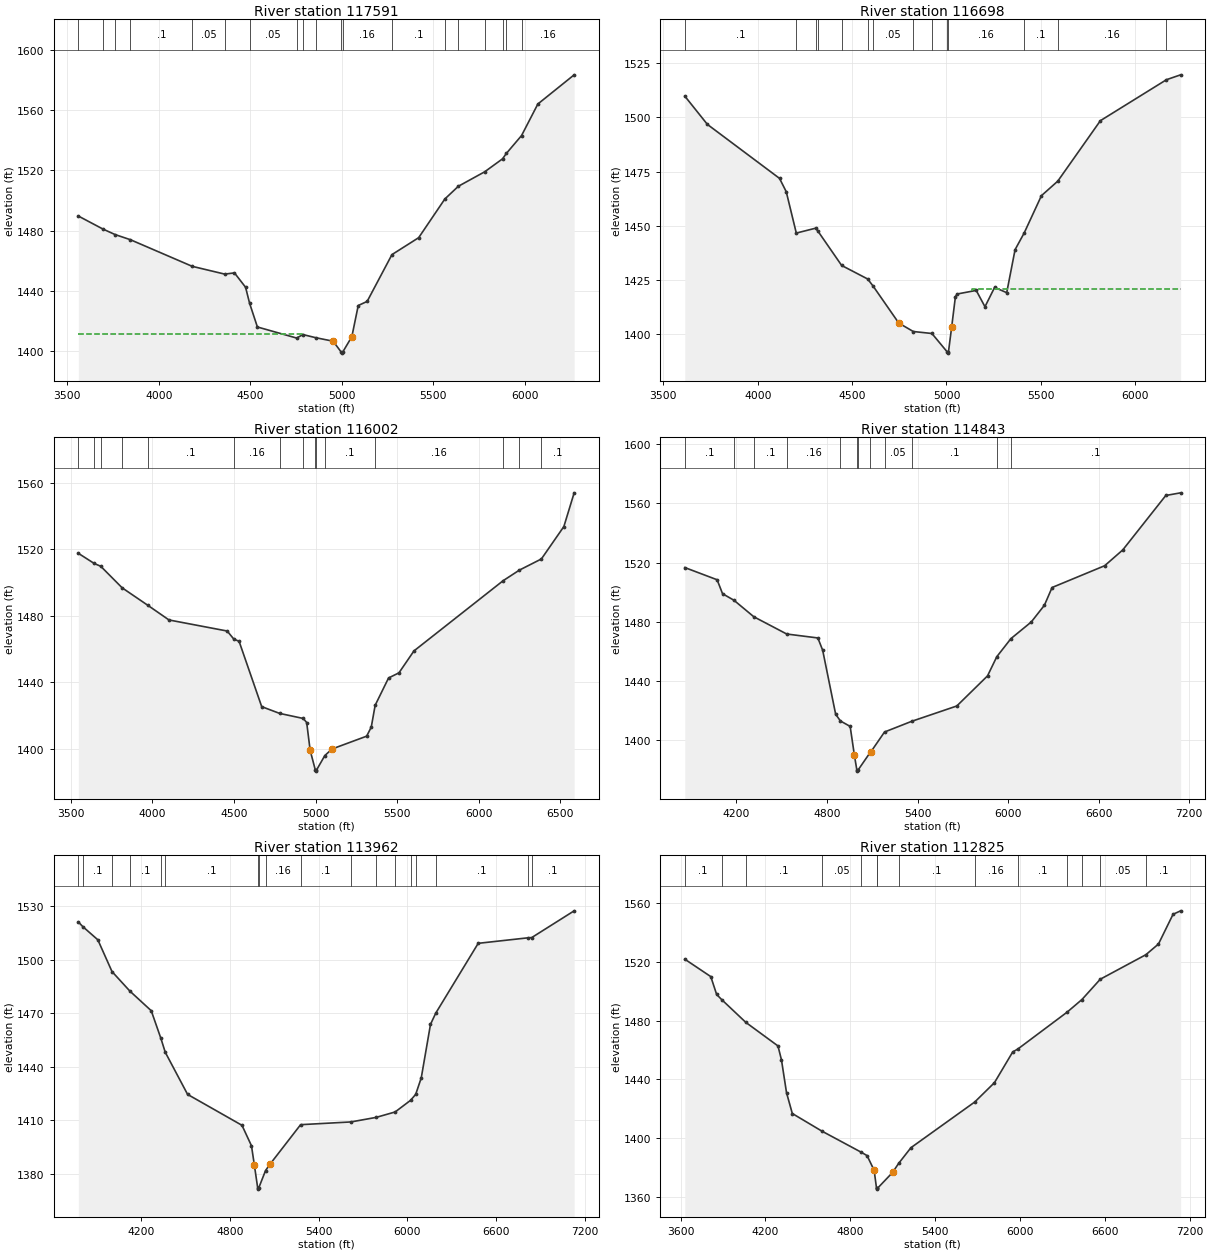
Type RM Length L Ch R = 1 ,117591  ,893,893,893
BEGIN DESCRIPTION:
MILLER CREEK 195.0
END DESCRIPTION:
XS GIS Cut Line= 4
      2899025.45     10032204.58      2899478.59     10031563.95
      2899827.54     10030688.95      2900718.18     10030272.27
#Sta/Elev= 30
  3560.8 1489.62    3695    1481  3761.9 1477.32  3845.1 1473.93  4183.2 1456.27
  4360.5 1451.12  4414.2 1451.91  4474.9 1442.39  4496.9 1431.77  4539.5 1416.06
  4754.2 1408.72  4788.2 1411.04  4858.3 1408.96  4953.3 1406.64  4998.8 1399.23
  5001.6 1398.73  5004.8 1399.23  5055.7 1409.62  5090.7  1430.3  5139.3    1433
  5274.9 1464.04    5421 1475.27  5564.1 1500.92  5637.8 1509.34  5781.8 1518.94
  5879.5 1527.54  5899.9 1531.07  5983.4 1542.98  6072.4 1563.88  6270.8 1583.22
#Mann= 19 ,-1 , 0
  3560.8     .05       0    3695      .1       0  3761.9     .05       0
  3845.1      .1       0  4183.2     .05       0  4360.5      .1       0
  4496.9     .05       0  4754.2     .16       0  4788.2      .1       0
  4858.3     .16       0  4998.8     .07       0  5004.8     .16       0
  5274.9      .1       0  5564.1     .05       0  5637.8      .1       0
  5781.8     .05       0  5879.5     .16       0  5899.9      .1       0
  5983.4     .16       0
#XS Ineff= 2 , 0
         4785.89 1411.55
Permanent Ineff=
       T       T
Bank Sta=4953.3,5055.7
XS Rating Curve= 0 ,0
Exp/Cntr=0.3,0.1

Type RM Length L Ch R = 1 ,116698  ,696,696,696
BEGIN DESCRIPTION:
MILLER CREEK 193.0
END DESCRIPTION:
XS GIS Cut Line= 4
       2898994.2     10032438.96      2899780.67     10031704.57
      2900296.29     10031688.95      2900832.78     10030803.49
#Sta/Elev= 30
  3613.4 1509.83  3733.2 1496.76  4115.3 1471.83  4150.9 1465.68  4204.2 1446.56
  4306.6 1448.82  4318.4 1447.51  4444.5 1431.61  4582.3 1425.35  4611.7 1422.01
  4747.3 1404.98    4824 1401.09  4922.8 1400.17  5004.4  1391.6  5007.1  1391.1
  5010.4  1391.6  5027.4 1403.13  5047.4 1417.26  5057.4 1418.43  5157.5 1420.07
  5203.9 1412.53    5255 1421.47  5319.1 1419.03  5363.4  1438.9  5411.7 1446.62
  5503.2 1463.85  5589.6 1470.55  5815.5 1498.49  6165.6 1517.42  6240.6 1519.67
#Mann= 14 ,-1 , 0
  3613.4      .1       0  4204.2     .16       0  4306.6     .05       0
  4318.4      .1       0  4444.5     .05       0  4582.3      .1       0
  4611.7     .05       0    4824      .1       0  4922.8     .16       0
  5004.4     .07       0  5010.4     .16       0  5411.7      .1       0
  5589.6     .16       0  6165.6     .05       0
#XS Ineff= 2 , 0
                         5132.95         1420.65
Permanent Ineff=
       T       T
Bank Sta=4747.3,5027.4
XS Rating Curve= 0 ,0
Exp/Cntr=0.3,0.1

Type RM Length L Ch R = 1 ,116002  ,1159,1159,1159
BEGIN DESCRIPTION:
MILLER CREEK 191.0
END DESCRIPTION:
XS GIS Cut Line= 3
      2898916.09     10032824.36      2899936.92     10032605.61
      2901363.77     10031210.01
#Sta/Elev= 30
  3545.4 1517.66  3642.7 1511.55  3683.1 1509.83  3814.1 1496.88  3972.1 1486.32
  4101.2 1477.54    4458 1470.88  4499.7 1465.91  4530.8 1464.75  4669.6 1425.37
  4779.6  1421.3  4924.5 1418.25  4945.4 1415.81  4966.7 1399.04  4998.9 1387.06
  5001.7 1386.56  5004.9 1387.06  5056.8 1395.95    5101 1399.89  5313.1  1407.6
  5341.4 1413.06  5365.2 1426.18  5447.4 1442.63  5511.2 1445.72    5603  1458.9
  6149.7 1501.16  6249.6 1507.55  6384.4 1514.26  6522.3 1533.78  6585.3 1554.06
#Mann= 15 ,-1 , 0
  3545.4      .1       0  3642.7     .05       0  3683.1      .1       0
  3814.1     .05       0  3972.1      .1       0  4499.7     .16       0
  4779.6      .1       0  4924.5     .16       0  4998.9     .07       0
  5004.9     .16       0  5056.8      .1       0  5365.2     .16       0
  6149.7      .1       0  6249.6     .05       0  6384.4      .1       0
Bank Sta=4966.7,5101
XS Rating Curve= 0 ,0
Exp/Cntr=0.3,0.1

Type RM Length L Ch R = 1 ,114843  ,881,881,881
BEGIN DESCRIPTION:
MILLER CREEK 190.0
END DESCRIPTION:
XS GIS Cut Line= 4
       2898952.5     10032907.69      2899765.04     10033110.82
      2900332.75     10033173.32      2902174.96     10032824.66
#Sta/Elev= 30
  3858.9 1516.67  4072.9 1508.41  4108.9 1498.96  4184.3 1494.56  4315.9 1483.39
  4533.8 1471.72  4740.1 1469.05    4772 1460.74    4858 1417.44  4889.7 1412.89
    4954 1409.24  4981.6 1390.04  4998.7 1379.49  5001.5 1378.99  5004.7 1379.49
  5082.7 1391.03  5092.3 1392.19  5181.5 1405.44  5362.5 1412.72  5660.2 1423.04
  5863.7  1443.4  5925.1 1456.37  6018.8 1468.61  6153.2 1479.84  6240.3 1491.15
  6291.2 1503.17  6639.5  1517.9  6759.3 1528.58  7044.3  1565.4  7142.5  1567.2
#Mann= 12 ,-1 , 0
  3858.9      .1       0  4184.3     .05       0  4315.9      .1       0
  4533.8     .16       0  4889.7      .1       0  4998.7     .07       0
  5004.7      .1       0  5082.7     .16       0  5181.5     .05       0
  5362.5      .1       0  5925.1     .16       0  6018.8      .1       0
Bank Sta=4981.6,5092.3
XS Rating Curve= 0 ,0
Exp/Cntr=0.3,0.1

Type RM Length L Ch R = 1 ,113962  ,1137,1137,1137
BEGIN DESCRIPTION:
MILLER CREEK 187.0
END DESCRIPTION:
XS GIS Cut Line= 4
      2899186.92     10034204.57      2900192.13     10034142.07
      2900598.38     10033464.99      2902091.76     10033038.31
#Sta/Elev= 30
  3776.6 1521.29  3805.9 1518.71  3908.4 1511.24  4004.1 1493.41  4125.1 1482.43
  4269.1 1471.44  4334.5 1455.88  4363.7 1448.14  4514.9 1424.45  4882.2 1407.11
  4946.4 1395.62 4965.91 1384.78  4988.7 1371.78  4991.5 1371.28  4994.7 1371.78
  5041.5  1381.7  5072.7 1385.39  5278.4 1407.46  5618.6    1409  5788.5 1411.55
  5917.1  1414.6    6021 1421.12  6055.9 1424.49  6093.5 1433.74  6155.9 1463.79
  6191.5 1470.09  6478.3 1509.27  6817.8 1512.39  6839.6 1512.48  7126.5 1527.51
#Mann= 18 ,-1 , 0
  3776.6     .05       0  3805.9      .1       0  4004.1     .05       0
  4125.1      .1       0  4334.5     .16       0  4363.7      .1       0
  4988.7     .07       0  4994.7      .1       0  5041.5     .16       0
  5278.4      .1       0  5618.6     .05       0  5788.5      .1       0
  5917.1     .05       0    6021      .1       0  6055.9     .16       0
  6191.5      .1       0  6817.8     .16       0  6839.6      .1       0
Bank Sta=4965.91,5072.7
XS Rating Curve= 0 ,0
Exp/Cntr=0.3,0.1

Type RM Length L Ch R = 1 ,112825  ,701,701,701
BEGIN DESCRIPTION:
MILLER CREEK 184.0
END DESCRIPTION:
XS GIS Cut Line= 4
      2899150.51     10034459.79      2900087.96     10034699.36
      2901421.29      10034657.7      2902473.34     10034074.39
#Sta/Elev= 30
  3630.3 1521.69    3814 1509.85  3855.3 1497.74  3891.1 1494.21  4061.8 1478.72
  4288.8 1462.72  4313.6 1453.23  4349.3 1430.94  4390.1 1416.79  4598.6 1404.85
  4875.8 1390.54  4918.5 1388.17  4968.6 1378.16  4985.6 1365.88  4988.3 1365.38
  4991.6 1365.88  5098.6 1376.69  5142.2 1382.93  5228.7 1393.55  5679.9 1424.63
    5819 1437.76  5948.1 1458.65    5984 1460.61  6332.1 1485.66  6437.5 1494.28
  6566.9 1508.08  6889.2 1524.74  6978.2    1532  7081.2  1552.2  7134.8 1554.57
#Mann= 14 ,-1 , 0
  3630.3      .1       0  3891.1     .05       0  4061.8      .1       0
  4598.6     .05       0  4875.8      .1       0  4985.6     .07       0
  4991.6      .1       0  5142.2      .1       0  5679.9     .16       0
    5984      .1       0  6332.1     .05       0  6437.5      .1       0
  6566.9     .05       0  6889.2      .1       0
Bank Sta=4968.6,5098.6
XS Rating Curve= 0 ,0
Exp/Cntr=0.3,0.1