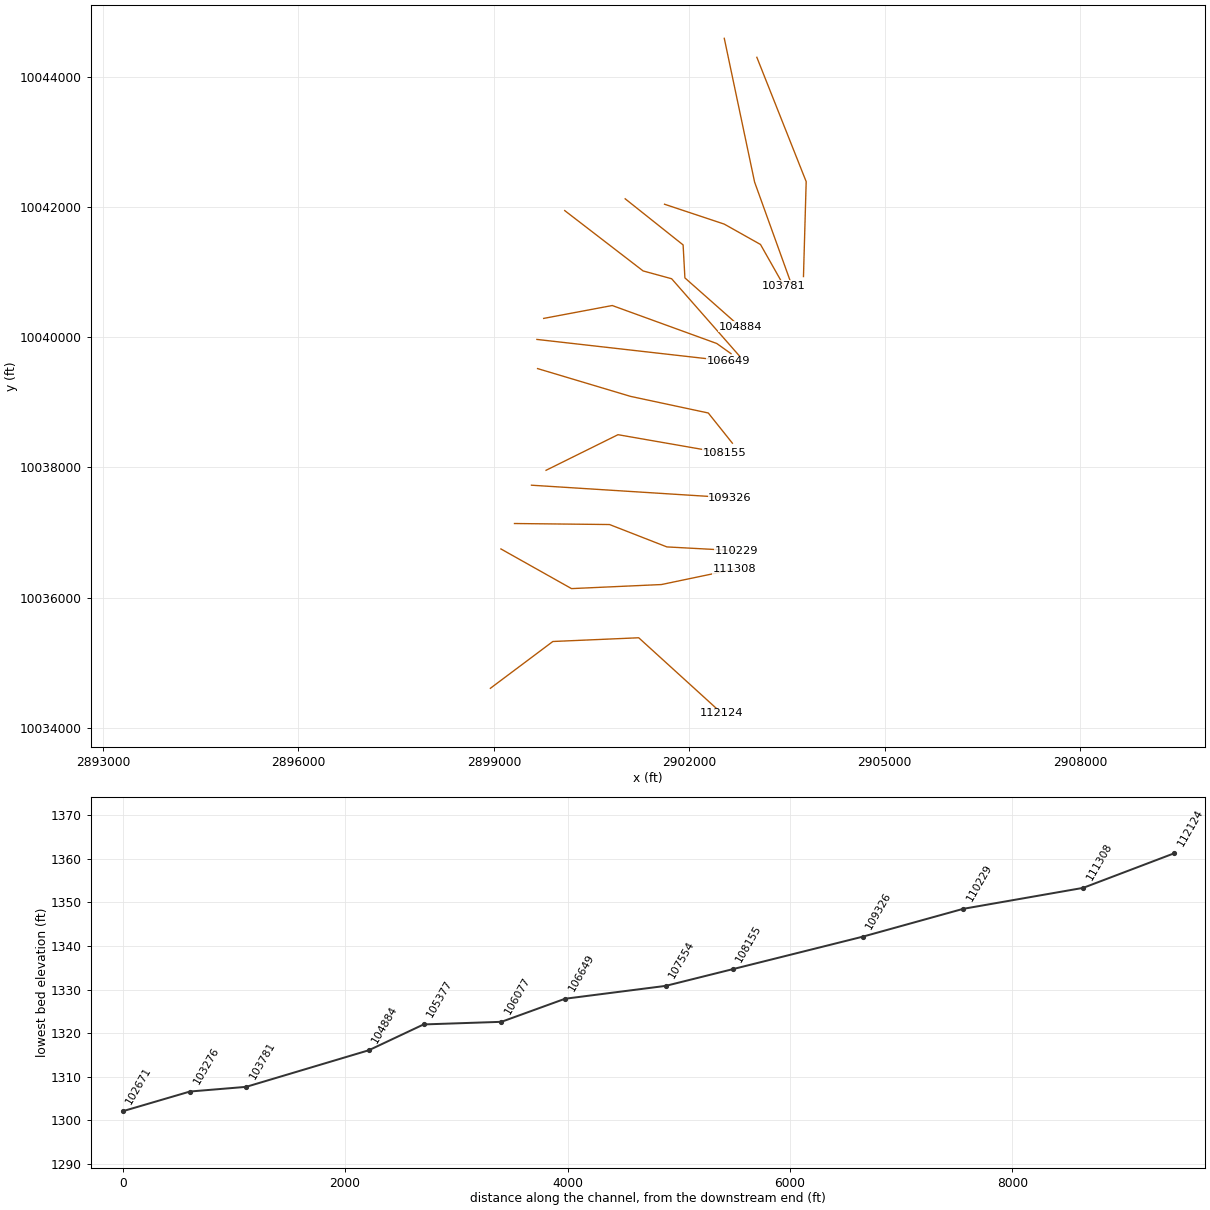
HEC-RAS study MILLER CREEK.prj: MILLER CREEK Base Level Engineering

--- MILLER CREEK.g01 (geometry) --- (continued)

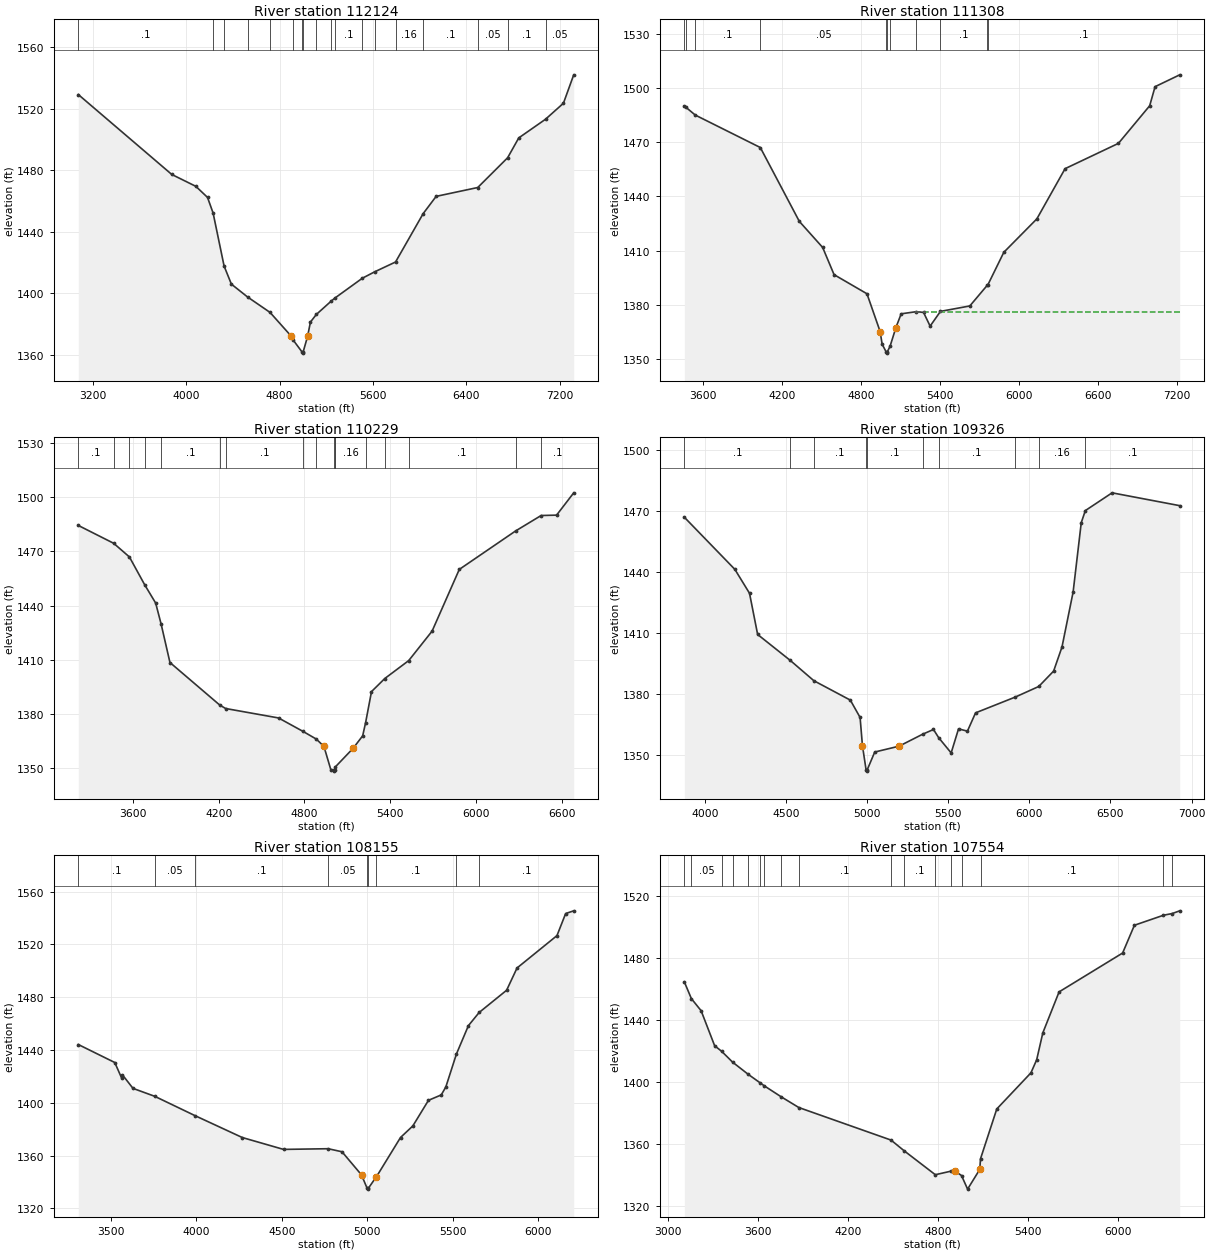
Type RM Length L Ch R = 1 ,112124  ,816,816,816
BEGIN DESCRIPTION:
MILLER CREEK 183.0
END DESCRIPTION:
XS GIS Cut Line= 4
      2898947.33     10034605.61      2899905.67     10035324.36
      2901223.38     10035381.66      2902499.45     10034220.17
#Sta/Elev= 30
  3076.6 1529.16  3876.8 1477.27    4083 1469.55    4183 1462.36    4231 1452.18
    4325 1417.78  4387.4 1406.02  4525.6  1397.7  4718.4 1387.66  4897.9  1372.4
  4917.6 1369.59    4995 1361.71  4997.8 1361.21    5001 1361.71 5039.77 1372.03
  5064.4 1381.39  5114.8 1386.32  5240.3 1394.87  5271.2 1396.83    5509 1409.87
  5613.4 1413.98  5793.2  1420.4  6029.8 1451.83    6141 1463.03  6497.2 1468.78
  6753.1 1488.11  6848.4    1501  7077.8 1513.14  7230.9 1523.51    7319 1541.97
#Mann= 18 ,-1 , 0
  3076.6      .1       0    4231     .16       0    4325      .1       0
  4525.6     .16       0  4718.4      .1       0  4917.6     .16       0
    4995     .07       0    5001     .16       0  5114.8      .1       0
  5240.3     .05       0  5271.2      .1       0    5509     .16       0
  5613.4     .05       0  5793.2     .16       0  6029.8      .1       0
  6497.2     .05       0  6753.1      .1       0  7077.8     .05       0
Bank Sta=4897.9,5039.77
XS Rating Curve= 0 ,0
Exp/Cntr=0.3,0.1

Type RM Length L Ch R = 1 ,111308  ,1079,1079,1079
BEGIN DESCRIPTION:
MILLER CREEK 180.0
END DESCRIPTION:
XS GIS Cut Line= 4
      2899108.81     10036746.23      2900192.13     10036136.86
      2901572.34     10036199.36       2902692.1     10036433.73
#Sta/Elev= 30
  3455.3 1489.81  3467.1 1489.33  3538.7 1485.01  4033.5 1467.05    4330 1426.22
  4507.8 1411.76  4594.5 1396.72  4844.7 1386.15  4944.8 1365.27  4960.2 1358.25
  4991.9 1353.81  4994.6 1353.31  4997.9 1353.81  5020.5 1357.11    5065 1367.46
    5105 1375.06  5217.6 1376.22  5275.2 1375.83  5325.2 1368.25  5403.8  1376.4
  5627.2 1379.41  5760.9 1390.93  5765.6 1391.26  5885.8 1409.09  6137.2 1427.59
  6351.8 1455.35  6757.7 1469.36  6995.4 1490.16  7036.3 1500.71  7223.9 1507.27
#Mann= 11 ,-1 , 0
  3455.3      .1       0  3467.1     .05       0  3538.7      .1       0
  4033.5     .05       0  4991.9    .035       0  4997.9     .05       0
  5020.5     .16       0  5217.6     .05       0  5403.8      .1       0
  5760.9     .16       0  5765.6      .1       0
#XS Ineff= 2 , 0
                         5210.23         1376.27
Permanent Ineff=
       T       T
Bank Sta=4944.8,5065
XS Rating Curve= 0 ,0
Exp/Cntr=0.3,0.1

Type RM Length L Ch R = 1 ,110229  ,903,903,903
BEGIN DESCRIPTION:
MILLER CREEK 178.0
END DESCRIPTION:
XS GIS Cut Line= 4
      2899317.08     10037136.86      2900775.46     10037121.24
      2901655.67     10036777.49      2902718.22     10036720.19
#Sta/Elev= 30
  3217.7 1484.39  3465.2 1474.52  3575.5 1466.95  3682.1 1451.59  3759.1 1441.46
  3797.4 1429.83  3859.1 1408.58  4208.1 1385.01  4249.1 1383.13  4619.2 1377.91
  4791.3 1370.44    4884  1366.2    4937 1362.14  4985.4 1349.23  5006.9    1349
  5009.6  1348.5  5012.9    1349  5016.4  1350.8    5141 1361.11  5208.1 1368.03
  5228.7 1375.37  5269.8 1392.48  5362.8 1399.72  5530.3 1409.64    5694 1425.94
  5884.3 1460.07    6278 1481.32    6457 1489.88  6565.3 1490.09  6685.2 1502.43
#Mann= 17 ,-1 , 0
  3217.7      .1       0  3465.2     .05       0  3575.5      .1       0
  3682.1     .05       0  3797.4      .1       0  4208.1     .05       0
  4249.1      .1       0  4791.3     .05       0    4884      .1       0
  5006.9     .07       0  5012.9      .1       0  5016.4     .16       0
  5228.7      .1       0  5362.8     .05       0  5530.3      .1       0
    6278     .05       0    6457      .1       0
Bank Sta=4937,5141
XS Rating Curve= 0 ,0
Exp/Cntr=0.3,0.1

Type RM Length L Ch R = 1 ,109326  ,1171,1171,1171
BEGIN DESCRIPTION:
MILLER CREEK 176.0
END DESCRIPTION:
XS GIS Cut Line= 2
      2899577.54     10037725.41      2902623.96     10037532.73
#Sta/Elev= 30
  3874.1 1467.11  4185.6 1441.43  4275.8 1429.67  4325.9 1409.39  4527.3 1396.59
  4672.2 1386.63  4897.1 1377.07  4957.2 1368.53 4971.59 1354.72  4994.3 1342.62
    4997 1342.12  5000.3 1342.62  5047.4 1351.52  5197.7 1354.41  5342.1 1360.27
  5409.4 1362.62  5441.2  1358.6  5518.3 1351.08  5563.7 1362.93  5618.5 1361.79
  5668.6  1370.8  5913.2 1378.57  6057.9 1383.78  6149.6 1391.36  6201.2 1403.22
  6269.8  1430.3  6319.9 1464.42  6345.1 1470.37  6509.9 1479.11  6926.6 1472.79
#Mann= 10 ,-1 , 0
  3874.1      .1       0  4527.3     .05       0  4672.2      .1       0
  4994.3     .07       0  5000.3      .1       0  5342.1     .05       0
  5441.2      .1       0  5913.2     .05       0  6057.9     .16       0
  6345.1      .1       0
#XS Ineff= 3 ,-1
 5387.97 5408.06 1361.49 5409.44 5562.65 1362.58 5563.76 5632.64 1362.84
Permanent Ineff=
       T       T       T
Bank Sta=4971.59,5197.7
XS Rating Curve= 0 ,0
Exp/Cntr=0.3,0.1

Type RM Length L Ch R = 1 ,108155  ,601,601,601
BEGIN DESCRIPTION:
MILLER CREEK 174.0
END DESCRIPTION:
XS GIS Cut Line= 3
       2899801.5     10037954.57      2900905.67     10038501.45
      2902544.89     10038215.23
#Sta/Elev= 30
    3310  1444.2  3523.2 1430.57  3562.5 1419.04    3568 1421.23  3629.7 1410.98
  3756.7 1404.98  3990.6 1390.43  4268.8 1373.74  4509.9 1364.75  4770.7 1365.27
  4851.6 1362.96  4965.6 1345.45  4998.8 1335.16  5001.6 1334.66  5004.8 1335.16
  5047.8 1343.18  5052.6 1343.96  5193.6 1373.76  5265.8 1382.55  5357.1 1401.94
  5431.7 1406.02  5458.6 1412.06  5520.6 1437.05  5590.6 1458.51  5653.3 1468.47
  5813.9 1485.31  5874.8 1502.17  6108.3  1526.7  6159.1 1543.43  6206.2 1545.48
#Mann= 9 ,-1 , 0
    3310      .1       0  3756.7     .05       0  3990.6      .1       0
  4770.7     .05       0  4998.8    .035       0  5004.8     .05       0
  5047.8      .1       0  5520.6     .16       0  5653.3      .1       0
Bank Sta=4965.6,5052.6
XS Rating Curve= 0 ,0
Exp/Cntr=0.3,0.1

Type RM Length L Ch R = 1 ,107554  ,905,905,905
BEGIN DESCRIPTION:
MILLER CREEK 172.0
END DESCRIPTION:
XS GIS Cut Line= 4
      2899671.26     10039517.08      2901098.38     10039089.99
      2902291.09     10038834.78      2902660.86     10038371.27
#Sta/Elev= 30
  3106.6 1464.63  3153.7 1453.78  3218.5    1446  3308.7 1423.39  3355.9 1419.75
  3428.2 1412.81  3532.5 1404.93  3614.2 1399.28  3639.3 1397.52  3751.9 1390.45
  3869.7 1383.51  4484.6 1362.49  4571.2 1355.64  4779.8 1340.14  4881.7 1342.38
  4913.4 1342.32  4954.3 1339.62  4994.9 1330.84    5076 1343.55  5081.1 1350.45
  5189.5 1382.58  5417.2  1405.9  5455.4 1414.31  5496.3 1431.67  5604.8 1458.14
  6028.3 1483.22  6106.8 1501.14  6300.6  1507.6  6358.3 1508.69  6408.9 1510.45
#Mann= 17 ,-1 , 0
  3106.6      .1       0  3153.7     .05       0  3355.9      .1       0
  3428.2     .05       0  3532.5      .1       0  3614.2     .05       0
  3639.3      .1       0  3751.9     .05       0  3869.7      .1       0
  4484.6     .05       0  4571.2      .1       0  4779.8     .05       0
  4881.7     .16       0  4954.3     .07       0  5081.1      .1       0
  6300.6     .05       0  6358.3      .1       0
Bank Sta=4913.4,5076
XS Rating Curve= 0 ,0
Exp/Cntr=0.3,0.1

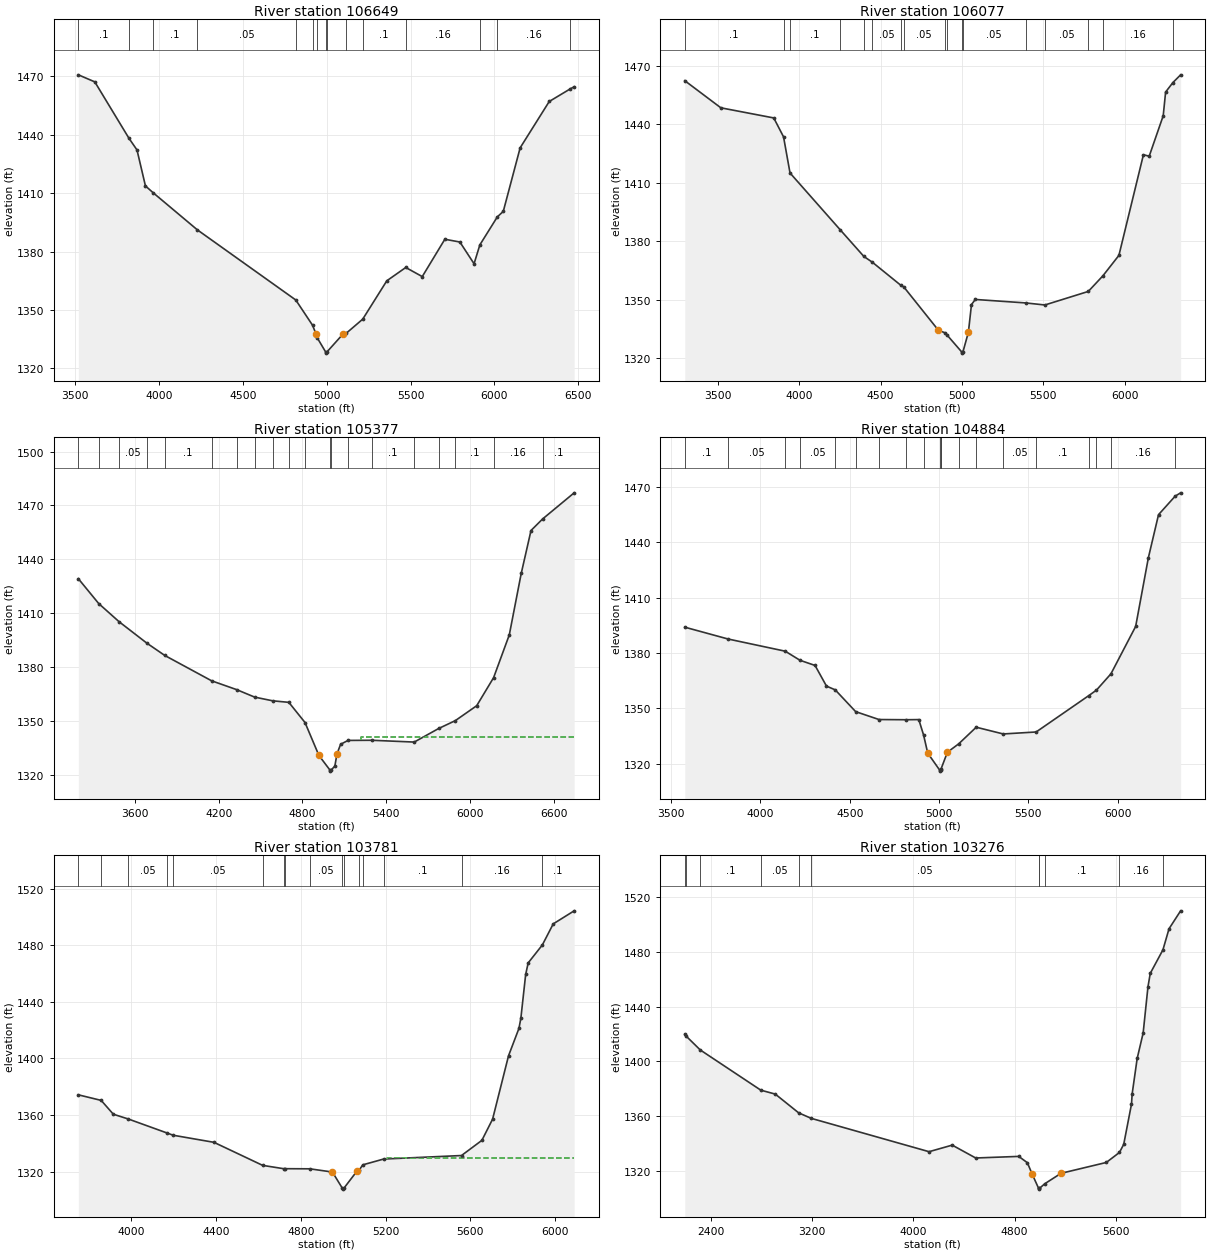
Type RM Length L Ch R = 1 ,106649  ,572,572,572
BEGIN DESCRIPTION:
MILLER CREEK 170.0
END DESCRIPTION:
XS GIS Cut Line= 2
      2899660.92     10039964.98      2902598.37     10039631.66
#Sta/Elev= 30
  3518.8 1470.82    3617  1467.2  3820.3 1438.28  3868.6 1432.23  3918.9 1413.77
    3964 1410.32  4228.5  1391.2  4815.3 1355.18    4915 1342.25  4935.4 1337.87
  4944.5 1335.58    4994 1328.39  4996.8 1327.89    5000 1328.39  5096.4 1337.64
  5114.6 1337.98  5214.4 1345.33  5358.1 1365.04  5471.1 1371.87  5569.4  1367.2
  5704.1 1386.37  5793.7 1384.96  5878.3 1373.79  5912.8 1383.48  6017.1 1397.87
  6052.5 1400.69  6153.1 1433.33  6326.5 1457.13  6453.1 1463.67  6475.1 1464.68
#Mann= 15 ,-1 , 0
  3518.8      .1       0  3820.3     .05       0    3964      .1       0
  4228.5     .05       0  4815.3      .1       0    4915     .05       0
  4944.5     .16       0    4994     .07       0    5000     .16       0
  5114.6     .05       0  5214.4      .1       0  5471.1     .16       0
  5912.8      .1       0  6017.1     .16       0  6453.1      .1       0
Bank Sta=4935.4,5096.4
XS Rating Curve= 0 ,0
Exp/Cntr=0.3,0.1

Type RM Length L Ch R = 1 ,106077  ,700,700,700
BEGIN DESCRIPTION:
MILLER CREEK 169.0
END DESCRIPTION:
XS GIS Cut Line= 4
      2899765.06     10040287.91      2900817.13     10040485.82
      2902421.29     10039902.49      2902640.06     10039746.23
#Sta/Elev= 30
  3296.8 1462.24  3518.3 1448.34  3843.4 1443.15  3903.5 1433.45  3943.3 1414.94
    4252 1385.78  4397.1 1372.15  4449.8 1369.15  4622.4 1357.48  4642.3 1356.53
  4854.6 1334.36  4893.4 1333.08  4905.7  1332.1  4999.2  1323.1    5002  1322.6
  5005.2  1323.1  5039.1 1333.25  5058.1 1347.49  5081.7 1350.11  5390.1 1348.34
    5509 1347.28  5775.8 1354.22  5865.4 1362.21  5963.9  1372.7  6114.5 1424.28
  6150.1 1423.55  6236.1 1444.26  6250.9 1456.42  6295.9 1461.31  6343.1 1465.25
#Mann= 17 ,-1 , 0
  3296.8      .1       0  3903.5     .05       0  3943.3      .1       0
    4252     .05       0  4397.1      .1       0  4449.8     .05       0
  4622.4      .1       0  4642.3     .05       0  4893.4      .1       0
  4905.7     .05       0  4999.2    .035       0  5005.2     .05       0
  5390.1      .1       0    5509     .05       0  5775.8      .1       0
  5865.4     .16       0  6295.9      .1       0
Bank Sta=4854.6,5039.1
XS Rating Curve= 0 ,0
Exp/Cntr=0.3,0.1

Type RM Length L Ch R = 1 ,105377  ,493,493,493
BEGIN DESCRIPTION:
MILLER CREEK 168.0
END DESCRIPTION:
XS GIS Cut Line= 4
      2900087.93     10041944.18      2901291.09     10041017.07
      2901728.59     10040897.28      2902770.28     10039709.75
#Sta/Elev= 30
  3194.5 1429.21  3340.5 1415.36  3486.5 1405.24  3684.9 1393.33  3813.7 1386.45
  4149.4 1372.32  4328.9  1367.4  4457.7 1363.24  4586.5 1361.18  4702.6 1360.32
  4818.4 1349.09  4918.1 1330.73    4998  1322.5  5000.8    1322    5004  1322.5
  5032.1 1324.75  5047.8 1331.68  5073.6 1336.95  5126.6 1339.11    5298 1339.19
    5601 1338.19  5776.3 1345.76  5895.5 1350.14  6048.5 1358.44  6169.7  1374.1
    6282 1397.91  6367.4 1432.12  6437.6 1456.06  6520.1 1462.45  6746.7 1477.05
#Mann= 20 ,-1 , 0
  3194.5      .1       0  3340.5     .05       0  3486.5     .05       0
  3684.9     .05       0  3813.7      .1       0  4149.4     .16       0
  4328.9      .1       0  4457.7     .05       0  4586.5      .1       0
  4702.6      .1       0  4818.4     .05       0    4998    .035       0
    5004     .05       0  5126.6     .05       0    5298      .1       0
    5601     .05       0  5776.3     .05       0  5895.5      .1       0
  6169.7     .16       0  6520.1      .1       0
#XS Ineff= 2 , 0
                         5218.18         1341.23
Permanent Ineff=
       T       T
Bank Sta=4918.1,5047.8
XS Rating Curve= 0 ,0
Exp/Cntr=0.3,0.1

Type RM Length L Ch R = 1 ,104884  ,1103,1103,1103
BEGIN DESCRIPTION:
MILLER CREEK 167.0
END DESCRIPTION:
XS GIS Cut Line= 4
      2901015.79      10042125.2      2901904.66     10041416.88
      2901932.43     10040909.94      2902779.68     10040159.92
#Sta/Elev= 30
  3576.7 1394.03  3819.7 1387.61  4138.9 1381.03  4221.8  1376.1  4305.9 1373.31
  4369.9 1362.12    4419 1360.08  4533.3 1348.29  4663.9 1344.02  4815.1 1343.91
  4886.7 1343.99  4913.4 1335.67  4936.8 1325.84  5003.9 1316.58  5006.6 1316.08
  5009.9 1316.58  5011.7 1317.38  5046.9 1326.31  5109.9 1330.84  5208.2 1339.86
  5359.3 1336.21  5543.7 1337.28  5838.4 1356.98  5881.2 1359.94  5962.3 1368.76
  6100.8 1394.44  6171.9 1431.62  6228.8 1454.96  6321.8 1464.97  6352.5 1466.79
#Mann= 20 ,-1 , 0
  3576.7      .1       0  3819.7     .05       0  4138.9     .16       0
  4221.8     .05       0    4419     .05       0  4533.3      .1       0
  4663.9     .05       0  4815.1      .1       0  4913.4     .05       0
  5003.9    .035       0  5009.9     .05       0  5011.7      .1       0
  5109.9     .05       0  5208.2      .1       0  5359.3     .05       0
  5543.7      .1       0  5838.4     .16       0  5881.2      .1       0
  5962.3     .16       0  6321.8      .1       0
Bank Sta=4936.8,5046.9
XS Rating Curve= 0 ,0
Exp/Cntr=0.3,0.1

Type RM Length L Ch R = 1 ,103781  ,505,505,505
BEGIN DESCRIPTION:
MILLER CREEK 165.0
END DESCRIPTION:
XS GIS Cut Line= 4
      2901619.94     10042041.88       2902536.6     10041736.33
      2903092.16     10041423.83      2903453.25     10040784.97
#Sta/Elev= 30
  3751.7 1374.32  3859.4 1370.38  3916.7 1360.61  3987.7 1357.22    4169  1347.4
  4198.7 1345.77    4391 1340.76  4620.7 1324.47  4719.8 1322.12    4727 1322.13
    4843 1322.04  4949.6 1319.76  4996.9 1308.19  4999.6 1307.69  5002.9 1308.19
  5064.9 1320.34    5075 1320.99  5092.8 1324.85  5190.9 1328.94  5558.1 1331.43
  5654.1 1342.14  5704.7 1357.13  5779.8  1401.9  5828.8 1421.22  5837.9 1428.34
  5860.6 1459.34  5872.4 1467.52  5939.2 1480.19  5990.5  1495.1  6089.2 1504.32
#Mann= 16 ,-1 , 0
  3751.7     .05       0  3859.4      .1       0  3987.7     .05       0
    4169      .1       0  4198.7     .05       0  4620.7      .1       0
  4719.8     .05       0    4727      .1       0    4843     .05       0
  4996.9    .035       0  5002.9     .05       0    5075      .1       0
  5092.8     .05       0  5190.9      .1       0  5558.1     .16       0
  5939.2      .1       0
#XS Ineff= 2 , 0
                          5205.1         1329.33
Permanent Ineff=
       T       T
Bank Sta=4949.6,5064.9
XS Rating Curve= 0 ,0
Exp/Cntr=0.3,0.1

Type RM Length L Ch R = 1 ,103276  ,605,605,605
BEGIN DESCRIPTION:
MILLER CREEK 164.0
END DESCRIPTION:
XS GIS Cut Line= 3
      2902536.61     10044590.46      2903001.88     10042382.16
      2903563.92     10040820.93
#Sta/Elev= 30
  2194.9 1419.83  2202.2 1418.82  2316.9  1408.4  2795.2 1378.99  2909.6 1376.11
  3094.1  1362.4  3193.7 1358.37    4124 1333.99    4307  1338.8  4492.5 1329.39
  4832.6 1330.55  4900.5 1325.93  4938.9 1317.54  4989.6 1307.12  4992.3 1306.62
  4995.6 1307.12  5038.1 1310.56  5166.2 1318.17    5524 1326.12  5627.8 1333.43
  5661.6 1339.38    5723 1368.81  5728.3 1376.32  5767.9 1402.19  5815.1 1420.82
  5852.9 1454.44  5871.2  1464.4  5971.3 1481.61  6019.4 1497.01    6111 1510.13
#Mann= 11 ,-1 , 0
  2194.9      .1       0  2202.2     .05       0  2316.9      .1       0
  2795.2     .05       0  3094.1      .1       0  3193.7     .05       0
  4989.6    .035       0  4995.6     .05       0  5038.1      .1       0
  5627.8     .16       0  5971.3      .1       0
Bank Sta=4938.9,5166.2
XS Rating Curve= 0 ,0
Exp/Cntr=0.3,0.1

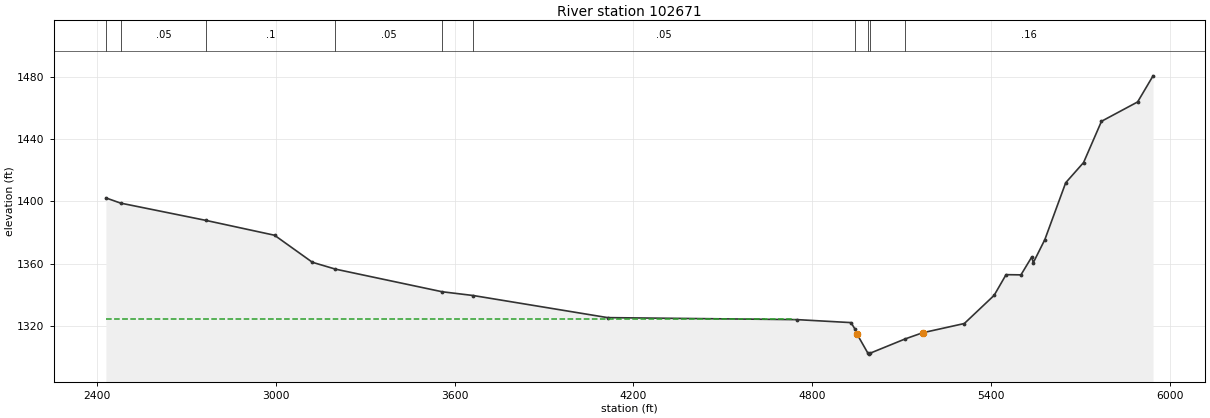
Type RM Length L Ch R = 1 ,102671  ,820,820,820
BEGIN DESCRIPTION:
MILLER CREEK 163.0
END DESCRIPTION:
XS GIS Cut Line= 3
       2903036.6     10044298.82      2903793.55     10042389.11
      2903751.88     10040930.76
#Sta/Elev= 30
  2430.4  1402.3  2479.6 1398.97  2767.1 1387.83  2996.2 1378.35  3123.2    1361
  3200.7 1356.61  3558.7  1342.1  3662.8 1339.69  4113.9 1325.51  4750.1 1324.22
  4930.2 1322.32  4942.8 1318.38  4950.2 1315.03  4987.2  1302.6    4990  1302.1
  4993.2  1302.6  5112.7 1311.91  5170.3 1315.79  5310.4 1321.73  5410.4  1339.8
  5450.4 1353.07  5500.4 1352.94  5536.7 1364.44  5541.7 1360.71  5580.5 1375.55
  5650.5 1412.02  5710.5 1424.99  5770.6 1451.44  5891.8 1463.85  5943.6  1480.6
#Mann= 10 ,-1 , 0
  2430.4      .1       0  2479.6     .05       0  2767.1      .1       0
  3200.7     .05       0  3558.7      .1       0  3662.8     .05       0
  4942.8      .1       0  4987.2     .07       0  4993.2      .1       0
  5112.7     .16       0
#XS Ineff= 2 , 0
         4738.64 1324.53
Permanent Ineff=
       T       T
Bank Sta=4950.2,5170.3
XS Rating Curve= 0 ,0
Exp/Cntr=0.3,0.1