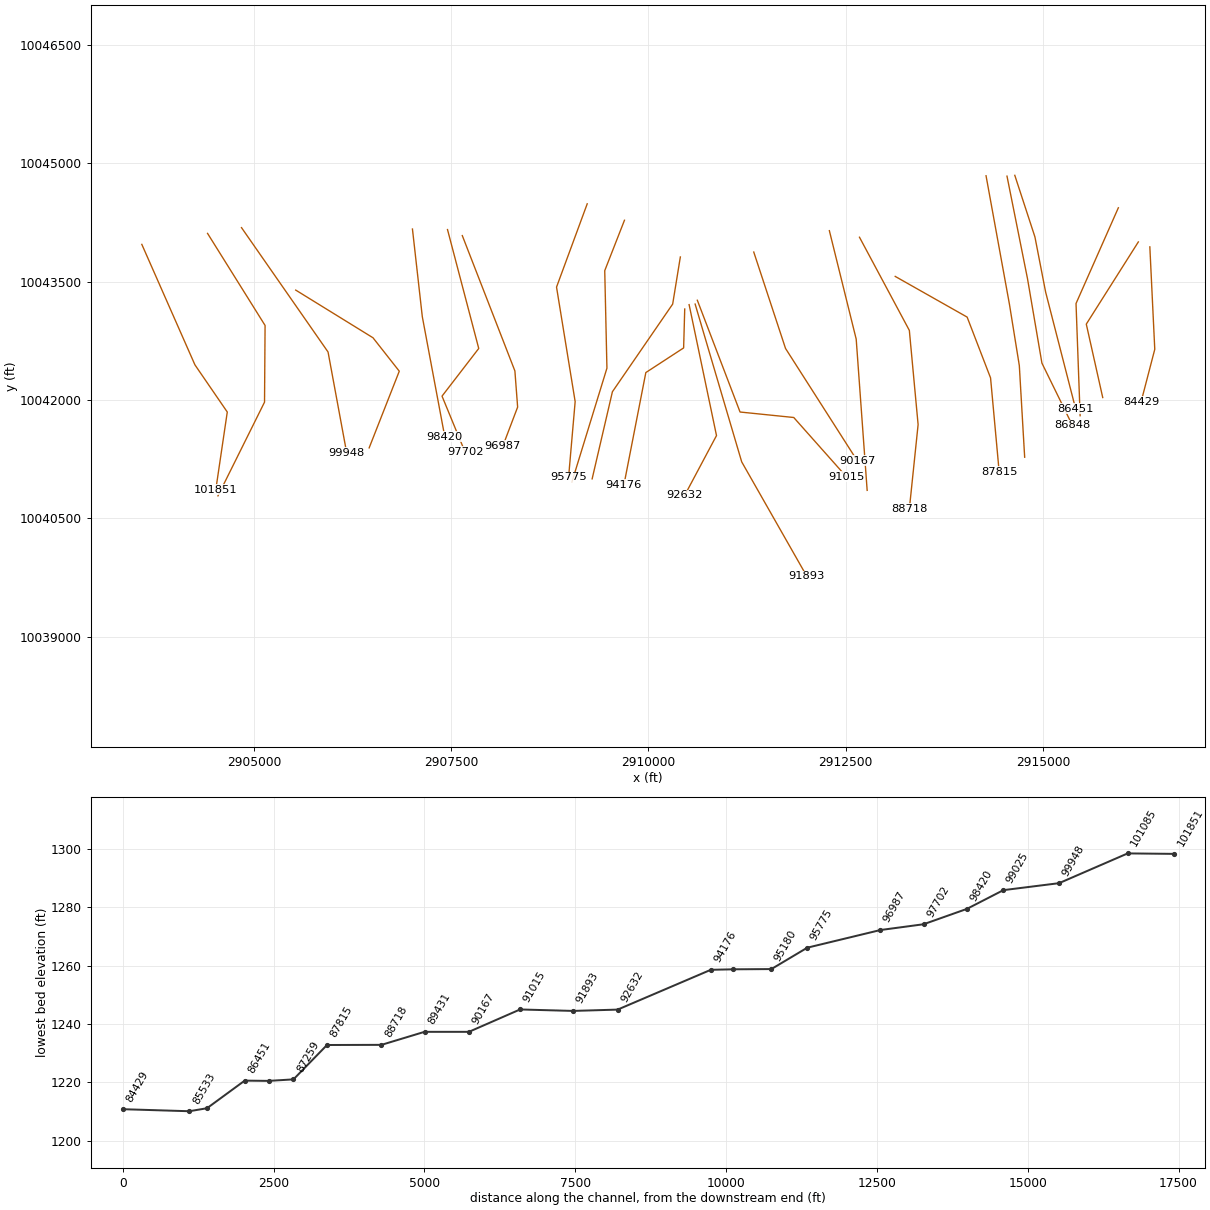
HEC-RAS study MILLER CREEK.prj: MILLER CREEK Base Level Engineering

--- MILLER CREEK.g01 (geometry) --- (continued)

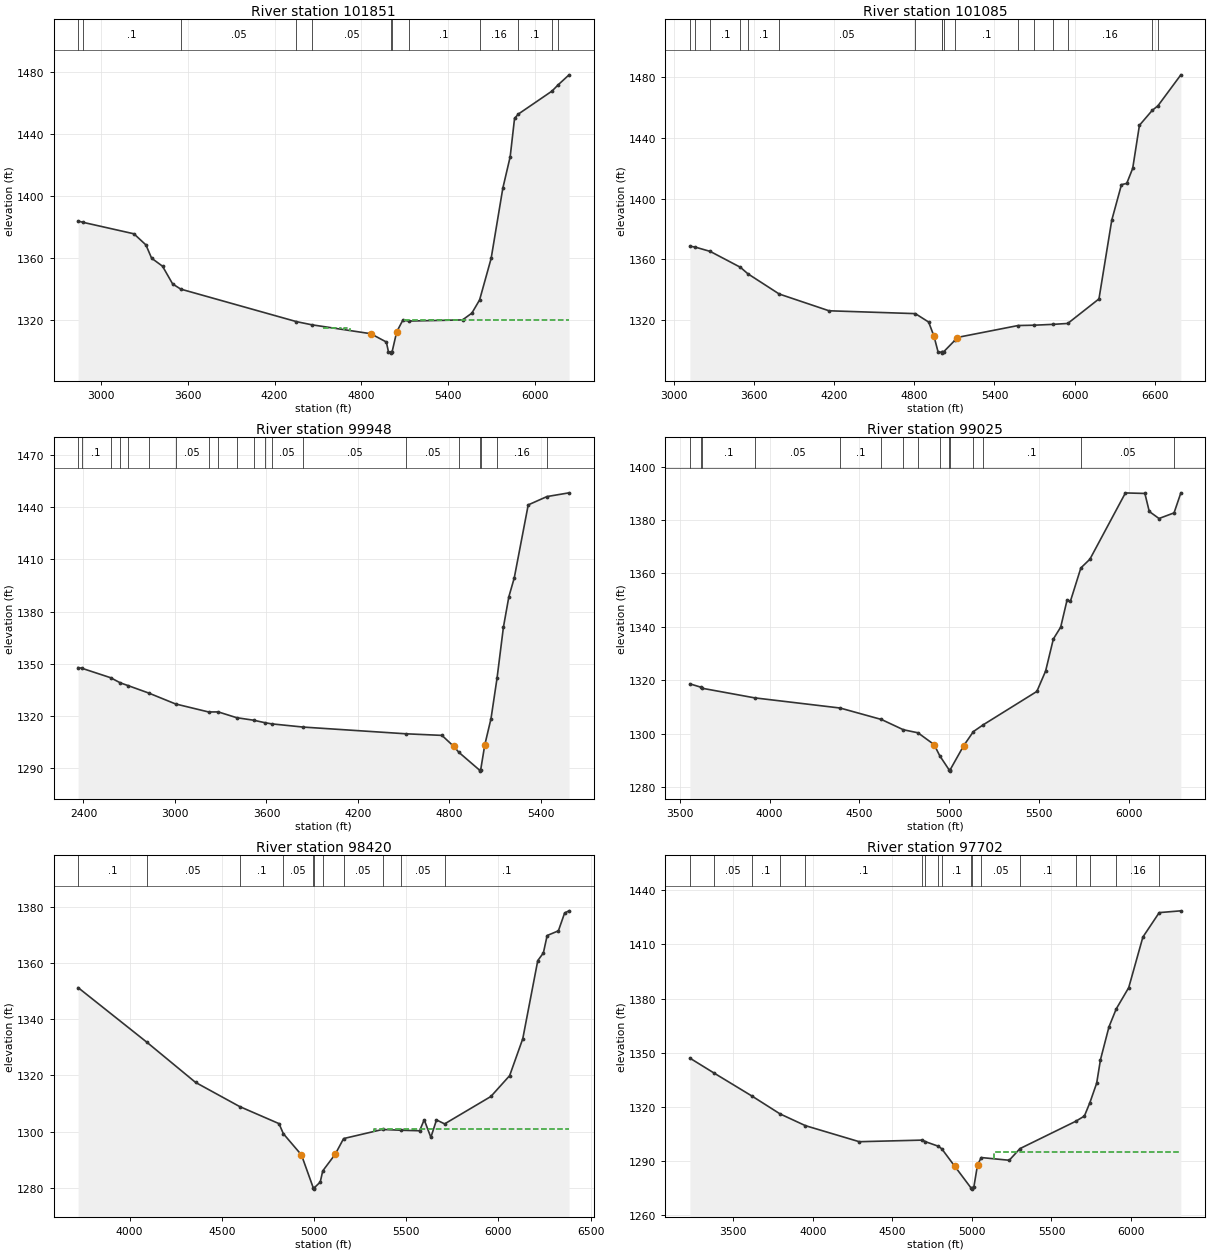
Type RM Length L Ch R = 1 ,101851  ,766,766,766
BEGIN DESCRIPTION:
MILLER CREEK 162.0
END DESCRIPTION:
XS GIS Cut Line= 4
      2903578.28     10043972.42      2904251.88     10042444.66
       2904661.6     10041847.44      2904515.76     10040861.29
#Sta/Elev= 30
  2843.1 1383.72  2880.1 1382.85  3228.7 1375.49  3311.6  1368.3  3350.8 1359.73
  3426.2 1354.54  3496.2 1343.05  3552.3 1339.72  4351.1 1318.71  4456.6 1316.67
  4864.3  1310.9  4971.9 1305.53  4986.8 1299.09  5004.8 1298.84  5007.5 1298.34
  5010.8 1298.84  5043.6 1312.12  5085.6  1319.6  5125.3 1319.08  5498.1 1319.81
  5562.6 1324.21    5616 1332.74  5695.7 1359.57  5776.5 1405.02  5827.1 1425.26
  5857.4  1450.1  5883.7 1452.92  6115.8 1467.76  6159.5  1471.9  6233.9 1478.28
#Mann= 12 ,-1 , 0
  2843.1     .05       0  2880.1      .1       0  3552.3     .05       0
  4351.1      .1       0  4456.6     .05       0  5004.8    .035       0
  5010.8     .05       0  5125.3      .1       0    5616     .16       0
  5883.7      .1       0  6115.8     .05       0  6159.5      .1       0
#XS Ineff= 4 ,-1
 4492.21 4531.41 1315.57 4533.08 4655.71 1314.85  4677.4 4719.94 1314.85
 5095.33  6233.9 1320.05
Permanent Ineff=
       T       T       T       T
Bank Sta=4864.3,5043.6
XS Rating Curve= 0 ,0
Exp/Cntr=0.3,0.1

Type RM Length L Ch R = 1 ,101085  ,1137,1137,1137
BEGIN DESCRIPTION:
MILLER CREEK 161.0
END DESCRIPTION:
XS GIS Cut Line= 4
      2904411.58     10044111.37      2905140.77     10042944.66
      2905133.82     10041972.44      2904543.54     10040784.94
#Sta/Elev= 30
  3120.8 1368.71  3159.5 1368.13  3272.5 1365.29  3498.5 1354.87  3554.9 1350.58
  3789.4  1337.3  4161.9  1326.3  4808.2 1324.43  4907.6  1318.9  4947.6 1309.56
  4977.6 1299.45  5004.6    1299  5007.3  1298.5  5010.6    1299    5020 1299.39
  5103.4 1306.87  5117.6 1308.72  5576.9 1316.62  5696.2 1316.83  5837.6 1317.39
  5948.4 1317.98  6182.1  1334.1  6277.8 1385.75  6350.5 1409.12  6389.8 1409.89
  6434.6 1419.82  6484.9 1448.06  6580.9 1457.89  6623.1 1460.84    6795  1481.2
#Mann= 17 ,-1 , 0
  3120.8      .1       0  3159.5     .05       0  3272.5      .1       0
  3498.5     .05       0  3554.9      .1       0  3789.4     .05       0
  4808.2      .1       0  5004.6     .07       0  5010.6      .1       0
    5020     .05       0  5103.4      .1       0  5576.9     .05       0
  5696.2      .1       0  5837.6     .05       0  5948.4     .16       0
  6580.9      .1       0  6623.1     .05       0
Bank Sta=4947.6,5117.6
XS Rating Curve= 0 ,0
Exp/Cntr=0.3,0.1

Type RM Length L Ch R = 1 ,99948   ,923,923,923
BEGIN DESCRIPTION:
MILLER CREEK 159.0
END DESCRIPTION:
XS GIS Cut Line= 3
      2904841.92      10044184.4      2905939.12     10042608.05
      2906175.23     10041330.29
#Sta/Elev= 30
  2364.6 1347.81  2387.9 1347.46  2577.7 1341.99  2641.5 1339.03  2692.1 1337.46
    2827  1333.2  3003.6 1326.91  3220.4  1322.3    3284 1322.33  3404.4 1319.01
  3516.8 1317.54  3588.4 1316.16  3633.2 1315.47  3840.2 1313.62  4517.5 1309.74
  4750.9 1308.84  4828.6 1302.49  4861.8 1299.11  4998.5  1288.8  5001.2  1288.3
  5004.5  1288.8    5032 1303.47  5072.6 1318.44  5112.2 1341.68    5154    1371
  5189.6 1388.47  5225.2 1399.37  5316.7  1441.3  5439.6 1446.08  5584.6 1448.23
#Mann= 20 ,-1 , 0
  2364.6     .05       0  2387.9      .1       0  2577.7     .05       0
  2641.5      .1       0  2692.1     .05       0    2827      .1       0
  3003.6     .05       0  3220.4      .1       0    3284     .05       0
  3404.4      .1       0  3516.8     .05       0  3588.4      .1       0
  3633.2     .05       0  3840.2     .05       0  4517.5     .05       0
  4861.8      .1       0  4998.5     .07       0  5004.5      .1       0
  5112.2     .16       0  5439.6      .1       0
Bank Sta=4828.6,5032
XS Rating Curve= 0 ,0
Exp/Cntr=0.3,0.1

Type RM Length L Ch R = 1 ,99025   ,605,605,605
BEGIN DESCRIPTION:
MILLER CREEK 158.0
END DESCRIPTION:
XS GIS Cut Line= 4
       2905529.4     10043392.77      2906508.56      10042788.6
       2906841.9     10042364.99      2906459.97     10041392.81
#Sta/Elev= 30
  3556.6 1318.61  3616.1 1317.39  3624.6 1316.96    3917 1313.36  4393.1 1309.55
  4623.2 1305.26  4745.5 1301.41  4826.7 1300.27  4916.9 1295.83  4947.8 1291.69
  4999.9 1286.41  5002.7 1285.91  5005.9 1286.41  5081.5 1295.47  5135.5 1300.74
    5190 1303.26  5488.7 1315.76  5537.5  1323.4  5580.6 1335.41  5621.5 1339.86
  5656.7 1349.93  5675.7 1349.57  5733.8 1362.03  5784.1  1365.3  5981.9 1390.13
  6090.3 1389.94  6114.7 1383.19    6169 1380.55  6252.8 1382.66  6290.7 1390.17
#Mann= 15 ,-1 , 0
  3556.6      .1       0  3616.1     .05       0  3624.6      .1       0
    3917     .05       0  4393.1      .1       0  4623.2     .05       0
  4745.5      .1       0  4826.7     .05       0  4947.8      .1       0
  4999.9     .07       0  5005.9      .1       0  5135.5     .05       0
    5190      .1       0  5733.8     .05       0  6252.8      .1       0
Bank Sta=4916.9,5081.5
XS Rating Curve= 0 ,0
Exp/Cntr=0.3,0.1

Type RM Length L Ch R = 1 ,98420   ,718,718,718
BEGIN DESCRIPTION:
MILLER CREEK 157.0
END DESCRIPTION:
XS GIS Cut Line= 3
      2907008.83     10044166.85      2907133.82     10043055.77
      2907418.19     10041536.84
#Sta/Elev= 30
  3720.2 1351.26  4092.8 1331.83  4357.3  1317.5  4596.7 1308.89  4810.1 1302.81
  4833.6 1299.23  4931.9 1291.66  4995.7 1279.98  4998.5 1279.48  5001.7 1279.98
  5033.7 1281.99  5047.5 1285.99    5115  1291.9  5160.6 1297.49  5371.6 1300.73
  5470.2 1300.46  5572.9 1300.27  5597.7 1304.18  5633.9 1297.92  5664.4 1304.13
  5708.5 1302.72  5959.5 1312.48  6061.2  1319.9  6132.4 1333.04  6213.8 1360.88
  6244.2 1363.61  6264.7 1369.81  6325.7 1371.49  6359.6 1377.86  6383.6 1378.61
#Mann= 11 ,-1 , 0
  3720.2      .1       0  4092.8     .05       0  4596.7      .1       0
  4833.6     .05       0  4995.7    .035       0  5001.7     .05       0
  5047.5      .1       0  5160.6     .05       0  5371.6      .1       0
  5470.2     .05       0  5708.5      .1       0
#XS Ineff= 2 , 0
                         5324.48         1300.91
Permanent Ineff=
       T       T
Bank Sta=4931.9,5115
XS Rating Curve= 0 ,0
Exp/Cntr=0.3,0.1

Type RM Length L Ch R = 1 ,97702   ,715,715,715
BEGIN DESCRIPTION:
MILLER CREEK 156.0
END DESCRIPTION:
XS GIS Cut Line= 4
      2907453.27     10044159.91       2907849.1       10042653.
      2907383.82     10042048.83      2907675.48     10041340.53
#Sta/Elev= 30
  3226.8 1346.93  3379.6  1338.6  3616.5 1325.91  3794.1 1315.95  3953.4 1309.44
  4291.6 1300.54  4688.7 1301.43  4707.9 1300.55  4788.5 1298.03  4810.3 1296.61
  4891.8 1286.92  4995.5 1274.72  4998.2 1274.22  5001.5 1274.72  5012.3 1275.56
    5035 1287.61  5058.4 1291.75  5234.3 1290.24  5301.9 1296.71  5651.6 1311.84
  5706.9 1314.78  5741.6 1322.26  5784.1 1333.04  5808.1 1346.11  5861.4 1364.28
    5907 1374.24  5985.5 1386.05  6074.6 1414.13  6177.3  1427.7  6313.4 1428.69
#Mann= 17 ,-1 , 0
  3226.8      .1       0  3379.6     .05       0  3616.5      .1       0
  3794.1     .05       0  3953.4      .1       0  4688.7     .05       0
  4707.9      .1       0  4788.5     .05       0  4810.3      .1       0
  4995.5     .07       0  5001.5      .1       0  5058.4     .05       0
  5301.9      .1       0  5651.6     .05       0  5741.6      .1       0
    5907     .16       0  6177.3      .1       0
#XS Ineff= 2 , 0
                         5139.77         1294.69
Permanent Ineff=
       T       T
Bank Sta=4891.8,5035
XS Rating Curve= 0 ,0
Exp/Cntr=0.3,0.1

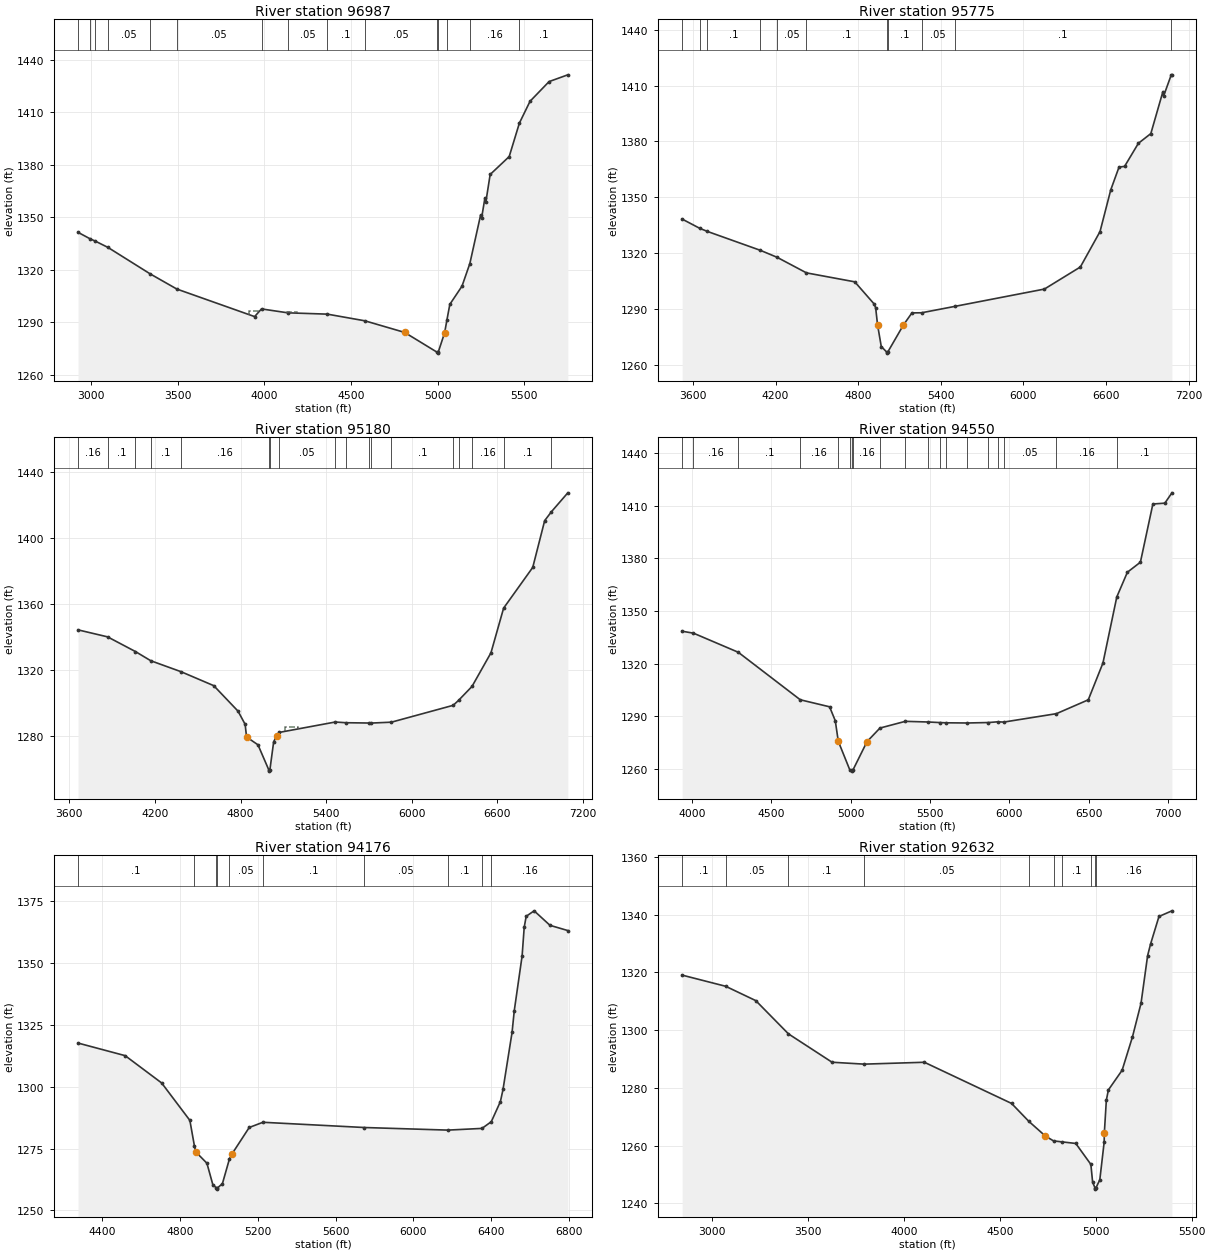
Type RM Length L Ch R = 1 ,96987   ,1212,1212,1212
BEGIN DESCRIPTION:
MILLER CREEK 154.0
END DESCRIPTION:
XS GIS Cut Line= 4
      2907640.75     10044083.59      2908307.43     10042368.27
      2908342.16     10041909.94        2908155.     10041417.79
#Sta/Elev= 30
  2924.1 1341.39  2992.9 1337.73  3023.9 1336.35  3096.7 1332.76  3340.4 1317.61
  3494.4 1308.92  3943.2 1293.15  3982.9 1297.55  4134.8 1295.31  4362.7 1294.56
  4579.5 1290.74  4809.1 1284.09  4996.6 1272.74  4999.4 1272.24  5002.6 1272.74
  5039.8 1283.93  5053.1  1291.3  5069.8 1300.18    5140 1310.59  5185.3 1323.54
  5247.6  1351.4    5253 1349.49  5272.4  1361.2  5277.8 1358.88  5302.5 1374.51
  5412.3 1384.76  5471.1 1403.91  5532.7 1416.43  5642.5 1427.69  5750.6 1431.56
#Mann= 15 ,-1 , 0
  2924.1      .1       0  2992.9     .05       0  3023.9     .16       0
  3096.7     .05       0  3340.4      .1       0  3494.4     .05       0
  3982.9      .1       0  4134.8     .05       0  4362.7      .1       0
  4579.5     .05       0  4996.6     .04       0  5002.6     .05       0
  5053.1      .1       0  5185.3     .16       0  5471.1      .1       0
#XS Ineff= 3 ,-1
 3911.38 3975.33 1296.34 4128.95 4189.91 1295.77 4221.59 4264.03 1294.13
Permanent Ineff=
       T       T       T
Bank Sta=4809.1,5039.8
XS Rating Curve= 0 ,0
Exp/Cntr=0.3,0.1

Type RM Length L Ch R = 1 ,95775   ,595,595,595
BEGIN DESCRIPTION:
MILLER CREEK 152.0
END DESCRIPTION:
XS GIS Cut Line= 4
      2909224.11     10044486.36      2908835.21     10043430.77
      2909071.32     10041979.38      2908987.99     10041021.01
#Sta/Elev= 30
  3521.7 1338.24  3647.9 1333.33  3704.6 1331.61  4090.5 1321.42  4210.9 1317.71
  4424.8 1309.32  4775.4 1304.51  4917.2 1292.52  4927.3  1290.5 4940.91 1281.43
  4967.9 1269.75  5008.4 1266.69  5011.2 1266.19  5014.4 1266.69  5129.4 1281.38
  5190.7 1287.81  5260.8 1287.88  5501.5  1291.3  6152.9 1300.62  6413.9 1312.48
  6556.8 1331.52  6634.7 1353.92  6694.9  1366.2  6735.1 1366.55  6835.5 1378.97
  6925.8 1384.18  7013.5 1406.73  7018.5 1404.34  7073.1 1415.53  7079.1 1415.77
#Mann= 11 ,-1 , 0
  3521.7      .1       0  3647.9     .16       0  3704.6      .1       0
  4090.5     .16       0  4210.9     .05       0  4424.8      .1       0
  5008.4     .07       0  5014.4      .1       0  5260.8     .05       0
  5501.5      .1       0  7073.1     .16       0
Bank Sta=4940.91,5129.4
XS Rating Curve= 0 ,0
Exp/Cntr=0.3,0.1

Type RM Length L Ch R = 1 ,95180   ,630,630,630
BEGIN DESCRIPTION:
MILLER CREEK 151.0
END DESCRIPTION:
XS GIS Cut Line= 4
      2909696.31     10044277.96      2909446.32     10043639.11
       2909474.1       10042403.      2909029.69     10040958.66
#Sta/Elev= 30
  3660.7 1344.48  3867.8 1340.24  4063.3 1331.33  4170.8 1325.76  4382.3 1319.14
  4612.2 1310.66  4782.2 1295.23  4832.2 1287.23  4842.2 1279.53  4922.2 1274.81
  4999.3 1259.36    5002 1258.86  5005.3 1259.36  5032.3  1276.7  5052.3 1279.94
  5070.4 1282.31  5463.6 1288.62  5538.8  1288.2  5698.2 1288.02  5714.9 1287.98
  5857.6 1288.53  6290.5 1298.74    6328 1301.71  6422.7  1310.2  6555.4 1330.55
  6644.2 1357.65  6848.5 1382.34  6932.1 1410.69  6979.7 1416.11  7094.3 1427.54
#Mann= 18 ,-1 , 0
  3660.7     .16       0  3867.8      .1       0  4063.3     .05       0
  4170.8      .1       0  4382.3     .16       0  4999.3     .07       0
  5005.3     .16       0  5070.4     .05       0  5463.6      .1       0
  5538.8     .05       0  5698.2      .1       0  5714.9     .05       0
  5857.6      .1       0  6290.5     .16       0    6328      .1       0
  6422.7     .16       0  6644.2      .1       0  6979.7     .16       0
#XS Ineff= 1 ,-1
 5112.17 5202.48 1285.71
Permanent Ineff=
       T
Bank Sta=4842.2,5052.3
XS Rating Curve= 0 ,0
Exp/Cntr=0.3,0.1

Type RM Length L Ch R = 1 ,94550   ,374,374,374
BEGIN DESCRIPTION:
MILLER CREEK 150.0
END DESCRIPTION:
XS GIS Cut Line= 4
      2910404.66     10043812.71      2910307.43      10043215.5
      2909543.55     10042104.38      2909286.61     10041000.23
#Sta/Elev= 30
  3937.3 1338.44  4008.8 1337.33    4291 1326.46  4681.8 1299.41  4866.6 1295.41
  4902.5 1287.46  4921.4 1275.78  4993.5 1259.61    5007 1259.28  5009.8 1258.78
    5013 1259.28  5102.7  1275.6    5184  1283.3  5343.9 1287.13  5487.3 1286.76
  5561.6 1286.43  5601.8  1286.3  5733.1 1286.19  5867.7 1286.45  5928.6 1286.88
  5963.9  1286.7  6296.4  1291.5  6497.2 1299.39  6589.6 1320.35  6676.9 1357.97
  6743.6 1372.03  6825.7 1377.75  6904.3 1410.89  6979.7 1411.37  7024.4 1417.25
#Mann= 19 ,-1 , 0
  3937.3     .05       0  4008.8     .16       0    4291      .1       0
  4681.8     .16       0  4921.4      .1       0  4993.5     .16       0
    5007     .07       0    5013     .16       0    5184     .05       0
  5343.9      .1       0  5487.3     .05       0  5561.6      .1       0
  5601.8     .05       0  5733.1      .1       0  5867.7     .05       0
  5928.6      .1       0  5963.9     .05       0  6296.4     .16       0
  6676.9      .1       0
Bank Sta=4921.4,5102.7
XS Rating Curve= 0 ,0
Exp/Cntr=0.3,0.1

Type RM Length L Ch R = 1 ,94176   ,1544,1544,1544
BEGIN DESCRIPTION:
MILLER CREEK 149.0
END DESCRIPTION:
XS GIS Cut Line= 4
      2910460.21     10043152.96      2910446.32     10042659.94
      2909967.16     10042347.44      2909689.39     10040923.87
#Sta/Elev= 30
  4277.3 1317.54  4519.3 1312.46  4706.7 1301.45  4851.7 1286.35  4875.3 1275.96
    4882 1273.64  4939.3 1269.06  4969.5 1260.47  4987.6 1259.11  4990.4 1258.61
  4993.6 1259.11  5018.7 1260.77  5055.1 1270.81    5069 1272.91  5156.6 1283.48
    5227 1285.58  5747.3 1283.47  6177.3 1282.42  6352.3 1283.11    6400 1285.82
  6446.7 1293.91  6460.2 1298.83  6506.7 1321.87    6518 1330.61  6558.3 1352.71
    6569 1364.22  6579.2 1368.68    6620 1370.89  6701.4 1365.04    6793 1362.93
#Mann= 10 ,-1 , 0
  4277.3      .1       0  4875.3     .16       0  4987.6     .07       0
  4993.6     .16       0  5055.1     .05       0    5227      .1       0
  5747.3     .05       0  6177.3      .1       0  6352.3     .05       0
    6400     .16       0
#XS Ineff= 2 , 0
                         5261.36         1285.21
Permanent Ineff=
       T       T
Bank Sta=4882,5069
XS Rating Curve= 0 ,0
Exp/Cntr=0.3,0.1

Type RM Length L Ch R = 1 ,92632   ,739,739,739
BEGIN DESCRIPTION:
MILLER CREEK 146.0
END DESCRIPTION:
XS GIS Cut Line= 3
      2910515.76     10043208.59      2910862.99     10041548.83
      2910460.22     10040791.91
#Sta/Elev= 30
  2844.1 1319.09  3070.8 1315.23  3227.9 1310.26  3398.3 1298.74  3625.5 1288.92
  3792.6 1288.26  4106.7 1288.91  4561.3 1274.65  4650.9 1268.47  4738.1 1263.32
  4780.1 1261.68  4824.7 1261.33  4895.9 1260.79  4974.6 1253.54  4983.8 1247.39
  4995.7 1245.47  4998.4 1244.97  5001.7 1245.47  5021.3 1248.23    5044 1261.26
 5044.89 1264.48  5055.3 1275.78    5066 1279.33  5137.6 1286.15  5191.2 1297.64
  5236.1 1309.34  5270.5 1325.86  5285.7 1329.83  5329.6  1339.4  5397.2 1341.36
#Mann= 10 ,-1 , 0
  2844.1      .1       0  3070.8     .05       0  3398.3      .1       0
  3792.6     .05       0  4650.9      .1       0  4780.1     .05       0
  4824.7      .1       0  4974.6     .16       0  4995.7     .07       0
  5001.7     .16       0
Bank Sta=4738.1,5044.89
XS Rating Curve= 0 ,0
Exp/Cntr=0.3,0.1

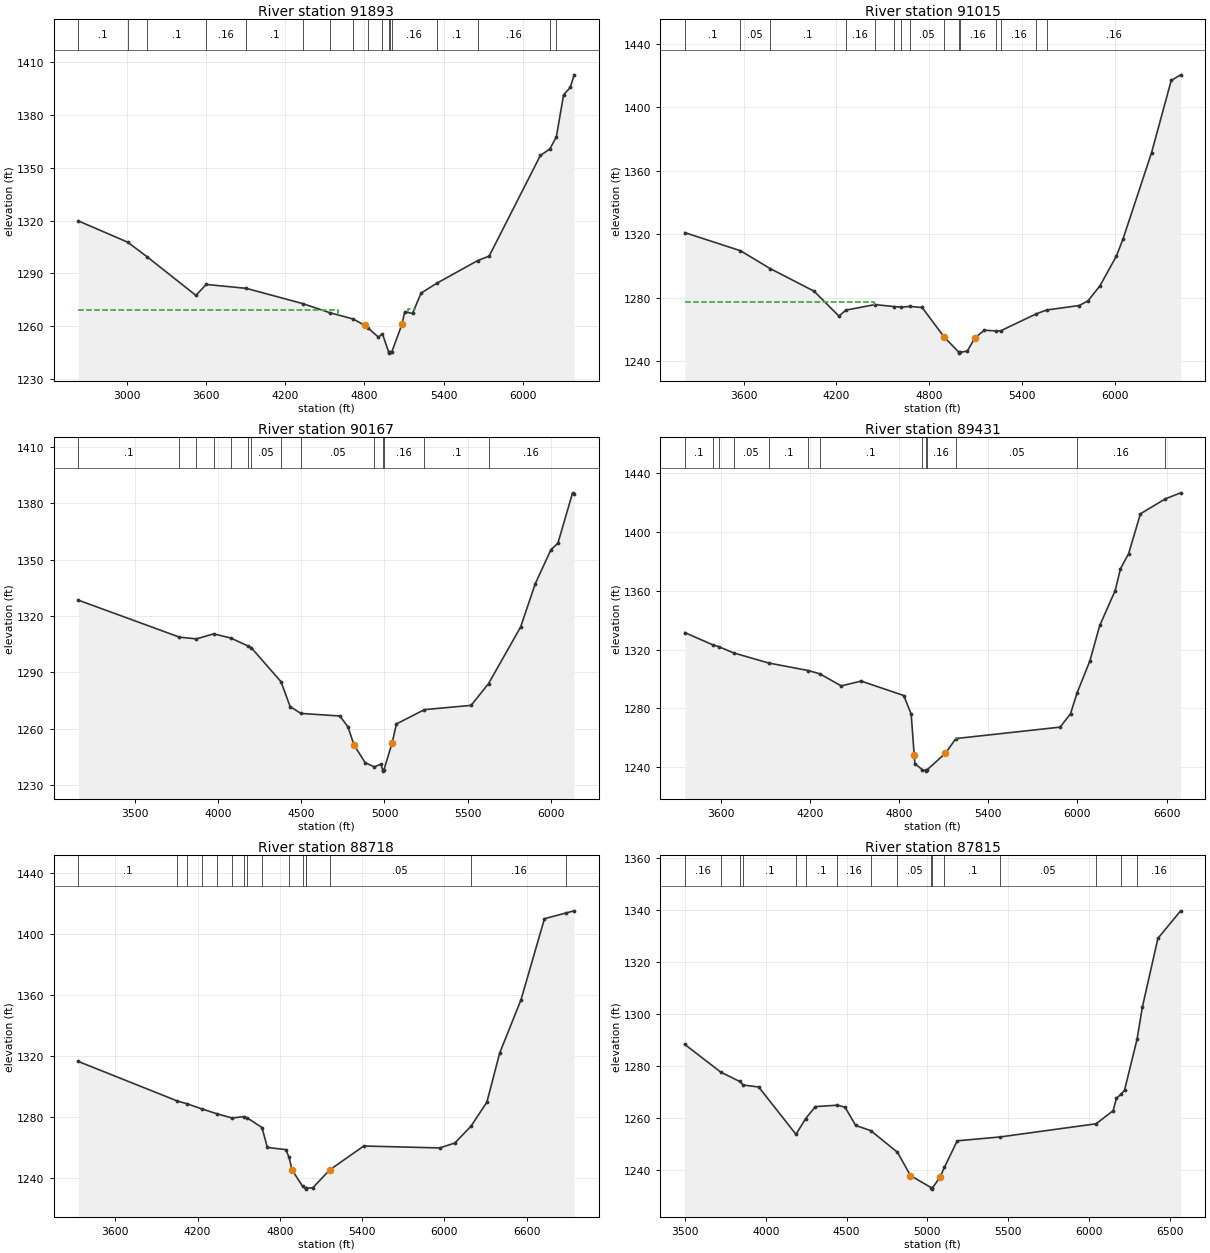
Type RM Length L Ch R = 1 ,91893   ,878,878,878
BEGIN DESCRIPTION:
MILLER CREEK 145.0
END DESCRIPTION:
XS GIS Cut Line= 3
      2910592.16     10043215.49      2911182.43      10041215.5
       2912008.8     10039764.15
#Sta/Elev= 30
    2634 1319.78  3007.5 1307.68  3155.8  1299.3  3524.5 1277.39  3602.3 1283.61
  3906.1 1281.39    4334  1272.7  4537.8 1267.55  4716.4 1263.92  4804.9 1260.25
  4826.7 1258.89  4907.2 1253.62  4937.2 1255.52  4984.9 1245.02  4987.7 1244.52
  4990.9 1245.02  5008.7 1245.29  5084.5 1260.83  5106.1 1267.97  5165.2 1267.11
    5230 1278.69  5348.3 1284.27  5658.3 1297.18  5745.5 1299.73  6133.5 1357.03
  6205.5 1360.72  6254.6 1367.65  6309.3 1391.53  6359.8 1395.72  6389.4 1402.92
#Mann= 17 ,-1 , 0
    2634      .1       0  3007.5     .05       0  3155.8      .1       0
  3602.3     .16       0  3906.1      .1       0    4334     .05       0
  4537.8      .1       0  4716.4     .05       0  4826.7     .16       0
  4937.2     .05       0  4984.9    .035       0  4990.9     .05       0
  5008.7     .16       0  5348.3      .1       0  5658.3     .16       0
  6205.5      .1       0  6254.6     .16       0
#XS Ineff= 2 ,-1
    2634 4599.43 1269.06 5127.76 5191.52 1269.39
Permanent Ineff=
       T       T
Bank Sta=4804.9,5084.5
XS Rating Curve= 0 ,0
Exp/Cntr=0.3,0.1

Type RM Length L Ch R = 1 ,91015   ,848,848,848
BEGIN DESCRIPTION:
MILLER CREEK 144.0
END DESCRIPTION:
XS GIS Cut Line= 4
      2910619.93     10043264.11       2911161.6     10041847.44
      2911842.16       10041778.      2912508.52     10041028.33
#Sta/Elev= 30
  3220.2 1320.94  3579.6 1309.54  3771.6  1298.3  4055.7 1284.03  4216.3 1268.33
  4260.8  1272.1  4448.4  1275.6  4571.6 1274.36  4614.9    1274  4675.3 1274.43
  4753.8 1273.77    4897 1255.03  4992.1 1245.52  4994.8 1245.02  4998.1 1245.52
  5045.4  1246.3  5095.6 1254.73  5155.9 1259.46  5231.9    1259  5260.3 1259.03
  5491.1 1269.77  5558.5  1272.2  5768.5 1275.01  5825.4 1277.94  5903.1 1287.49
  6009.3 1306.21    6052    1317    6236 1371.24  6363.3 1416.77    6424 1420.34
#Mann= 15 ,-1 , 0
  3220.2      .1       0  3579.6     .05       0  3771.6      .1       0
  4260.8     .16       0  4448.4      .1       0  4571.6     .05       0
  4614.9      .1       0  4675.3     .05       0    4897     .16       0
  4992.1     .07       0  4998.1     .16       0  5231.9      .1       0
  5260.3     .16       0  5491.1      .1       0  5558.5     .16       0
#XS Ineff= 2 , 0
         4445.74 1276.97
Permanent Ineff=
       T       T
Bank Sta=4897,5095.6
XS Rating Curve= 0 ,0
Exp/Cntr=0.3,0.1

Type RM Length L Ch R = 1 ,90167   ,736,736,736
BEGIN DESCRIPTION:
MILLER CREEK 141.0
END DESCRIPTION:
XS GIS Cut Line= 3
      2911335.22     10043875.21      2911737.99       10042653.
       2912647.7      10041229.4
#Sta/Elev= 30
  3162.5 1328.43  3769.7 1308.72  3871.8 1307.79  3973.9 1310.47  4076.1  1308.3
  4178.2 1304.16  4199.9 1303.19  4379.2 1284.97  4433.9 1271.75  4498.2  1268.1
  4732.7 1266.72    4781 1260.92  4817.4 1251.29  4884.2 1241.86  4938.8 1239.63
  4978.1 1241.01  4990.3 1237.85    4993 1237.35  4996.3 1237.85 5046.31 1252.44
    5072 1262.49  5240.1 1270.12  5520.3 1272.37    5625 1284.01  5817.2 1314.09
  5905.2 1337.14  5999.1 1355.28  6041.4  1358.8  6129.3  1385.6  6138.8 1384.86
#Mann= 14 ,-1 , 0
  3162.5      .1       0  3769.7     .05       0  3871.8      .1       0
  3973.9     .05       0  4076.1      .1       0  4178.2     .16       0
  4199.9     .05       0  4379.2     .16       0  4498.2     .05       0
  4938.8     .16       0  4990.3     .07       0  4996.3     .16       0
  5240.1      .1       0    5625     .16       0
Bank Sta=4817.4,5046.31
XS Rating Curve= 0 ,0
Exp/Cntr=0.3,0.1

Type RM Length L Ch R = 1 ,89431   ,713,713,713
BEGIN DESCRIPTION:
MILLER CREEK 140.0
END DESCRIPTION:
XS GIS Cut Line= 3
      2912293.55     10044146.02      2912633.82     10042771.05
      2912772.71     10040854.43
#Sta/Elev= 30
  3356.9 1331.65  3547.5 1323.22  3585.9 1322.07  3686.1  1317.8  3922.4 1310.92
  4187.5 1305.84  4266.4 1303.58    4410 1295.36    4544 1298.64  4830.8 1288.82
    4881 1276.24    4901 1248.58  4906.4 1242.42  4956.1  1238.3  4978.2 1237.85
    4981 1237.35  4984.2 1237.85  5111.6 1249.55  5182.1 1259.53  5883.6  1267.3
  5953.8 1276.42  5996.8  1290.3  6084.1  1312.4  6150.6 1336.52  6254.5 1360.27
    6290 1375.08  6344.8 1385.37  6424.4  1412.5  6592.1 1422.67    6695 1426.77
#Mann= 13 ,-1 , 0
  3356.9      .1       0  3547.5     .05       0  3585.9      .1       0
  3686.1     .05       0  3922.4      .1       0  4187.5     .05       0
  4266.4      .1       0  4956.1     .16       0  4978.2     .07       0
  4984.2     .16       0  5182.1     .05       0  5996.8     .16       0
  6592.1      .1       0
#XS Ineff= 1 ,-1
 5180.27 5192.29 1259.65
Permanent Ineff=
       T
Bank Sta=4901,5111.6
XS Rating Curve= 0 ,0
Exp/Cntr=0.3,0.1

Type RM Length L Ch R = 1 ,88718   ,903,903,903
BEGIN DESCRIPTION:
MILLER CREEK 139.0
END DESCRIPTION:
XS GIS Cut Line= 4
      2912675.47     10044062.75      2913307.43     10042882.16
      2913418.55     10041687.72      2913307.45     10040618.46
#Sta/Elev= 30
  3331.3 1316.42  4052.5 1290.57  4124.5 1288.71  4233.6 1285.32  4342.7 1282.14
  4451.8 1279.43  4536.3 1280.32  4560.9 1279.59  4669.9 1273.19    4709 1260.15
    4844 1258.73  4866.8 1253.69  4889.8 1245.32  4965.2 1234.79  4987.2 1233.39
  4989.9 1232.89  4993.2 1233.39  5040.4 1233.83    5162  1245.3  5166.7 1245.69
    5412 1261.11  5964.5 1259.84  6075.1 1263.05  6192.8 1274.03  6308.8 1289.78
  6402.4 1321.99  6557.7  1356.8  6728.6 1409.83  6887.8 1413.63    6945 1414.98
#Mann= 16 ,-1 , 0
  3331.3      .1       0  4052.5     .05       0  4124.5      .1       0
  4233.6     .16       0  4342.7     .05       0  4451.8      .1       0
  4536.3     .16       0  4560.9      .1       0  4669.9     .16       0
  4866.8     .05       0  4965.2     .16       0  4987.2     .07       0
  4993.2     .16       0    5162     .05       0  6192.8     .16       0
  6887.8      .1       0
Bank Sta=4889.8,5166.7
XS Rating Curve= 0 ,0
Exp/Cntr=0.3,0.1

Type RM Length L Ch R = 1 ,87815   ,556,556,556
BEGIN DESCRIPTION:
MILLER CREEK 138.0
END DESCRIPTION:
XS GIS Cut Line= 4
      2913128.59      10043566.2      2914040.07     10043050.56
      2914336.95     10042279.73      2914446.24     10041087.88
#Sta/Elev= 30
  3498.3 1288.46  3722.1 1277.77  3838.2 1274.23  3860.9 1272.85  3956.1 1272.09
  4186.7  1253.9  4246.6 1259.95  4306.8 1264.56  4442.4  1265.1  4490.1 1264.35
  4556.6 1257.32  4650.1 1255.31  4815.2    1247  4895.8 1238.06  5025.8 1233.34
  5028.6 1232.84  5031.8 1233.34  5077.9 1237.33  5105.9 1241.22  5185.1 1251.41
  5451.3  1252.9    6045 1257.96  6150.8 1263.01  6170.9  1267.8  6200.6 1269.36
  6221.1 1270.87    6299 1290.56  6331.6 1302.84  6427.7 1329.22  6568.4 1339.81
#Mann= 16 ,-1 , 0
  3498.3     .16       0  3722.1      .1       0  3838.2     .16       0
  3860.9      .1       0  4186.7     .05       0  4246.6      .1       0
  4442.4     .16       0  4650.1      .1       0  4815.2     .05       0
  5025.8     .04       0  5031.8     .05       0  5105.9      .1       0
  5451.3     .05       0    6045     .16       0  6200.6     .05       0
    6299     .16       0
Bank Sta=4895.8,5077.9
XS Rating Curve= 0 ,0
Exp/Cntr=0.3,0.1

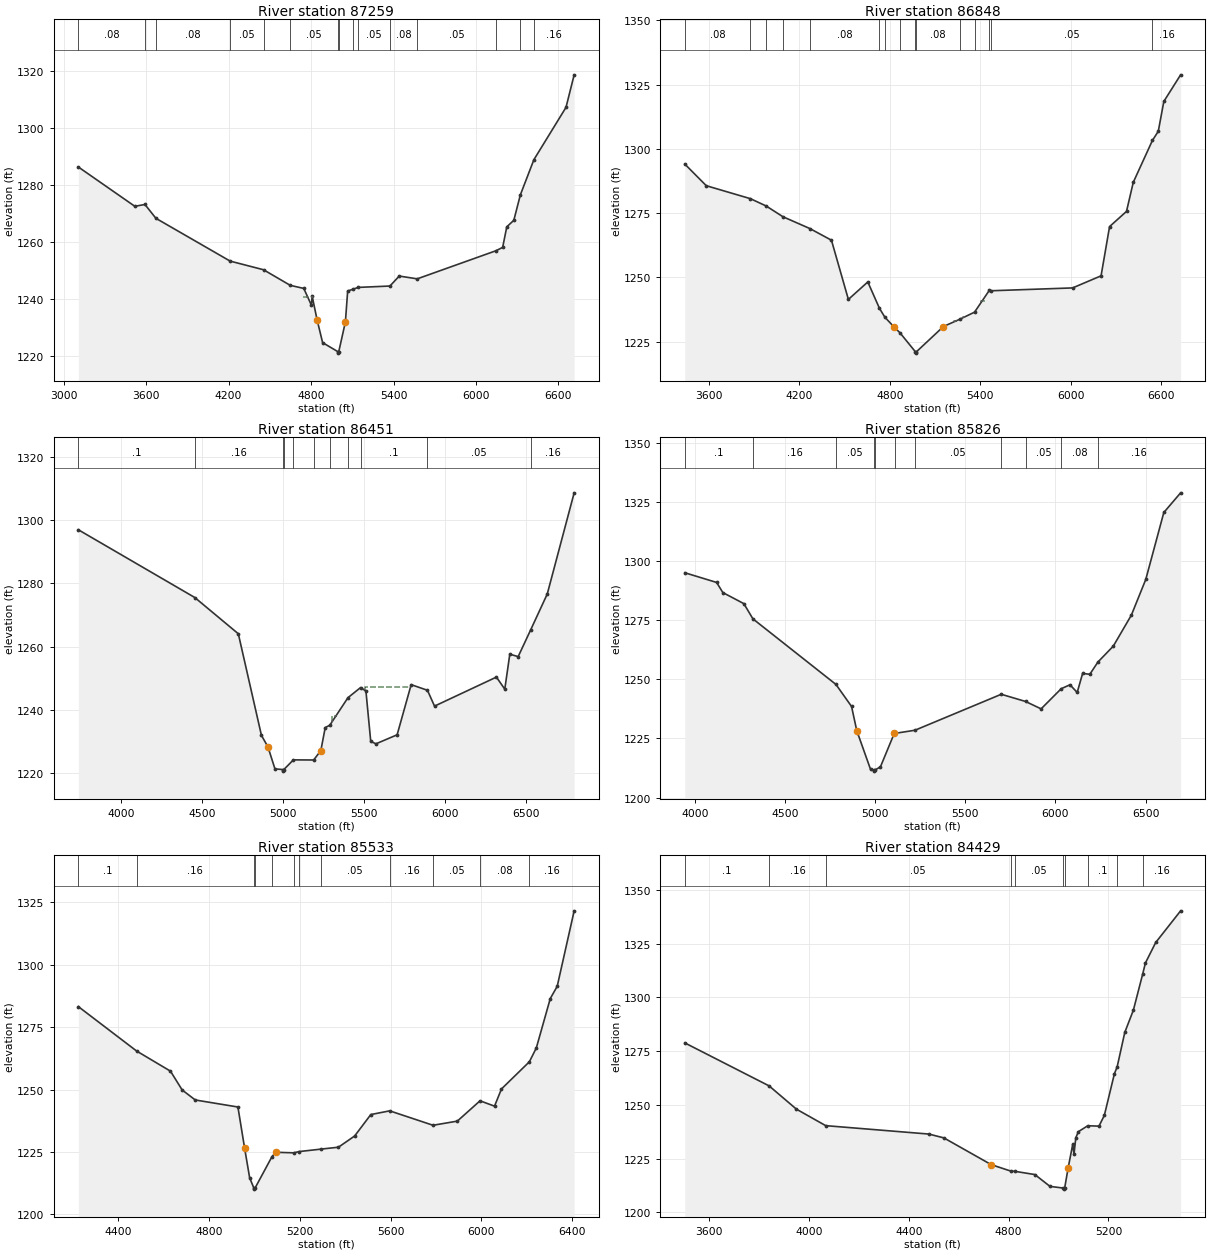
Type RM Length L Ch R = 1 ,87259   ,411,411,411
BEGIN DESCRIPTION:
MILLER CREEK 137.0
END DESCRIPTION:
XS GIS Cut Line= 4
      2914279.66     10044842.22      2914576.53     10043212.02
      2914701.53     10042435.98      2914769.24      10041274.5
#Sta/Elev= 30
  3107.4 1286.34  3518.4 1272.55    3592 1273.19  3671.6 1268.34  4211.7 1253.33
  4454.4  1250.3    4649 1244.83  4747.4 1243.75  4803.1 1237.82  4808.1 1241.08
  4843.7  1232.8  4884.2 1224.74  4995.7 1221.56  4998.4 1221.06  5001.7 1221.56
    5050 1232.02  5066.5 1242.84  5105.2 1243.47  5142.7 1244.11    5374 1244.59
  5441.6 1248.09  5572.4 1247.11  6144.7 1256.96  6193.8 1258.14  6223.8 1265.35
    6275 1267.64  6322.7 1276.58    6421  1288.9  6654.6 1307.25  6713.9 1318.66
#Mann= 15 ,-1 , 0
  3107.4     .08       0    3592      .1       0  3671.6     .08       0
  4211.7     .05       0  4454.4     .08       0    4649     .05       0
  4995.7     .04       0  5001.7     .05       0  5105.2     .08       0
  5142.7     .05       0    5374     .08       0  5572.4     .05       0
  6144.7     .16       0  6322.7     .05       0    6421     .16       0
#XS Ineff= 1 ,-1
 4740.91 4811.36 1240.65
Permanent Ineff=
       T
Bank Sta=4843.7,5050
XS Rating Curve= 0 ,0
Exp/Cntr=0.3,0.1

Type RM Length L Ch R = 1 ,86848   ,397,397,397
BEGIN DESCRIPTION:
MILLER CREEK 136.0
END DESCRIPTION:
XS GIS Cut Line= 4
      2914545.27     10044837.06       2914805.7     10043534.94
      2914987.99     10042467.23      2915373.41     10041680.76
#Sta/Elev= 30
  3440.8 1294.07  3583.2 1285.65  3876.1  1280.6    3980 1277.77  4091.4 1273.58
  4269.8 1268.99    4413 1264.45  4525.2 1241.43    4654 1248.22  4731.1 1237.98
  4767.1 1234.51  4830.8 1230.53  4866.2 1228.52  4969.8 1221.04  4972.6 1220.54
  4975.8 1221.04  5155.4 1230.89  5262.5 1233.68  5361.5 1236.47  5460.6 1245.04
  5469.5 1244.79  6011.7  1245.9  6200.3  1250.6  6256.7 1269.75  6368.9 1275.66
  6413.9 1286.98  6540.6 1303.24  6579.6 1306.81  6616.4 1318.42  6727.7 1328.77
#Mann= 15 ,-1 , 0
  3440.8     .08       0  3876.1      .1       0    3980     .08       0
  4091.4      .1       0  4269.8     .08       0  4731.1     .05       0
  4767.1     .16       0  4866.2     .08       0  4969.8     .07       0
  4975.8     .08       0  5262.5     .05       0  5361.5      .1       0
  5460.6     .08       0  5469.5     .05       0  6540.6     .16       0
#XS Ineff= 4 ,-1
  3440.8 4654.55 1247.78 5225.44 5247.81 1232.98 5286.59 5300.31 1234.45
 5406.51 5433.65 1240.64
Permanent Ineff=
       T       T       T       T
Bank Sta=4830.8,5155.4
XS Rating Curve= 0 ,0
Exp/Cntr=0.3,0.1

Type RM Length L Ch R = 1 ,86451   ,625,625,625
BEGIN DESCRIPTION:
MILLER CREEK 135.0
END DESCRIPTION:
XS GIS Cut Line= 4
      2914644.24     10044847.45      2914899.45     10044066.19
      2915034.87     10043368.27      2915415.08     10041889.08
#Sta/Elev= 30
  3734.4 1296.97  4453.1 1275.54  4721.8 1264.07  4864.4 1231.96  4905.1 1228.23
  4947.9 1221.34  4996.6 1221.13  4999.4 1220.63  5002.6 1221.13  5061.7 1224.19
  5186.8 1224.15  5231.1 1227.13  5258.2 1234.41  5286.4 1235.15  5398.5 1243.86
  5476.4 1247.06  5509.4 1245.94    5539 1230.04  5571.3 1229.27  5701.9 1232.12
  5788.6 1247.98  5889.1  1246.2  5932.7 1241.19  6314.7 1250.37  6366.4 1246.55
  6397.3 1257.61    6449 1256.85  6525.7 1265.26  6628.5 1276.65  6794.5 1308.65
#Mann= 11 ,-1 , 0
  3734.4      .1       0  4453.1     .16       0  4996.6     .07       0
  5002.6     .16       0  5061.7      .1       0  5186.8     .05       0
  5286.4      .1       0  5398.5     .05       0  5476.4      .1       0
  5889.1     .05       0  6525.7     .16       0
#XS Ineff= 3 ,-1
  5258.2 5286.73 1234.35 5299.03 5331.47 1238.21 5502.62 5786.19 1247.21
Permanent Ineff=
       T       T       T
Bank Sta=4905.1,5231.1
XS Rating Curve= 0 ,0
Exp/Cntr=0.3,0.1

Type RM Length L Ch R = 1 ,85826   ,293,293,293
BEGIN DESCRIPTION:
MILLER CREEK 134.0
END DESCRIPTION:
XS GIS Cut Line= 3
      2915956.76     10044436.02      2915420.28     10043222.44
      2915472.37     10041800.56
#Sta/Elev= 30
  3944.8 1295.19  4121.4 1291.08  4155.7  1286.8  4272.2 1282.11  4322.6 1275.66
  4782.9  1247.9  4869.6 1238.56  4898.5 1228.32    4975 1211.89  4994.1 1211.67
  4996.8 1211.17  5000.1 1211.67  5029.7 1212.98  5106.3 1227.13  5111.8 1227.18
  5221.4 1228.49  5699.8 1243.72  5834.3 1240.68  5920.8 1237.54  6032.1 1246.07
  6080.9 1247.74  6120.9 1244.49    6151 1252.55    6191 1252.19  6235.8 1257.37
  6321.1 1264.11  6421.1  1277.2  6501.2 1292.36  6601.3 1320.71  6694.5 1329.04
#Mann= 11 ,-1 , 0
  3944.8      .1       0  4322.6     .16       0  4782.9     .05       0
  4994.1    .035       0  5000.1     .05       0  5111.8      .1       0
  5221.4     .05       0  5699.8     .16       0  5834.3     .05       0
  6032.1     .08       0  6235.8     .16       0
Bank Sta=4898.5,5106.3
XS Rating Curve= 0 ,0
Exp/Cntr=0.3,0.1

Type RM Length L Ch R = 1 ,85533   ,1104,1104,1104
BEGIN DESCRIPTION:
MILLER CREEK 133.0
END DESCRIPTION:
XS GIS Cut Line= 3
      2916210.11     10044003.23       2915550.4     10042961.59
      2915758.74       10042031.
#Sta/Elev= 30
    4223  1283.2  4480.3  1265.4  4629.3 1257.36    4681 1249.82  4738.7 1245.82
  4926.8 1243.01  4956.3 1226.55  4978.5 1214.68  4996.7 1210.64  4999.5 1210.14
  5002.7 1210.64    5077 1223.14  5093.8 1224.89  5172.5 1224.67  5196.7 1225.17
  5291.7 1226.14  5370.1 1226.92  5441.6 1231.41  5512.9 1239.99  5596.2 1241.47
  5787.3  1235.7  5894.4 1237.36  5994.5 1245.49  6058.4 1243.35  6089.1 1250.24
  6212.1 1261.11  6242.8 1266.66  6304.3 1286.43  6334.8  1291.3  6409.6 1321.53
#Mann= 12 ,-1 , 0
    4223      .1       0  4480.3     .16       0  4996.7     .07       0
  5002.7     .16       0    5077      .1       0  5172.5     .05       0
  5196.7      .1       0  5291.7     .05       0  5596.2     .16       0
  5787.3     .05       0  5994.5     .08       0  6212.1     .16       0
Bank Sta=4956.3,5093.8
XS Rating Curve= 0 ,0
Exp/Cntr=0.3,0.1

Type RM Length L Ch R = 1 ,84429   ,477,477,477
BEGIN DESCRIPTION:
MILLER CREEK 131.0
END DESCRIPTION:
XS GIS Cut Line= 3
      2916355.96     10043940.75      2916418.46     10042642.14
      2916245.28     10041977.14
#Sta/Elev= 30
    3502 1278.82    3840 1258.83  3949.5 1248.01  4066.8 1240.35  4480.2 1236.44
  4540.2 1234.67  4730.4 1222.21  4808.6 1219.23  4825.9  1219.1  4905.1 1217.61
  4965.8 1212.11  5018.5 1211.34  5021.2 1210.84  5024.5 1211.34  5038.1 1220.44
  5056.8 1231.66    5062 1227.12  5069.1 1234.68  5079.5 1237.56  5117.2  1240.3
  5162.1 1240.13  5183.5 1245.11  5224.1 1264.57  5234.8 1267.61  5265.5 1283.71
  5299.9 1294.03  5337.6 1310.99  5348.1 1315.96  5389.5 1325.51  5489.3 1340.22
#Mann= 10 ,-1 , 0
    3502      .1       0    3840     .16       0  4066.8     .05       0
  4808.6      .1       0  4825.9     .05       0  5018.5     .04       0
  5024.5     .05       0  5117.2      .1       0  5234.8     .08       0
  5337.6     .16       0
Bank Sta=4730.4,5038.1
XS Rating Curve= 0 ,0
Exp/Cntr=0.3,0.1