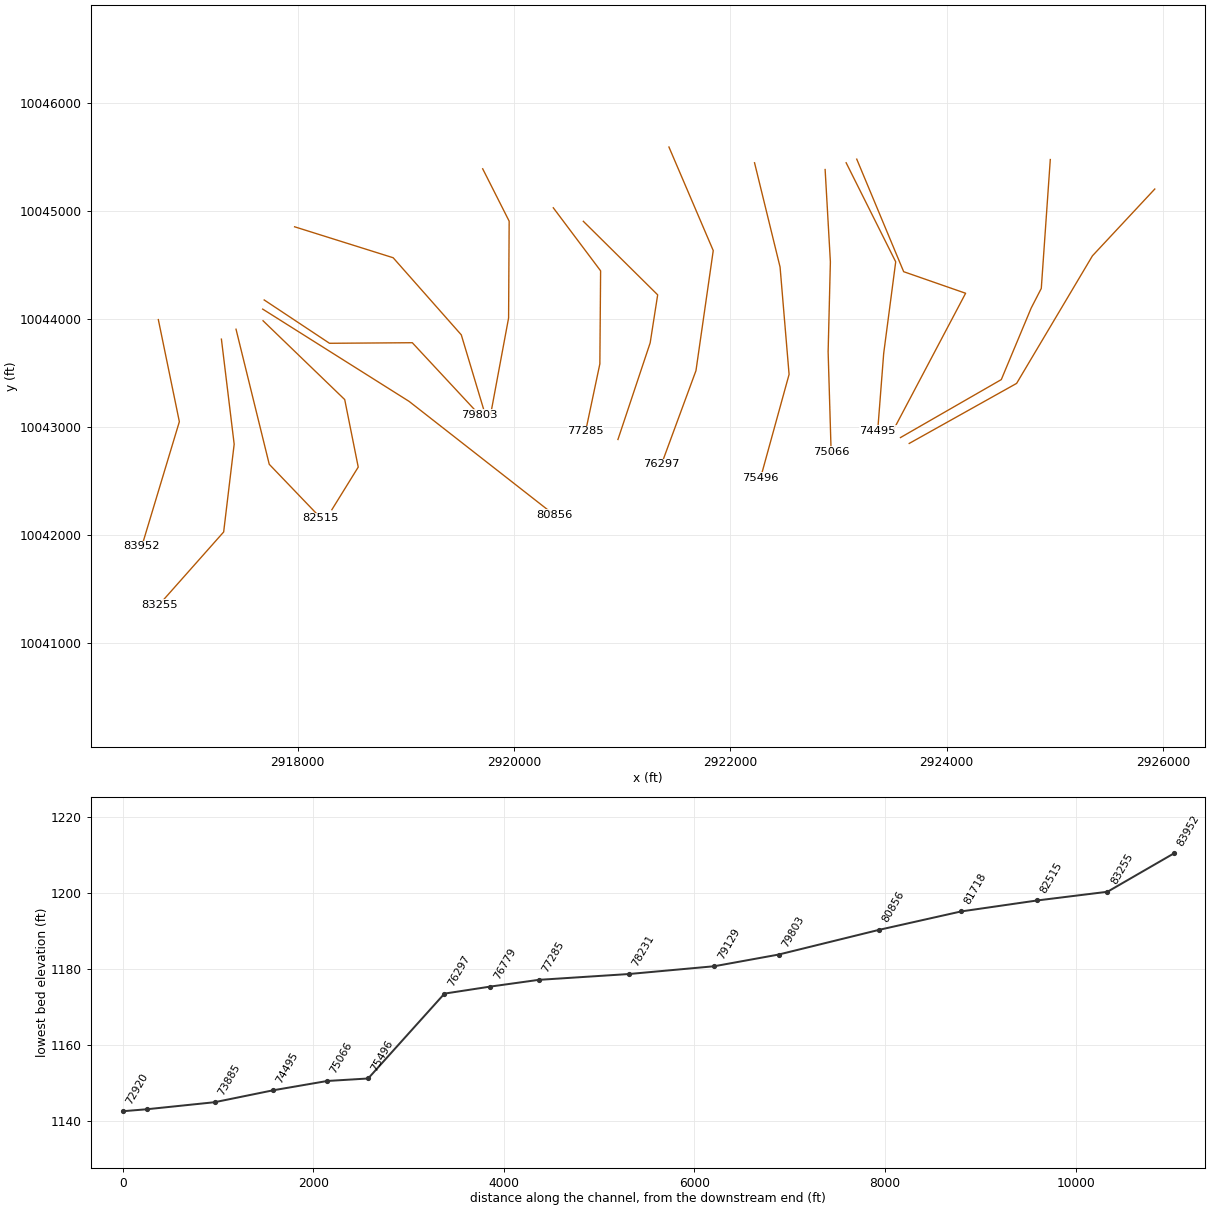
HEC-RAS study MILLER CREEK.prj: MILLER CREEK Base Level Engineering

--- MILLER CREEK.g01 (geometry) --- (continued)

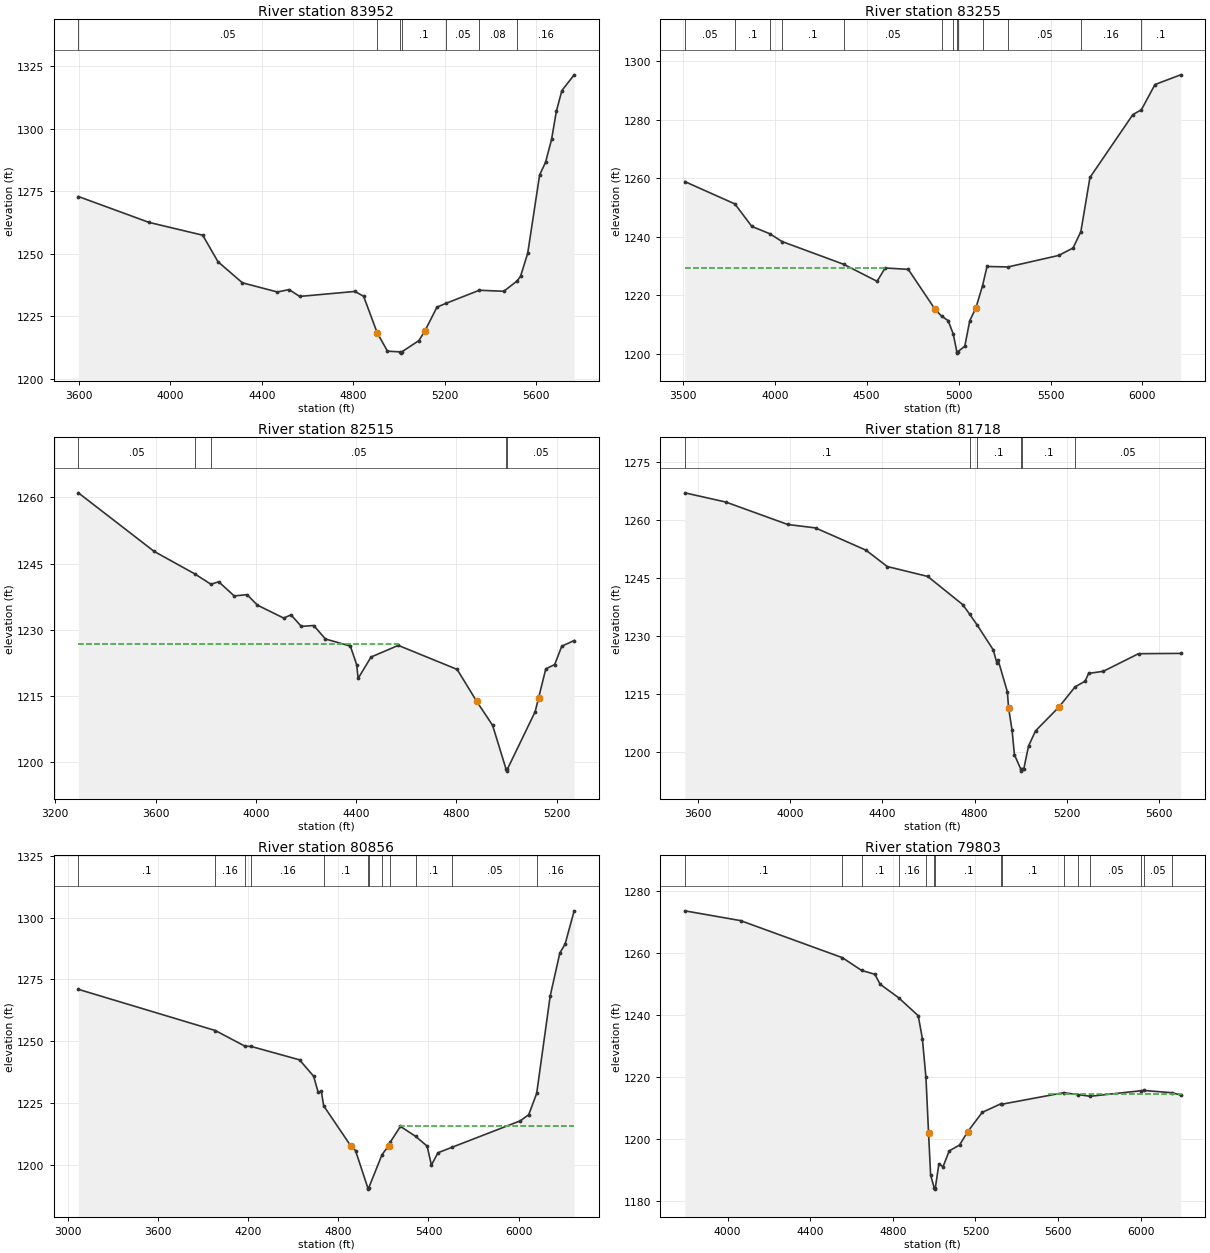
Type RM Length L Ch R = 1 ,83952   ,697,697,697
BEGIN DESCRIPTION:
MILLER CREEK 130.0
END DESCRIPTION:
XS GIS Cut Line= 3
      2916710.12     10043996.35      2916904.57     10043051.87
      2916557.36     10041899.12
#Sta/Elev= 30
  3597.6 1272.88  3906.6 1262.55  4141.4 1257.44  4208.5 1246.83    4315 1238.44
  4468.1 1234.77  4519.2 1235.73  4565.4    1233  4806.9 1234.99  4845.1 1233.06
  4904.4 1218.51  4949.4 1211.15    5006 1210.87  5008.8 1210.37    5012 1210.87
  5086.6 1215.35  5113.5 1219.29  5165.7  1228.7  5203.5 1230.18    5351 1235.46
  5458.1 1235.06  5515.7 1239.13  5531.2 1240.99  5562.6 1250.19  5614.8 1281.48
  5640.7 1286.55    5667 1295.64  5687.9 1306.84    5712 1315.15  5765.8 1321.44
#Mann= 7 ,-1 , 0
  3597.6     .05       0  4904.4      .1       0    5006     .07       0
    5012      .1       0  5203.5     .05       0    5351     .08       0
  5515.7     .16       0
Bank Sta=4904.4,5113.5
XS Rating Curve= 0 ,0
Exp/Cntr=0.3,0.1

Type RM Length L Ch R = 1 ,83255   ,740,740,740
BEGIN DESCRIPTION:
MILLER CREEK 129.0
END DESCRIPTION:
XS GIS Cut Line= 4
      2917293.46     10043815.74      2917411.51     10042843.53
      2917314.29     10042031.03      2916717.65     10041358.08
#Sta/Elev= 30
  3510.7 1258.89    3783 1251.26  3875.4 1243.57  3973.7 1241.06  4039.3 1238.42
  4375.1 1230.64  4556.6 1224.84  4600.6 1229.38  4726.3 1228.91  4872.6 1215.21
  4907.4 1212.93  4943.1 1211.44  4970.8 1206.85  4990.4  1200.8  4993.2  1200.3
  4996.4  1200.8  5033.7 1202.66  5060.8 1211.37  5094.1 1215.75  5130.1 1223.29
  5154.6 1229.89  5269.5 1229.74  5544.7 1233.67  5622.5  1236.2  5664.9 1241.75
  5714.5 1260.29  5947.8 1281.76  5994.3 1283.42  6068.2 1292.03  6207.7 1295.35
#Mann= 13 ,-1 , 0
  3510.7     .05       0    3783      .1       0  3973.7     .05       0
  4039.3      .1       0  4375.1     .05       0  4907.4      .1       0
  4970.8     .05       0  4990.4     .04       0  4996.4     .05       0
  5130.1     .08       0  5269.5     .05       0  5664.9     .16       0
  5994.3      .1       0
#XS Ineff= 2 , 0
         4604.55 1229.54
Permanent Ineff=
       T       T
Bank Sta=4872.6,5094.1
XS Rating Curve= 0 ,0
Exp/Cntr=0.3,0.1

Type RM Length L Ch R = 1 ,82515   ,797,797,797
BEGIN DESCRIPTION:
MILLER CREEK 128.0
END DESCRIPTION:
XS GIS Cut Line= 3
      2917428.63     10043907.44      2917735.92     10042657.44
      2918213.67     10042158.92
#Sta/Elev= 30
  3291.9 1261.02  3594.3 1247.76  3756.7 1242.66  3820.8 1240.32  3851.7 1240.89
  3913.6 1237.68  3965.1 1237.96  4006.3 1235.59  4111.2 1232.66  4140.1  1233.4
  4181.3 1230.78  4230.7 1230.98  4277.4 1227.93    4377 1226.32    4402 1222.12
  4407.9    1219  4459.4 1223.84  4568.2 1226.48  4802.9 1221.04  4880.6 1213.83
  4944.4 1208.37  4997.7 1198.51  5000.4 1198.01  5003.7 1198.51  5113.9 1211.45
  5128.1 1214.68  5156.4 1221.16  5191.9 1222.14  5220.2  1226.3  5269.6 1227.58
#Mann= 5 ,-1 , 0
  3291.9     .05       0  3756.7      .1       0  3820.8     .05       0
  4997.7    .035       0  5003.7     .05       0
#XS Ineff= 2 , 0
         4565.34 1226.75
Permanent Ineff=
       T       T
Bank Sta=4880.6,5128.1
XS Rating Curve= 0 ,0
Exp/Cntr=0.3,0.1

Type RM Length L Ch R = 1 ,81718   ,862,862,862
BEGIN DESCRIPTION:
MILLER CREEK 126.0
END DESCRIPTION:
XS GIS Cut Line= 4
      2917678.65     10043985.54      2918433.84      10043256.4
      2918558.84      10042631.4      2918315.01     10042237.12
#Sta/Elev= 30
  3542.8 1267.01  3720.8 1264.63  3989.4 1258.83  4109.8 1257.95    4329 1252.19
  4420.8 1247.98  4596.5 1245.42  4748.5 1238.13  4777.9  1235.7  4811.3 1232.84
  4880.8 1226.45  4896.3  1223.1  4901.4  1223.9    4942 1215.61  4947.3 1211.45
  4962.4  1205.7  4972.6 1199.38  5000.4 1195.63  5003.2 1195.13  5006.4 1195.63
  5013.4 1195.75  5033.8 1201.61  5064.4 1205.55  5166.4 1211.73  5235.9 1216.91
  5279.1 1218.36  5294.5 1220.37  5358.3 1220.92  5510.8 1225.46  5693.5 1225.54
#Mann= 6 ,-1 , 0
  3542.8      .1       0  4777.9     .16       0  4811.3      .1       0
  5000.4     .07       0  5006.4      .1       0  5235.9     .05       0
Bank Sta=4947.3,5166.4
XS Rating Curve= 0 ,0
Exp/Cntr=0.3,0.1

Type RM Length L Ch R = 1 ,80856   ,1053,1053,1053
BEGIN DESCRIPTION:
MILLER CREEK 124.0
END DESCRIPTION:
XS GIS Cut Line= 3
      2917675.38     10044093.55      2919029.57     10043239.37
      2920369.83     10042190.77
#Sta/Elev= 30
  3067.6 1271.01  3980.2 1254.36  4176.8 1248.07  4219.9 1247.92  4540.9 1242.52
  4635.1 1235.89  4665.1 1229.42  4686.1 1229.85  4701.9 1223.96  4885.1 1207.52
    4914 1205.86    4996 1190.79  4998.8 1190.29    5002 1190.79  5090.7 1204.24
  5135.5 1207.88    5146 1209.32  5213.2 1215.64  5314.5 1211.61    5391 1207.67
  5419.5 1199.99  5462.9 1204.97  5558.2 1207.23  6011.7 1217.89  6067.8 1220.37
  6120.8 1228.98  6210.7  1268.3  6274.9 1285.68  6310.2 1289.31  6370.4 1302.72
#Mann= 12 ,-1 , 0
  3067.6      .1       0  3980.2     .16       0  4176.8      .1       0
  4219.9     .16       0  4701.9      .1       0    4996     .07       0
    5002      .1       0  5090.7     .16       0    5146     .05       0
  5314.5      .1       0  5558.2     .05       0  6120.8     .16       0
#XS Ineff= 2 , 0
                         5211.36         1215.92
Permanent Ineff=
       T       T
Bank Sta=4885.1,5135.5
XS Rating Curve= 0 ,0
Exp/Cntr=0.3,0.1

Type RM Length L Ch R = 1 ,79803   ,674,674,674
BEGIN DESCRIPTION:
MILLER CREEK 123.0
END DESCRIPTION:
XS GIS Cut Line= 4
      2917689.08     10044178.25      2918293.21     10043777.23
      2919058.84     10043782.44      2919678.61      10043115.8
#Sta/Elev= 30
  3792.5 1273.75  4062.3 1270.59  4555.2 1258.62  4648.8 1254.48  4712.9 1253.25
  4738.2 1250.04  4827.4 1245.69  4922.9 1239.86  4942.9 1232.46  4960.2 1219.95
  4972.9 1201.95  4982.9 1188.35  4999.9 1184.31  5002.6 1183.81  5005.9 1184.31
  5022.9 1191.99  5042.9 1191.05  5072.9 1196.16  5122.9 1198.07  5162.9 1202.42
  5232.9 1208.63  5325.1 1211.45  5330.3 1211.28    5627 1214.97  5697.1 1214.35
  5756.2 1213.82  6000.8  1215.6  6014.6  1215.7  6152.7 1214.96  6193.5  1214.2
#Mann= 15 ,-1 , 0
  3792.5      .1       0  4555.2     .16       0  4648.8      .1       0
  4827.4     .16       0  4960.2      .1       0  4999.9     .07       0
  5005.9      .1       0  5325.1     .16       0  5330.3      .1       0
    5627     .05       0  5697.1      .1       0  5756.2     .05       0
  6000.8      .1       0  6014.6     .05       0  6152.7      .1       0
#XS Ineff= 2 , 0
                         5557.39         1214.61
Permanent Ineff=
       T       T
Bank Sta=4972.9,5162.9
XS Rating Curve= 0 ,0
Exp/Cntr=0.3,0.1

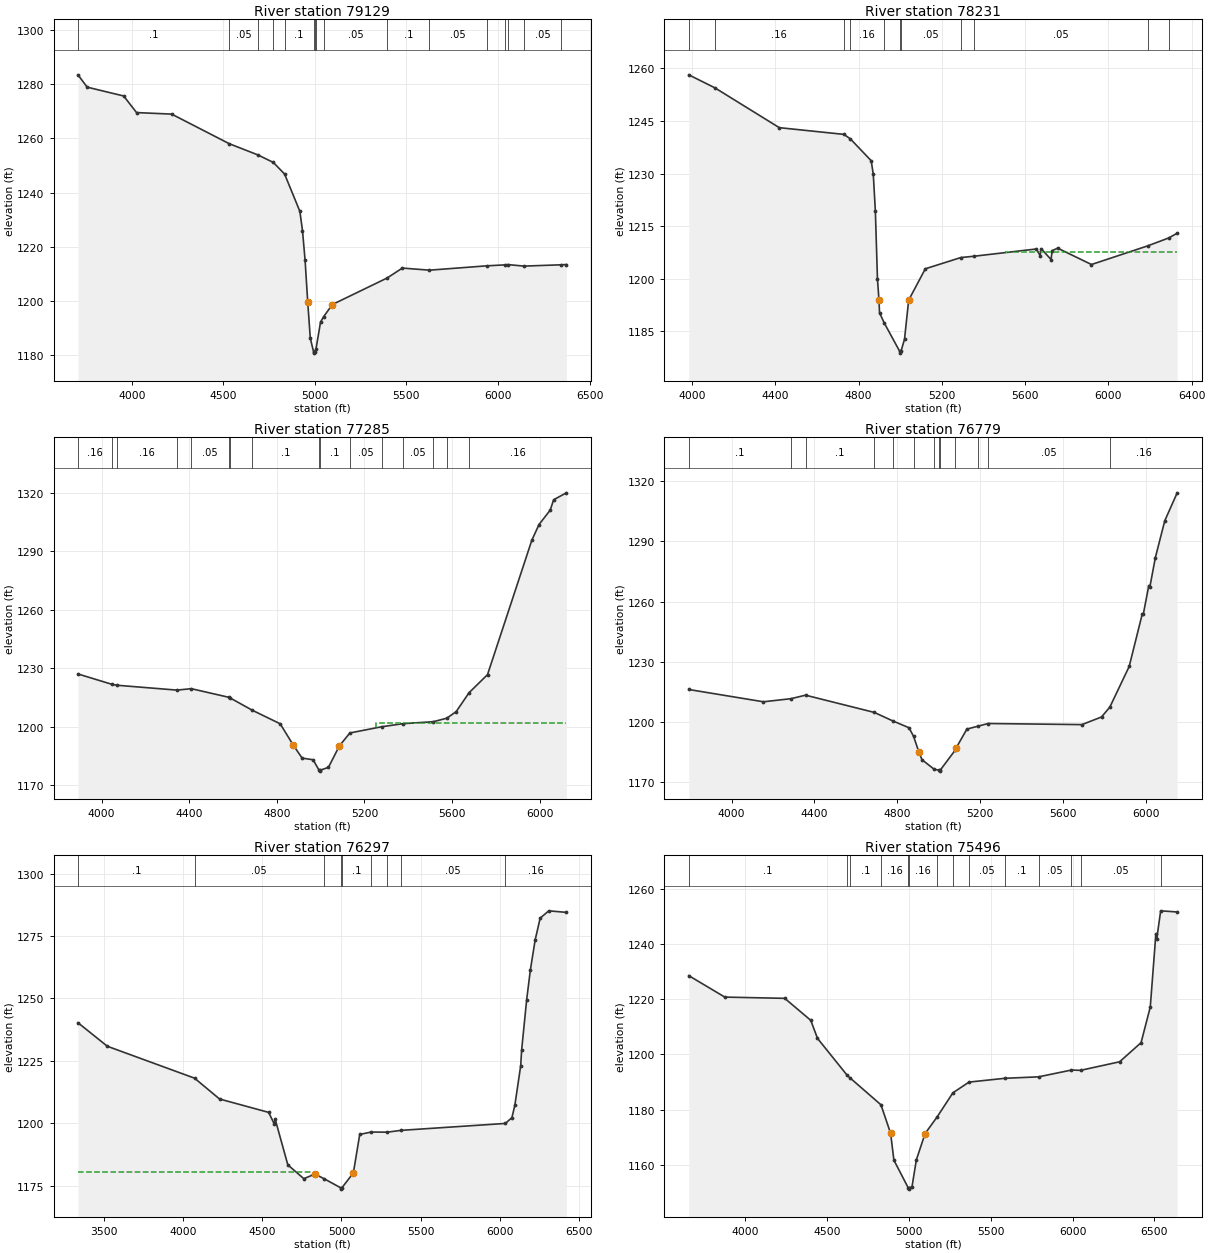
Type RM Length L Ch R = 1 ,79129   ,898,898,898
BEGIN DESCRIPTION:
MILLER CREEK 121.0
END DESCRIPTION:
XS GIS Cut Line= 4
      2917970.33     10044855.34      2918881.76      10044568.9
      2919511.96     10043855.35      2919730.33     10043127.48
#Sta/Elev= 30
  3706.2  1283.5  3756.5 1278.95  3955.8 1275.69  4026.2 1269.56  4217.9    1269
  4532.8 1258.06  4689.7 1253.91  4773.2 1251.15  4834.7 1246.86  4918.1 1233.09
  4932.4 1226.02  4946.6 1215.03  4960.8 1199.77    4975 1186.24  4992.9 1181.25
  4995.7 1180.75  4998.9 1181.25  5005.9 1182.21    5031 1192.23    5048 1194.21
  5095.4 1198.69  5394.4 1208.48  5477.8 1212.15    5626 1211.38  5938.7 1212.98
  6040.1 1213.34  6054.1 1213.44  6141.5 1212.88  6344.3 1213.36  6373.5 1213.45
#Mann= 16 ,-1 , 0
  3706.2      .1       0  4532.8     .05       0  4689.7      .1       0
  4773.2     .05       0  4834.7      .1       0  4992.9     .07       0
  4998.9      .1       0  5005.9     .16       0    5048     .05       0
  5394.4      .1       0    5626     .05       0  5938.7      .1       0
  6040.1     .05       0  6054.1      .1       0  6141.5     .05       0
  6344.3      .1       0
Bank Sta=4960.8,5095.4
XS Rating Curve= 0 ,0
Exp/Cntr=0.3,0.1

Type RM Length L Ch R = 1 ,78231   ,946,946,946
BEGIN DESCRIPTION:
MILLER CREEK 120.0
END DESCRIPTION:
XS GIS Cut Line= 4
      2919709.87     10045391.84      2919954.67     10044907.44
      2919949.46      10044011.6       2919783.4     10043119.02
#Sta/Elev= 30
    3984 1258.19  4109.4 1254.48  4418.9  1243.1  4729.1 1241.18  4760.1 1239.91
  4860.5 1233.66  4870.5 1229.75  4880.5 1219.26  4890.5 1199.96 4897.73 1193.92
  4900.5 1190.21  4923.7 1187.26  4997.5  1179.2  5000.2  1178.7  5003.5  1179.2
  5020.5 1182.67  5040.5 1193.84  5120.5 1202.79  5291.2    1206  5355.1 1206.38
  5654.4 1208.45  5671.9 1206.54  5676.9 1208.54  5724.6 1205.44  5729.7 1207.95
  5756.1 1208.69  5918.8 1204.01  6189.6 1209.35  6290.5 1211.61  6330.5 1212.95
#Mann= 11 ,-1 , 0
    3984      .1       0  4109.4     .16       0  4729.1      .1       0
  4760.1     .16       0  4923.7     .05       0  4997.5    .035       0
  5003.5     .05       0  5291.2     .16       0  5355.1     .05       0
  6189.6      .1       0  6290.5     .05       0
#XS Ineff= 2 , 0
                         5507.95         1207.68
Permanent Ineff=
       T       T
Bank Sta=4897.73,5040.5
XS Rating Curve= 0 ,0
Exp/Cntr=0.3,0.1

Type RM Length L Ch R = 1 ,77285   ,506,506,506
BEGIN DESCRIPTION:
MILLER CREEK 118.0
END DESCRIPTION:
XS GIS Cut Line= 4
       2920362.9     10045031.04       2920800.4      10044447.7
      2920793.46     10043586.59      2920661.51     10042961.58
#Sta/Elev= 30
  3892.4 1227.05    4048 1221.71    4071 1221.25  4344.1 1218.76  4409.7 1219.49
  4582.4 1215.03  4584.1 1214.92  4687.6 1208.45  4815.5 1201.46  4875.5 1190.43
  4915.5 1183.85  4965.6 1183.01  4992.6 1177.67  4995.3 1177.17  4998.6 1177.67
  5035.6  1179.1  5085.6 1190.14  5133.4 1196.76    5278 1199.94  5376.4 1201.54
  5513.9 1202.53    5576 1204.35  5618.5  1207.7  5677.5 1217.44  5761.6  1226.7
  5963.8 1295.68  5996.7 1303.77  6047.8 1311.16  6063.4 1316.47  6121.5 1320.03
#Mann= 16 ,-1 , 0
  3892.4     .16       0    4048      .1       0    4071     .16       0
  4344.1      .1       0  4409.7     .05       0  4582.4      .1       0
  4584.1     .05       0  4687.6      .1       0  4992.6     .07       0
  4998.6      .1       0  5133.4     .05       0    5278      .1       0
  5376.4     .05       0  5513.9      .1       0    5576     .05       0
  5677.5     .16       0
#XS Ineff= 2 , 0
                         5252.27          1201.9
Permanent Ineff=
       T       T
Bank Sta=4875.5,5085.6
XS Rating Curve= 0 ,0
Exp/Cntr=0.3,0.1

Type RM Length L Ch R = 1 ,76779   ,482,482,482
BEGIN DESCRIPTION:
MILLER CREEK 117.0
END DESCRIPTION:
XS GIS Cut Line= 4
      2920640.66     10044906.05      2921328.18     10044225.48
      2921258.74     10043781.03       2920960.7     10042886.94
#Sta/Elev= 30
  3792.9 1216.12  4153.6 1209.99  4286.7 1211.54    4357 1213.29  4689.3 1204.69
  4778.2 1200.47  4856.9 1197.04    4879 1192.77  4903.8 1185.19  4919.7 1181.09
  4979.2 1176.29    5002 1175.91  5004.7 1175.41    5008 1175.91  5079.4 1185.76
    5086 1187.19  5136.6 1196.37  5189.7 1197.81  5239.4 1199.16  5692.2 1198.61
    5787 1202.41  5827.1 1207.32  5920.7 1227.59  5983.9 1253.78  5989.2 1253.78
  6015.5 1267.97  6020.8 1267.35  6047.1 1281.86  6092.7 1300.29  6152.6  1314.2
#Mann= 13 ,-1 , 0
  3792.9      .1       0  4286.7     .05       0    4357      .1       0
  4689.3     .16       0  4778.2      .1       0    4879     .05       0
  4979.2      .1       0    5002     .07       0    5008      .1       0
  5079.4     .05       0  5189.7      .1       0  5239.4     .05       0
  5827.1     .16       0
Bank Sta=4903.8,5086
XS Rating Curve= 0 ,0
Exp/Cntr=0.3,0.1

Type RM Length L Ch R = 1 ,76297   ,801,801,801
BEGIN DESCRIPTION:
MILLER CREEK 116.0
END DESCRIPTION:
XS GIS Cut Line= 4
      2921432.33     10045593.58      2921842.07      10044635.2
      2921682.35     10043524.09      2921363.69     10042658.18
#Sta/Elev= 30
  3334.3 1240.27  3519.9 1230.83  4071.3 1218.04  4229.4 1209.69  4539.7 1204.33
  4576.3 1199.54  4581.4  1201.5    4661 1183.29    4762 1177.75  4832.7 1179.61
  4889.2 1177.76  4996.3 1174.06  4999.1 1173.56  5002.3 1174.06  5075.2 1180.06
  5115.6 1195.49  5189.2 1196.45  5289.2 1196.39  5376.5 1197.12  6036.1 1199.89
  6077.6 1202.23  6096.2 1207.22  6133.2 1223.08  6138.8  1229.2  6170.8  1249.5
  6194.1 1261.36  6224.6 1273.49  6256.1 1282.19  6310.7 1285.12  6421.8  1284.5
#Mann= 9 ,-1 , 0
  3334.3      .1       0  4071.3     .05       0  4889.2      .1       0
  4996.3     .07       0  5002.3      .1       0  5189.2     .05       0
  5289.2      .1       0  5376.5     .05       0  6036.1     .16       0
#XS Ineff= 2 , 0
          4801.7  1180.5
Permanent Ineff=
       T       T
Bank Sta=4832.7,5075.2
XS Rating Curve= 0 ,0
Exp/Cntr=0.3,0.1

Type RM Length L Ch R = 1 ,75496   ,430,430,430
BEGIN DESCRIPTION:
MILLER CREEK 115.0
END DESCRIPTION:
XS GIS Cut Line= 4
        2922224.     10045447.74      2922460.13     10044482.42
      2922543.46     10043489.37      2922279.58     10042531.06
#Sta/Elev= 30
  3655.1 1228.49  3875.4 1220.73  4241.5 1220.28  4400.5 1212.33  4441.6 1205.81
  4622.9 1192.46  4637.7 1191.65  4829.4 1181.78  4888.4 1171.46  4908.5 1161.76
  4995.8 1151.78  4998.5 1151.28  5001.8 1151.78  5018.9 1152.07  5045.8 1161.88
  5099.1 1171.38  5170.9 1177.24  5269.2 1186.13  5367.6 1189.99  5585.9 1191.36
  5792.6 1191.89  5993.4 1194.35    6049 1194.24  6287.5 1197.33  6418.8 1204.25
    6475 1217.13  6509.4 1243.68  6514.5 1241.81  6538.6 1251.93  6639.4 1251.52
#Mann= 14 ,-1 , 0
  3655.1      .1       0  4622.9     .16       0  4637.7      .1       0
  4829.4     .16       0  4995.8     .07       0  5001.8     .16       0
  5170.9     .05       0  5269.2      .1       0  5367.6     .05       0
  5585.9      .1       0  5792.6     .05       0  5993.4      .1       0
    6049     .05       0  6538.6      .1       0
Bank Sta=4888.4,5099.1
XS Rating Curve= 0 ,0
Exp/Cntr=0.3,0.1

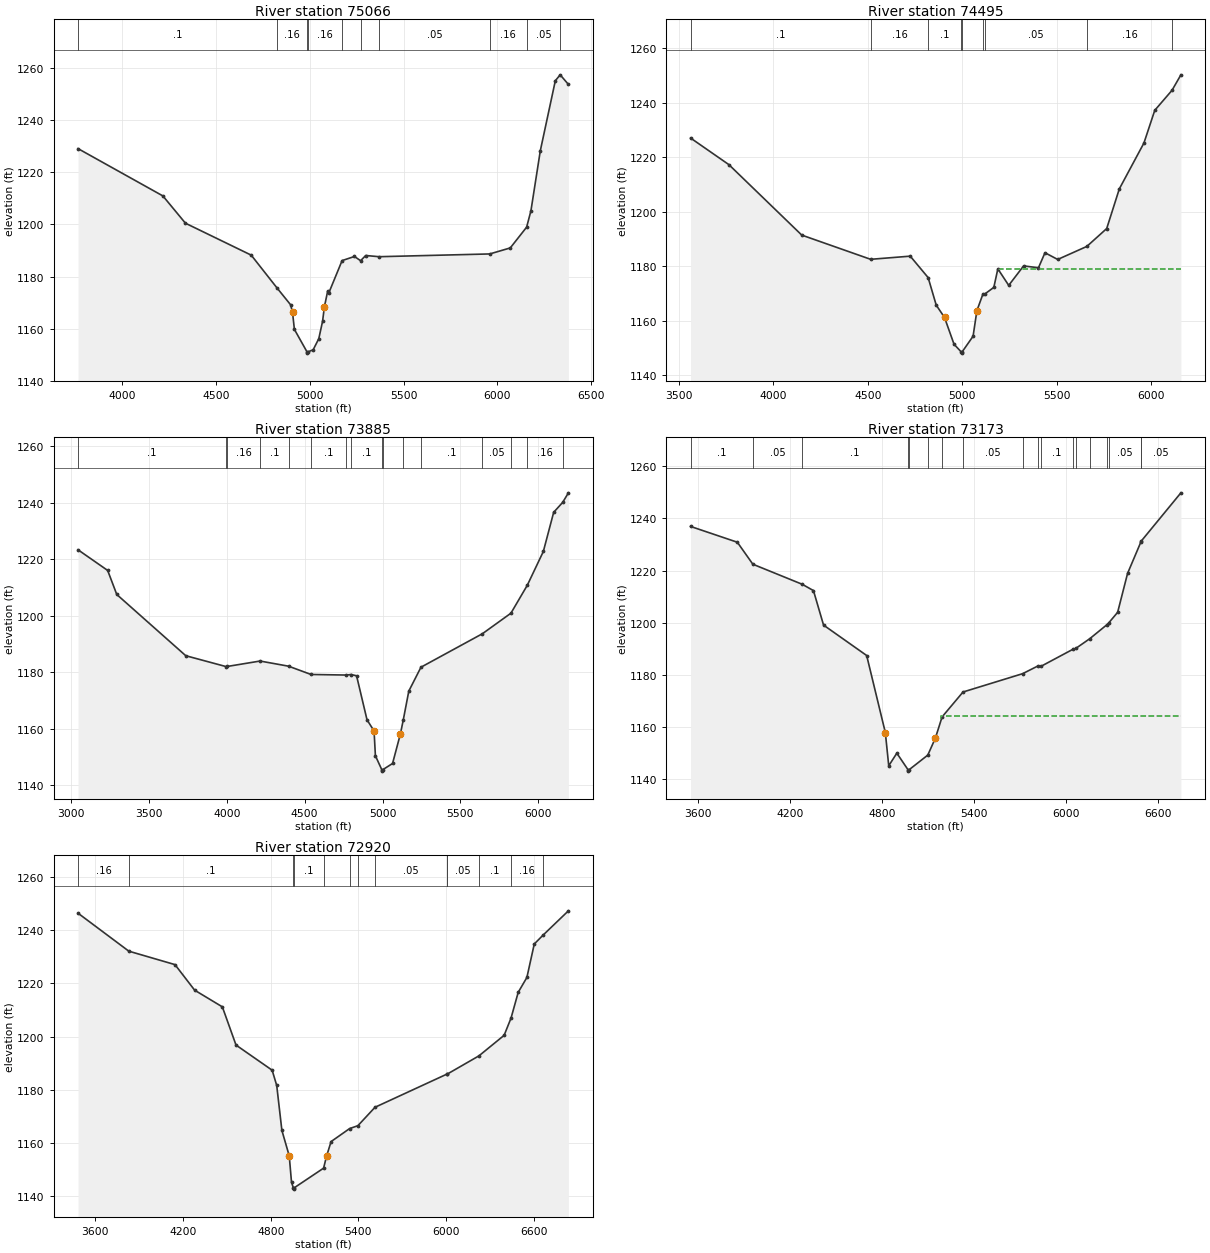
Type RM Length L Ch R = 1 ,75066   ,571,571,571
BEGIN DESCRIPTION:
MILLER CREEK 114.0
END DESCRIPTION:
XS GIS Cut Line= 4
       2922876.8     10045385.15       2922925.4     10044531.03
      2922904.57      10043697.7      2922932.35     10042774.11
#Sta/Elev= 30
  3765.3 1229.09  4217.4 1210.94  4337.6 1200.47  4688.1 1188.22  4826.7 1175.53
  4898.2 1169.15  4908.2 1166.24  4918.2 1159.73  4985.2 1151.12    4988 1150.62
  4991.2 1151.12  5018.2  1151.9  5048.2 1156.17  5068.2 1162.78  5078.2 1168.41
  5095.8 1174.53  5100.9 1173.61  5172.4 1186.13  5238.3 1187.71  5270.9 1186.08
  5298.3 1188.08  5369.4 1187.62  5959.3 1188.68  6068.6 1190.99  6155.8 1198.96
  6178.7 1205.24  6228.7 1228.28  6308.7 1255.15  6334.6 1257.41  6378.4 1253.73
#Mann= 10 ,-1 , 0
  3765.3      .1       0  4826.7     .16       0  4985.2     .07       0
  4991.2     .16       0  5172.4     .05       0  5270.9      .1       0
  5369.4     .05       0  5959.3     .16       0  6155.8     .05       0
  6334.6      .1       0
Bank Sta=4908.2,5078.2
XS Rating Curve= 0 ,0
Exp/Cntr=0.3,0.1

Type RM Length L Ch R = 1 ,74495   ,610,610,610
BEGIN DESCRIPTION:
MILLER CREEK 113.0
END DESCRIPTION:
XS GIS Cut Line= 4
      2923071.22     10045447.73      2923529.57     10044531.03
      2923418.46     10043683.81      2923362.91     10042968.64
#Sta/Elev= 30
  3561.5 1227.11  3764.7 1217.33  4150.4 1191.48  4515.2 1182.59  4724.9 1183.75
  4819.7 1175.88  4862.5 1165.78  4906.4 1161.25  4956.8 1151.42  4994.2 1148.66
  4996.9 1148.16  5000.2 1148.66  5057.7 1154.37  5077.9 1163.74  5109.4 1169.75
    5119 1169.82  5167.6  1172.3  5188.8 1179.09  5246.4 1173.03  5325.2 1180.17
    5404 1179.49  5438.4    1185  5505.8 1182.54  5660.1 1187.32  5765.3 1193.88
  5832.1 1208.44  5962.5 1225.28  6019.8 1237.27  6111.4 1244.64  6158.2  1250.3
#Mann= 9 ,-1 , 0
  3561.5      .1       0  4515.2     .16       0  4819.7      .1       0
  4994.2     .07       0  5000.2      .1       0  5109.4     .16       0
    5119     .05       0  5660.1     .16       0  6111.4     .05       0
#XS Ineff= 2 , 0
                         5194.32          1179.2
Permanent Ineff=
       T       T
Bank Sta=4906.4,5077.9
XS Rating Curve= 0 ,0
Exp/Cntr=0.3,0.1

Type RM Length L Ch R = 1 ,73885   ,712,712,712
BEGIN DESCRIPTION:
MILLER CREEK 112.0
END DESCRIPTION:
XS GIS Cut Line= 4
      2923169.16     10045481.42      2923603.18     10044439.78
       2924176.1     10044240.13      2923516.36     10042990.09
#Sta/Elev= 30
  3044.8 1223.29  3234.9    1216  3293.4  1207.5  3736.5 1185.85    3996    1182
  4003.5 1182.06  4213.5 1183.97  4396.6 1182.15  4540.7 1179.22  4764.8 1179.02
  4797.9  1179.2  4833.2 1178.76  4900.3 1163.18  4945.5 1159.25  4954.1 1150.49
  4995.1 1145.55  4997.8 1145.05  5001.1 1145.55  5064.2 1147.75  5115.1  1158.3
  5132.9 1163.11  5168.6 1173.35  5246.7 1181.79    5641 1193.62  5824.4 1200.89
  5929.3 1210.75  6032.4  1222.7  6098.8 1236.55  6156.9 1240.08  6193.4 1243.44
#Mann= 16 ,-1 , 0
  3044.8      .1       0    3996     .05       0  4003.5     .16       0
  4213.5      .1       0  4396.6     .16       0  4540.7      .1       0
  4764.8     .16       0  4797.9      .1       0  4995.1     .07       0
  5001.1      .1       0  5132.9     .05       0  5246.7      .1       0
    5641     .05       0  5824.4      .1       0  5929.3     .16       0
  6156.9     .05       0
Bank Sta=4945.5,5115.1
XS Rating Curve= 0 ,0
Exp/Cntr=0.3,0.1

Type RM Length L Ch R = 1 ,73173   ,253,253,253
BEGIN DESCRIPTION:
MILLER CREEK 111.0
END DESCRIPTION:
XS GIS Cut Line= 5
       2924959.2     10045477.71      2924875.87     10044285.04
      2924782.12     10044102.75      2924506.07     10043441.29
      2923573.81     10042904.85
#Sta/Elev= 30
  3554.5 1236.94  3859.2 1230.88  3960.2 1222.46  4281.5 1214.78  4354.8 1212.36
  4420.6 1199.14  4701.3 1187.49  4822.8 1157.99    4845 1145.24  4897.7 1150.08
  4970.9  1143.7  4973.6  1143.2  4976.9  1143.7  5099.3 1149.34    5149  1155.9
  5192.5 1163.98  5328.7 1173.51  5716.8 1180.53  5815.6 1183.46  5835.9 1183.33
  6042.9 1189.83  6063.3 1190.22    6154 1193.93  6265.1 1199.26  6276.2 1199.89
  6335.5 1204.04  6400.2 1218.95  6487.3 1231.04  6489.2 1231.32  6747.4 1249.81
#Mann= 18 ,-1 , 0
  3554.5      .1       0  3960.2     .05       0  4281.5      .1       0
  4970.9     .07       0  4976.9      .1       0  5099.3     .16       0
  5192.5      .1       0  5328.7     .05       0  5716.8      .1       0
  5815.6     .05       0  5835.9      .1       0  6042.9     .05       0
  6063.3      .1       0    6154     .05       0  6265.1      .1       0
  6276.2     .05       0  6487.3     .16       0  6489.2     .05       0
#XS Ineff= 2 , 0
                         5188.35         1164.48
Permanent Ineff=
       T       T
Bank Sta=4822.8,5149
XS Rating Curve= 0 ,0
Exp/Cntr=0.3,0.1

Type RM Length L Ch R = 1 ,72920   ,494,494,494
BEGIN DESCRIPTION:
MILLER CREEK 110.0
END DESCRIPTION:
XS GIS Cut Line= 4
       2925925.4     10045204.65      2925349.01     10044586.59
      2924647.63     10043406.03      2923654.57     10042850.48
#Sta/Elev= 30
  3481.2 1246.34  3828.8 1232.08  4144.7 1227.03  4279.1 1217.43  4468.8 1211.16
  4562.3 1196.81  4809.7 1187.36  4840.9 1181.63  4876.3 1164.74  4926.6 1155.18
  4942.2 1145.24  4954.8 1143.18  4957.5 1142.68  4960.8 1143.18  5161.8 1150.56
  5181.8 1155.01    5213 1160.54  5339.5 1165.42  5396.5 1166.51  5513.9 1173.44
  6004.2 1185.85  6008.8 1185.92    6225 1192.75  6397.5 1200.47  6444.9 1206.97
  6493.8 1216.62  6553.2  1222.2  6603.8 1234.79    6664 1238.11  6837.4 1247.24
#Mann= 13 ,-1 , 0
  3481.2     .16       0  3828.8      .1       0  4954.8     .07       0
  4960.8      .1       0  5161.8     .16       0  5339.5      .1       0
  5396.5     .16       0  5513.9     .05       0  6004.2      .1       0
  6008.8     .05       0    6225      .1       0  6444.9     .16       0
    6664     .05       0
Bank Sta=4926.6,5181.8
XS Rating Curve= 0 ,0
Exp/Cntr=0.3,0.1