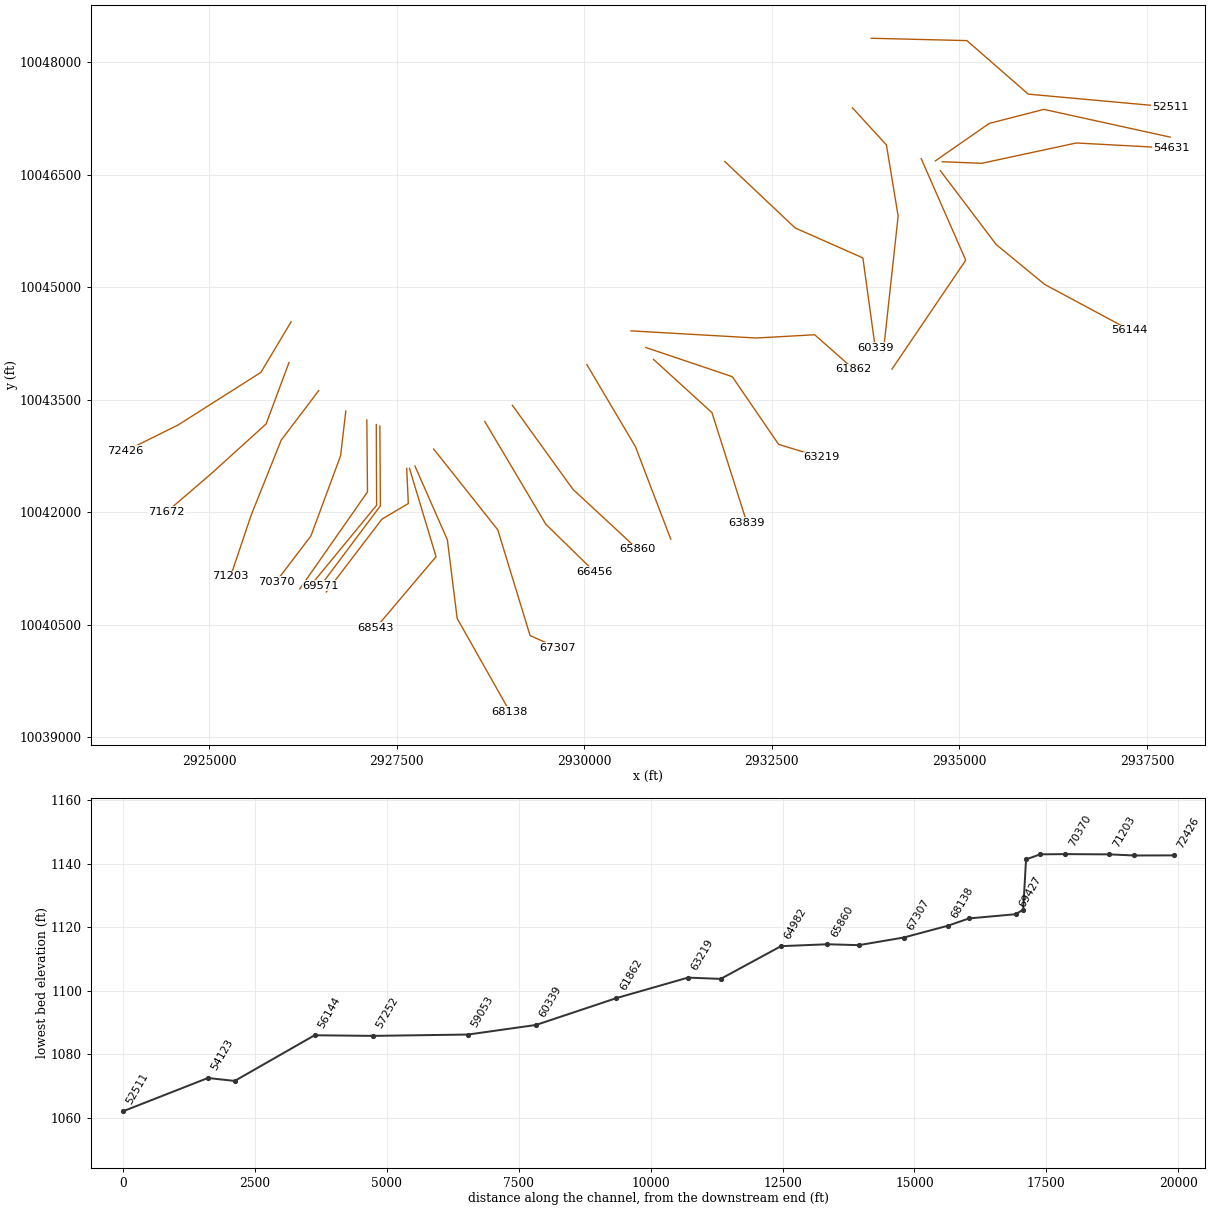
HEC-RAS study MILLER CREEK.prj: MILLER CREEK Base Level Engineering

--- MILLER CREEK.g01 (geometry) --- (continued)

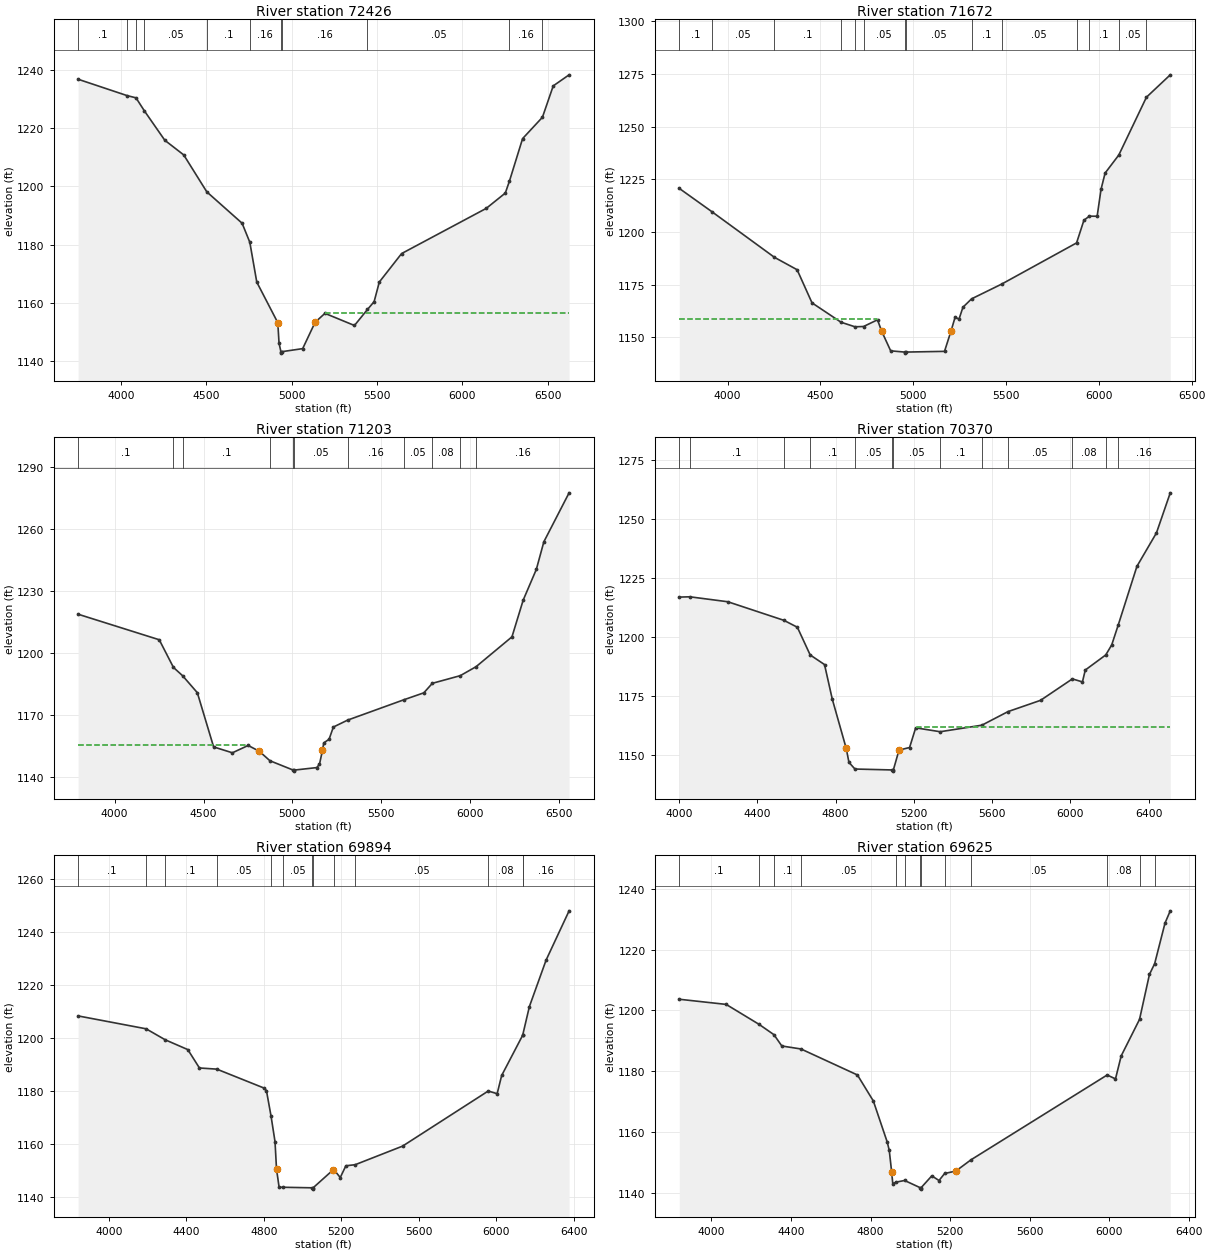
Type RM Length L Ch R = 1 ,72426   ,754,754,754
BEGIN DESCRIPTION:
MILLER CREEK 109.0
END DESCRIPTION:
XS GIS Cut Line= 4
      2926092.09     10044538.02      2925689.29     10043864.37
      2924585.13     10043162.98      2923883.76     10042815.77
#Sta/Elev= 30
    3749 1236.92  4036.6 1231.27  4088.1 1230.52  4137.4 1226.01  4256.9  1215.9
  4367.8 1210.85  4502.9 1198.13  4709.5 1187.33  4754.7 1180.78  4795.5 1167.05
  4918.6 1153.07  4925.8 1146.04  4936.8 1143.09  4939.6 1142.59  4942.8 1143.09
  5064.3 1144.14  5137.2 1153.22  5194.8 1156.29  5367.5 1152.11  5443.8 1157.63
  5482.7 1160.31  5513.2 1167.08  5643.7 1176.88  6139.3 1192.44  6251.1 1197.72
  6275.5 1201.89  6352.3 1216.47  6468.5 1223.83  6531.7 1234.63  6624.6 1238.44
#Mann= 11 ,-1 , 0
    3749      .1       0  4036.6     .05       0  4088.1      .1       0
  4137.4     .05       0  4502.9      .1       0  4754.7     .16       0
  4936.8     .07       0  4942.8     .16       0  5443.8     .05       0
  6275.5     .16       0  6468.5     .05       0
#XS Ineff= 2 , 0
                         5196.31         1156.27
Permanent Ineff=
       T       T
Bank Sta=4918.6,5137.2
XS Rating Curve= 0 ,0
Exp/Cntr=0.3,0.1

Type RM Length L Ch R = 1 ,71672   ,469,469,469
BEGIN DESCRIPTION:
MILLER CREEK 108.0
END DESCRIPTION:
XS GIS Cut Line= 4
      2926064.28     10043996.28      2925758.74     10043176.87
      2925022.63      10042510.2      2924432.91     10042003.74
#Sta/Elev= 30
  3739.7 1220.77  3915.3 1209.72  4252.5 1188.04  4374.6 1182.15  4454.9 1166.42
  4611.4 1157.22  4686.1 1155.07  4732.5  1155.2  4807.7 1158.38  4829.3 1153.11
  4878.6 1143.65  4953.4 1143.06  4956.1 1142.56  4959.4 1143.06  5168.6  1143.4
  5204.4 1153.24  5225.3 1159.51    5247 1158.76  5267.9 1164.34  5314.4 1168.33
  5476.6 1175.34    5880 1194.88  5919.6 1205.64  5948.8 1207.58  5990.9 1207.55
  6011.8 1220.34  6033.7 1228.04  6107.6 1236.62  6256.4 1264.05  6384.7 1274.68
#Mann= 14 ,-1 , 0
  3739.7      .1       0  3915.3     .05       0  4252.5      .1       0
  4611.4     .05       0  4686.1      .1       0  4732.5     .05       0
  4953.4    .033       0  4959.4     .05       0  5314.4      .1       0
  5476.6     .05       0    5880     .08       0  5948.8      .1       0
  6107.6     .05       0  6256.4      .1       0
#XS Ineff= 2 , 0
         4805.68 1158.75
Permanent Ineff=
       T       T
Bank Sta=4829.3,5204.4
XS Rating Curve= 0 ,0
Exp/Cntr=0.3,0.1

Type RM Length L Ch R = 1 ,71203   ,833,833,833
BEGIN DESCRIPTION:
MILLER CREEK 107.0
END DESCRIPTION:
XS GIS Cut Line= 4
      2926460.15     10043621.34      2925960.13     10042961.59
      2925557.35     10041954.64      2925286.52      10041149.1
#Sta/Elev= 30
  3794.2 1218.84  4250.7 1206.48  4330.7 1193.09  4382.1 1189.08    4465 1180.86
  4556.6 1154.63  4662.2 1151.78    4751 1155.33  4813.6 1152.52  4873.5 1147.93
  5004.5 1143.41  5007.2 1142.91  5010.5 1143.41  5136.7 1144.62  5152.2 1146.23
    5169    1153  5176.4 1156.58  5206.1 1158.32  5230.3 1164.25  5311.2 1167.62
  5627.9 1177.47  5739.2  1180.8    5787  1185.4  5944.3 1189.11  6033.1 1193.45
    6235 1207.89  6298.3  1225.7  6372.2 1240.55  6414.4 1253.89  6556.4 1277.58
#Mann= 11 ,-1 , 0
  3794.2      .1       0  4330.7     .05       0  4382.1      .1       0
  4873.5     .05       0  5004.5    .033       0  5010.5     .05       0
  5311.2     .16       0  5627.9     .05       0    5787     .08       0
  5944.3     .05       0  6033.1     .16       0
#XS Ineff= 2 , 0
         4740.91 1155.42
Permanent Ineff=
       T       T
Bank Sta=4813.6,5169
XS Rating Curve= 0 ,0
Exp/Cntr=0.3,0.1

Type RM Length L Ch R = 1 ,70370   ,476,476,476
BEGIN DESCRIPTION:
MILLER CREEK 105.0
END DESCRIPTION:
XS GIS Cut Line= 4
      2926821.23     10043350.44      2926751.79     10042753.26
      2926355.96     10041683.81       2925890.7     10041072.73
#Sta/Elev= 30
  4001.2 1216.89  4055.1 1217.02  4249.6 1214.91  4535.9 1207.03  4604.8 1204.09
  4670.4 1192.32  4743.7 1188.24  4783.2  1173.6  4854.7 1152.61  4868.5 1146.72
  4899.2 1143.88  5089.5 1143.49  5092.3 1142.99  5095.5 1143.49  5124.4 1151.91
  5178.4 1153.02  5209.7 1161.38  5334.9 1159.72    5548  1162.5  5681.6 1168.27
  5847.8 1173.05  6010.4 1182.15  6061.9 1180.88  6076.5 1185.92  6181.1 1192.33
  6211.6 1196.59  6245.4 1205.17  6340.5 1229.97  6440.3 1244.16  6510.8 1261.17
#Mann= 13 ,-1 , 0
  4001.2     .16       0  4055.1      .1       0  4535.9     .05       0
  4670.4      .1       0  4899.2     .05       0  5089.5    .033       0
  5095.5     .05       0  5334.9      .1       0    5548     .16       0
  5681.6     .05       0  6010.4     .08       0  6181.1     .05       0
  6245.4     .16       0
#XS Ineff= 2 , 0
                         5215.34          1161.9
Permanent Ineff=
       T       T
Bank Sta=4854.7,5124.4
XS Rating Curve= 0 ,0
Exp/Cntr=0.3,0.1

Type RM Length L Ch R = 1 ,69894   ,269,269,269
BEGIN DESCRIPTION:
Mapping XS 1d31ea20
END DESCRIPTION:
XS GIS Cut Line= 3
      2927101.56     10043230.38      2927110.24     10042271.15
      2926207.79     10040978.22
#Sta/Elev= 30
  3840.5 1208.37  4191.8  1203.5  4290.2 1199.36  4407.2 1195.64  4467.2  1188.7
    4557 1188.26  4799.8 1181.14  4813.3 1180.16  4837.1 1170.52  4857.6 1160.87
 4865.34 1150.51  4878.7 1143.65  4900.8 1143.62  5048.4 1143.42  5051.2 1142.92
  5054.4 1143.42  5158.7 1150.26    5162 1150.27  5194.5 1147.29  5223.5 1151.74
  5271.7 1152.15  5516.4 1159.17  5958.9 1179.99  6004.9 1178.98  6028.3 1185.87
  6136.7 1201.05  6137.1 1201.18  6171.5 1211.92  6257.8 1229.48  6376.5 1248.08
#Mann= 13 ,-1 , 0
  3840.5      .1       0  4191.8     .05       0  4290.2      .1       0
    4557     .05       0  4837.1     .16       0  4900.8     .05       0
  5048.4    .033       0  5054.4     .05       0    5162      .1       0
  5271.7     .05       0  5958.9     .08       0  6136.7     .05       0
  6137.1     .16       0
Bank Sta=4865.34,5158.7
XS Rating Curve= 0 ,0
Exp/Cntr=0.3,0.1

Type RM Length L Ch R = 1 ,69625   ,54,54,54
BEGIN DESCRIPTION:
Mapping XS bec2a497
END DESCRIPTION:
XS GIS Cut Line= 3
      2927227.43     10043169.58      2927231.77      10042093.2
      2926347.14     10041017.78
#Sta/Elev= 30
  3838.1 1203.69  4073.9    1202  4239.6 1195.44  4314.3 1192.05  4353.9 1188.34
  4450.2 1187.36    4734 1178.82    4814 1170.28    4884 1156.76    4894 1154.07
 4906.25 1146.88  4911.7 1143.15    4928 1143.62  4971.3 1144.17  5048.6 1141.83
  5051.4 1141.33  5054.6 1141.83    5108 1145.69  5144.2 1144.16  5172.6 1146.47
  5228.8 1147.26  5304.6 1150.94  5989.7 1178.81  6031.6 1177.54  6060.3 1185.09
  6152.5 1197.08  6202.4 1211.85  6228.5 1215.37  6280.6  1228.7    6307 1232.73
#Mann= 13 ,-1 , 0
  3838.1      .1       0  4239.6     .05       0  4314.3      .1       0
  4450.2     .05       0    4928      .1       0  4971.3     .05       0
  5048.6    .033       0  5054.6     .05       0  5172.6      .1       0
  5304.6     .05       0  5989.7     .08       0  6152.5     .05       0
  6228.5     .16       0
Bank Sta=4906.25,5228.8
XS Rating Curve= 0 ,0
Exp/Cntr=0.3,0.1

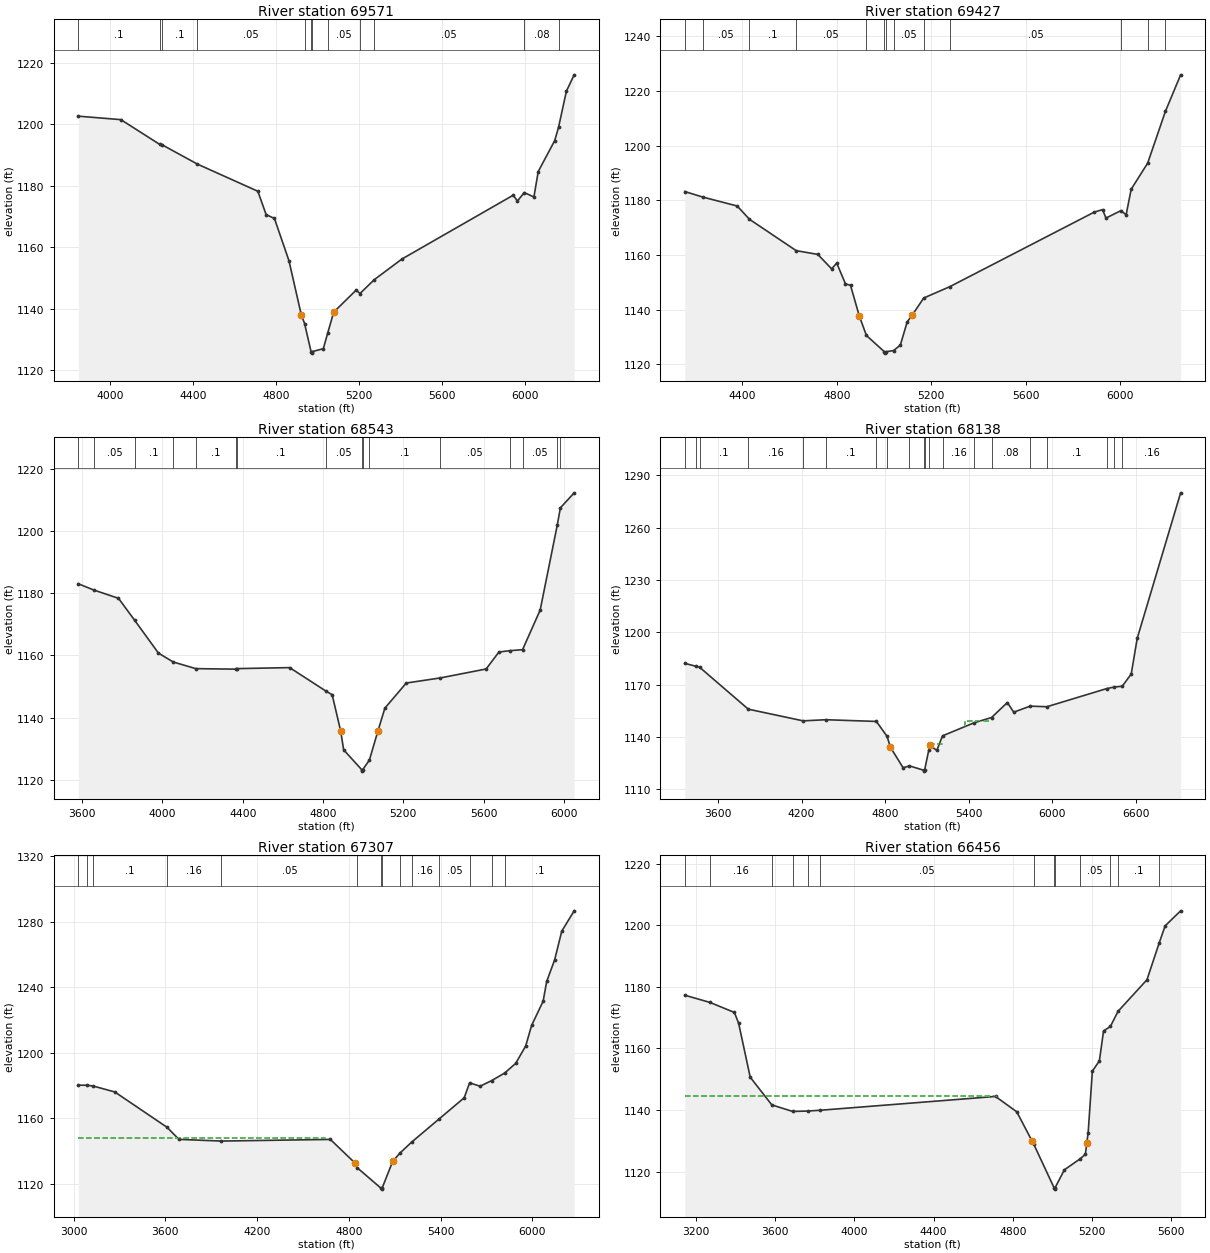
Type RM Length L Ch R = 1 ,69571   ,144,144,144
BEGIN DESCRIPTION:
MILLER CREEK 104.0
END DESCRIPTION:
XS GIS Cut Line= 3
      2927275.17     10043148.77      2927282.12     10042086.26
      2926486.99     10041023.77
#Sta/Elev= 30
  3847.4 1202.57  4052.4 1201.44  4239.5  1193.4  4250.2  1193.3  4421.2 1186.99
  4712.5 1178.16  4752.5 1170.57  4792.5 1169.32  4862.5 1155.58  4921.9 1137.99
  4937.8 1135.17  4968.9 1126.04  4971.6 1125.54  4974.9 1126.04  5028.1 1126.99
  5048.9 1131.97  5078.1 1138.86  5186.5 1146.03  5204.7 1144.91  5273.3  1149.4
  5407.4 1156.15    5943 1176.87  5963.8    1175  5996.6 1177.74    6043  1176.3
  6063.9 1184.58  6143.1  1194.6  6161.6  1198.9  6199.6 1210.69    6237 1216.01
#Mann= 12 ,-1 , 0
  3847.4      .1       0  4239.5     .05       0  4250.2      .1       0
  4421.2     .05       0  4937.8      .1       0  4968.9     .07       0
  4974.9      .1       0  5048.9     .05       0  5204.7      .1       0
  5273.3     .05       0  5996.6     .08       0  6161.6     .05       0
Bank Sta=4921.9,5078.1
XS Rating Curve= 0 ,0
Exp/Cntr=0.3,0.1

Type RM Length L Ch R = 1 ,69427   ,884,884,884
BEGIN DESCRIPTION:
Mapping XS 8a1f8864
END DESCRIPTION:
XS GIS Cut Line= 4
      2927632.81     10042585.39      2927654.51     10042116.64
      2927302.95      10041908.3      2926561.76     10040937.39
#Sta/Elev= 30
  4156.1 1183.23  4233.4 1181.19    4378 1177.94  4429.9 1173.08  4627.7 1161.61
  4719.4 1160.22  4777.9 1154.94  4799.4 1157.03  4836.4 1149.46  4857.8  1148.9
  4894.9  1137.7  4925.1 1130.55  5001.3 1124.59  5004.1 1124.09  5007.3 1124.59
  5039.8 1125.03  5068.7 1127.01  5097.7 1135.52  5118.5 1137.93  5167.7 1144.26
  5278.5 1148.43  5889.5 1175.69  5924.9 1176.63  5939.4 1173.52    6003 1176.26
  6024.7  1174.7  6046.2 1184.09    6116 1193.64  6190.9 1212.55  6255.5 1225.96
#Mann= 13 ,-1 , 0
  4156.1      .1       0  4233.4     .05       0  4429.9      .1       0
  4627.7     .05       0  4925.1      .1       0  5001.3     .07       0
  5007.3      .1       0  5039.8     .05       0  5167.7      .1       0
  5278.5     .05       0    6003     .08       0    6116     .05       0
  6190.9     .16       0
Bank Sta=4894.9,5118.5
XS Rating Curve= 0 ,0
Exp/Cntr=0.3,0.1

Type RM Length L Ch R = 1 ,68543   ,405,405,405
BEGIN DESCRIPTION:
MILLER CREEK 102.0
END DESCRIPTION:
XS GIS Cut Line= 3
      2927669.77     10042585.26      2928023.93      10041408.2
      2927222.63     10040461.21
#Sta/Elev= 30
  3581.1 1182.99  3659.1 1180.96  3781.1 1178.32  3861.9 1171.23  3980.2  1160.7
  4053.6 1157.85  4166.2 1155.71  4364.3 1155.54  4369.1 1155.71  4633.7 1156.04
  4814.4 1148.49  4845.4 1147.32  4888.3 1135.53  4902.6 1129.62  4991.9 1123.26
  4994.6 1122.76  4997.9 1123.26  5030.8  1126.3  5072.9 1135.56    5108 1143.01
  5214.6 1151.08  5384.1 1152.72  5612.3  1155.6  5676.1 1161.05  5728.9 1161.47
  5793.8 1161.81  5881.5 1174.54  5966.4 1201.77  5982.2  1207.4  6050.8 1212.23
#Mann= 16 ,-1 , 0
  3581.1      .1       0  3659.1     .05       0  3861.9      .1       0
  4053.6     .16       0  4166.2      .1       0  4364.3     .16       0
  4369.1      .1       0  4814.4     .05       0  4991.9     .04       0
  4997.9     .05       0  5030.8      .1       0  5384.1     .05       0
  5728.9     .08       0  5793.8     .05       0  5966.4     .16       0
  5982.2     .05       0
#XS Ineff= 1 ,-1
 5130.27 5155.72 1144.31
Permanent Ineff=
       T
Bank Sta=4888.3,5072.9
XS Rating Curve= 0 ,0
Exp/Cntr=0.3,0.1

Type RM Length L Ch R = 1 ,68138   ,831,831,831
BEGIN DESCRIPTION:
MILLER CREEK 101.0
END DESCRIPTION:
XS GIS Cut Line= 4
      2927742.67     10042616.56      2928174.97     10041632.16
      2928305.18     10040585.29      2929008.29     10039340.52
#Sta/Elev= 30
  3361.6 1182.19  3441.6 1180.51  3467.6 1179.98  3817.4 1155.94  4211.2 1149.24
  4374.6 1149.89  4737.1 1148.91  4813.7 1140.36  4838.2 1134.07  4928.9 1122.37
  4974.8 1123.44  5077.1 1120.94  5079.8 1120.44  5083.1 1120.94  5113.3 1132.53
  5120.4 1135.24  5170.8 1132.31  5211.9 1140.66  5439.8 1148.17  5563.9 1151.15
  5677.2 1159.73  5723.2 1154.22  5840.6 1157.66  5961.5 1157.34  6392.2 1167.76
  6443.5 1168.58  6502.6  1169.1  6566.6 1176.08  6609.9 1196.57  6921.3 1279.88
#Mann= 20 ,-1 , 0
  3361.6      .1       0  3441.6     .05       0  3467.6      .1       0
  3817.4     .16       0  4211.2     .05       0  4374.6      .1       0
  4737.1     .05       0  4813.7      .1       0  4974.8     .05       0
  5077.1     .04       0  5083.1     .05       0  5113.3      .1       0
  5211.9     .16       0  5439.8     .05       0  5563.9     .08       0
  5840.6     .05       0  5961.5      .1       0  6392.2     .16       0
  6443.5     .05       0  6502.6     .16       0
#XS Ineff= 2 ,-1
 5131.31  5220.5 1136.18 5372.07  5549.2 1149.15
Permanent Ineff=
       T       T
Bank Sta=4838.2,5120.4
XS Rating Curve= 0 ,0
Exp/Cntr=0.3,0.1

Type RM Length L Ch R = 1 ,67307   ,851,851,851
BEGIN DESCRIPTION:
MILLER CREEK 100.0
END DESCRIPTION:
XS GIS Cut Line= 4
      2927992.65     10042842.27      2928846.84     10041765.84
       2929277.4     10040356.12      2929638.48     10040196.41
#Sta/Elev= 30
    3031  1180.2  3085.9 1180.17  3128.4 1179.68  3269.5 1176.07  3611.3 1154.49
  3689.2 1147.13  3966.8  1146.1  4679.2  1147.1    4840 1132.75  4856.9 1129.68
  5011.4 1117.26  5014.2 1116.76  5017.4 1117.26    5087 1133.66  5134.3 1138.73
  5210.4  1145.4  5390.4 1159.58  5554.9 1172.52  5590.1 1181.65  5658.6 1179.57
  5734.5    1183  5819.6 1187.63  5891.3 1193.47  5956.9 1204.11  5995.7 1216.65
  6071.1 1231.46  6094.4 1243.53  6146.4  1256.7    6193 1274.22    6274 1286.62
#Mann= 14 ,-1 , 0
    3031      .1       0  3085.9     .16       0  3128.4      .1       0
  3611.3     .16       0  3966.8     .05       0  4856.9      .1       0
  5011.4     .07       0  5017.4      .1       0  5134.3     .05       0
  5210.4     .16       0  5390.4     .05       0  5590.1     .08       0
  5734.5     .05       0  5819.6      .1       0
#XS Ineff= 2 , 0
          4644.6 1147.81
Permanent Ineff=
       T       T
Bank Sta=4840,5087
XS Rating Curve= 0 ,0
Exp/Cntr=0.3,0.1

Type RM Length L Ch R = 1 ,66456   ,596,596,596
BEGIN DESCRIPTION:
MILLER CREEK 99.0
END DESCRIPTION:
XS GIS Cut Line= 3
      2928673.24     10043210.28      2929485.73     10041842.23
      2930138.49     10041203.37
#Sta/Elev= 30
  3143.3 1177.28  3270.7 1174.93  3393.8 1171.69  3415.3 1168.16  3473.7 1150.68
  3582.9 1141.69  3688.3 1139.56  3765.4  1139.7  3828.7 1139.96  4712.8 1144.43
  4820.2 1139.44  4897.9 1129.91  4905.9 1128.95  5008.1 1114.86  5010.8 1114.36
  5014.1 1114.86  5060.5 1120.62    5140 1124.18  5166.7 1125.67  5173.7 1129.21
  5180.8 1132.73    5202 1152.64  5237.4 1155.98  5258.5 1165.69    5293 1167.13
  5331.6 1172.04  5477.9 1182.31  5539.2 1194.17  5569.7  1199.8  5647.8 1204.66
#Mann= 13 ,-1 , 0
  3143.3     .05       0  3270.7     .16       0  3582.9      .1       0
  3688.3     .05       0  3765.4      .1       0  3828.7     .05       0
  4905.9      .1       0  5008.1     .07       0  5014.1      .1       0
    5140     .05       0    5293     .16       0  5331.6      .1       0
  5539.2     .05       0
#XS Ineff= 2 , 0
         4718.18 1144.46
Permanent Ineff=
       T       T
Bank Sta=4897.9,5173.7
XS Rating Curve= 0 ,0
Exp/Cntr=0.3,0.1

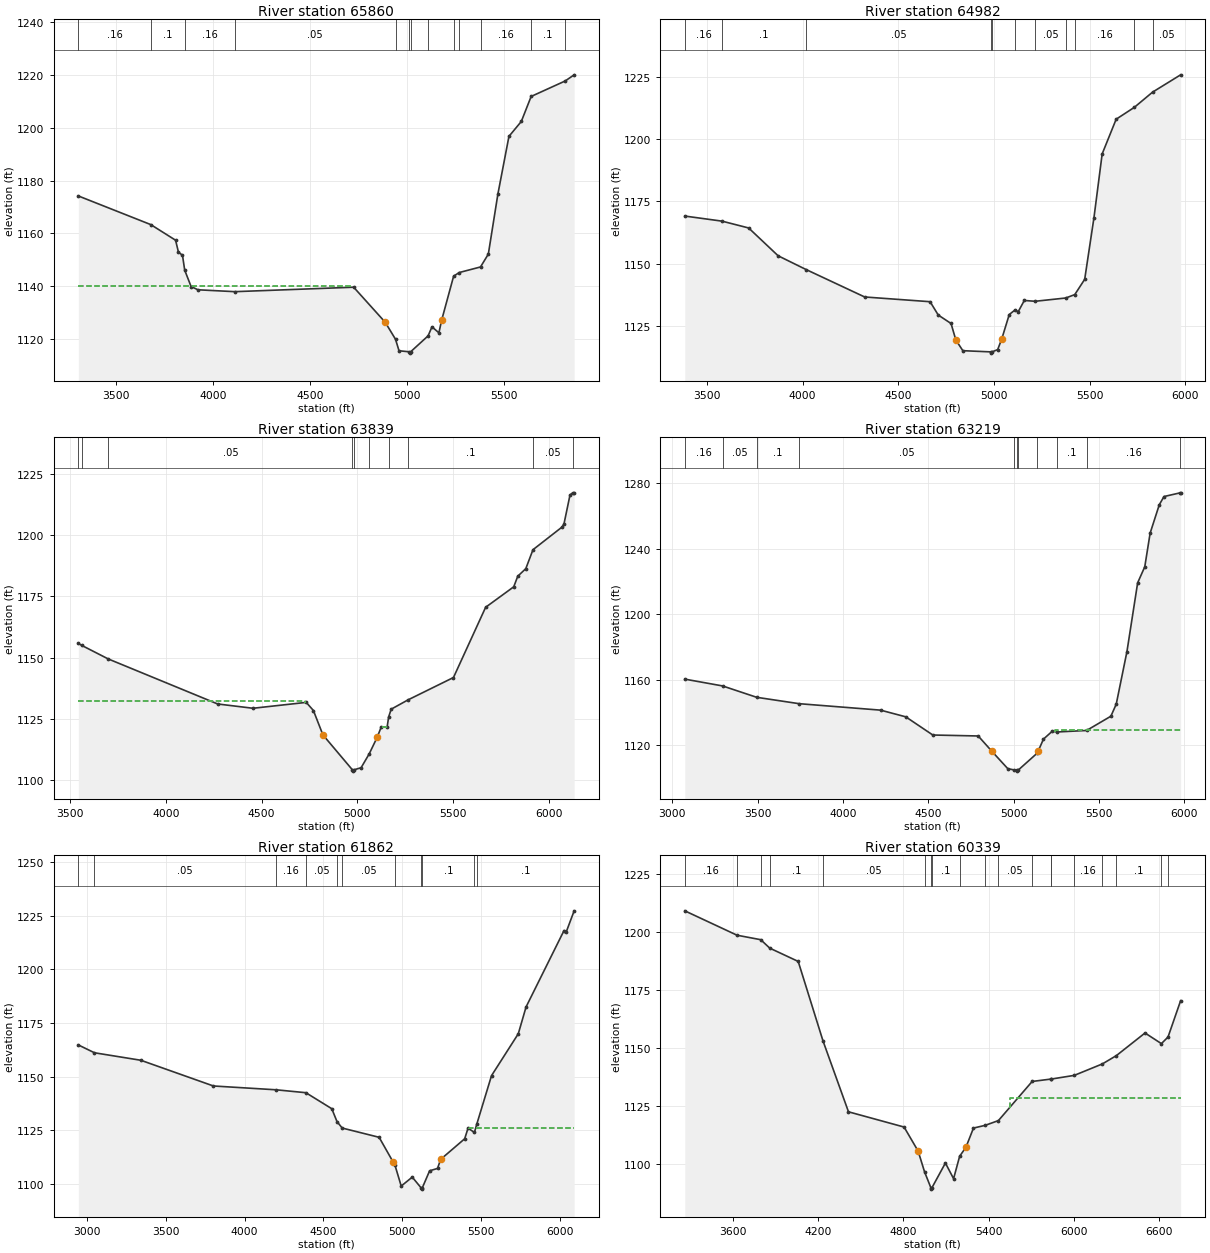
Type RM Length L Ch R = 1 ,65860   ,878,878,878
BEGIN DESCRIPTION:
MILLER CREEK 97.0
END DESCRIPTION:
XS GIS Cut Line= 3
      2929041.28     10043425.57      2929846.84     10042307.51
      2930707.98     10041508.88
#Sta/Elev= 30
  3306.7 1174.18  3679.8 1163.32  3807.3 1157.41    3822 1152.91  3842.9 1151.69
  3854.3 1146.07  3887.1 1139.87  3922.7 1138.63  4112.5 1137.92  4724.1 1139.61
  4886.8 1126.31  4939.6 1119.88  4957.6 1115.53  5011.3 1115.14    5014 1114.64
  5017.3 1115.14  5107.3 1121.18  5127.2  1124.6  5162.9 1122.34    5177  1127.1
  5238.7 1143.79  5267.6 1145.17  5377.1 1147.28  5417.4 1152.15  5466.8 1174.99
  5523.5 1196.75  5587.1 1202.39  5637.8 1211.87    5813 1217.73  5859.2 1220.06
#Mann= 13 ,-1 , 0
  3306.7     .16       0  3679.8      .1       0  3854.3     .16       0
  4112.5     .05       0  4939.6     .16       0  5011.3     .07       0
  5017.3     .16       0  5107.3     .05       0  5238.7     .16       0
  5267.6      .1       0  5377.1     .16       0  5637.8      .1       0
    5813     .05       0
#XS Ineff= 2 , 0
         4713.07 1139.95
Permanent Ineff=
       T       T
Bank Sta=4886.8,5177
XS Rating Curve= 0 ,0
Exp/Cntr=0.3,0.1

Type RM Length L Ch R = 1 ,64982   ,1143,1143,1143
BEGIN DESCRIPTION:
MILLER CREEK 96.0
END DESCRIPTION:
XS GIS Cut Line= 3
      2930034.34     10043967.24      2930680.18     10042876.95
      2931152.42      10041640.8
#Sta/Elev= 30
    3385 1169.14  3579.1  1167.1  3718.6 1164.35  3872.6 1153.17    4019 1147.63
  4324.9 1136.61  4666.6 1134.71  4709.2 1129.35  4776.1 1125.95  4800.9 1119.36
  4837.6 1115.02  4984.5 1114.54  4987.3 1114.04  4990.5 1114.54  5019.6 1115.45
    5041 1119.73  5080.1 1129.55  5111.7 1131.48  5126.7 1130.65  5158.8 1135.21
  5215.3 1134.88  5375.3  1136.2  5422.5 1137.57  5474.3 1143.71  5522.8 1168.53
  5565.6 1194.12  5638.7 1208.07  5733.4 1212.82  5828.9 1218.95  5975.5 1225.91
#Mann= 11 ,-1 , 0
    3385     .16       0  3579.1      .1       0    4019     .05       0
  4984.5    .033       0  4990.5     .05       0  5111.7      .1       0
  5215.3     .05       0  5375.3      .1       0  5422.5     .16       0
  5733.4      .1       0  5828.9     .05       0
Bank Sta=4800.9,5041
XS Rating Curve= 0 ,0
Exp/Cntr=0.3,0.1

Type RM Length L Ch R = 1 ,63839   ,620,620,620
BEGIN DESCRIPTION:
MILLER CREEK 93.0
END DESCRIPTION:
XS GIS Cut Line= 3
       2930923.2     10044036.71      2931701.01     10043328.34
      2932166.29     10041863.07
#Sta/Elev= 30
  3543.4 1155.83  3560.1 1155.04  3699.7 1149.47  4271.1 1131.12  4455.6 1129.37
  4733.6 1131.77  4771.1 1128.45  4820.6 1118.54    4975 1104.25  4977.7 1103.75
    4981 1104.25    5020 1105.13  5062.1 1110.73  5104.2 1117.56  5124.9 1121.66
  5156.3 1121.81  5163.9 1125.81  5177.3    1129  5265.7 1132.81  5502.6 1141.91
  5670.5 1170.53  5817.3 1178.88  5838.3 1183.19  5880.3 1186.28  5917.7 1193.99
  6069.2 1203.21  6079.6 1204.48  6111.1 1216.29  6124.6 1217.15  6132.8 1217.18
#Mann= 10 ,-1 , 0
  3543.4     .16       0  3560.1      .1       0  3699.7     .05       0
    4975    .035       0    4981     .05       0  5062.1      .1       0
  5163.9     .05       0  5265.7      .1       0  5917.7     .05       0
  6124.6      .1       0
#XS Ineff= 2 ,-1
  3543.4 4725.57 1132.14 5131.42 5163.17 1121.87
Permanent Ineff=
       T       T
Bank Sta=4820.6,5104.2
XS Rating Curve= 0 ,0
Exp/Cntr=0.3,0.1

Type RM Length L Ch R = 1 ,63219   ,1357,1357,1357
BEGIN DESCRIPTION:
MILLER CREEK 92.0
END DESCRIPTION:
XS GIS Cut Line= 4
      2930819.02     10044196.41      2931971.84     10043807.51
       2932589.9     10042904.73      2933159.39     10042731.11
#Sta/Elev= 30
  3073.1 1160.37  3294.5 1156.21  3494.6 1149.26  3743.5 1145.36  4220.5 1141.42
  4368.3 1137.33  4526.7 1126.22  4792.8 1125.63  4873.4 1116.22  4966.1 1105.67
    5003 1104.88    5020 1104.65  5022.7 1104.15    5026 1104.65  5139.7 1115.24
  5145.5 1116.69  5175.3 1123.72  5226.1 1128.46  5255.5 1128.08  5428.1 1128.99
  5570.5 1137.71  5601.9  1145.1  5664.6 1177.22  5727.3 1219.22  5769.1 1229.03
  5800.5 1249.58  5854.1 1266.93  5881.7 1271.95  5976.7 1274.22  5979.2 1274.22
#Mann= 11 ,-1 , 0
  3073.1     .16       0  3294.5     .05       0  3494.6      .1       0
  3743.5     .05       0    5003      .1       0    5020    .035       0
    5026      .1       0  5139.7     .05       0  5255.5      .1       0
  5428.1     .16       0  5976.7      .1       0
#XS Ineff= 2 , 0
                         5244.89         1129.29
Permanent Ineff=
       T       T
Bank Sta=4873.4,5145.5
XS Rating Curve= 0 ,0
Exp/Cntr=0.3,0.1

Type RM Length L Ch R = 1 ,61862   ,1523,1523,1523
BEGIN DESCRIPTION:
MILLER CREEK 90.0
END DESCRIPTION:
XS GIS Cut Line= 4
      2930622.57     10044418.04      2932289.26     10044322.56
      2933070.51     10044365.96      2933591.33      10043905.9
#Sta/Elev= 30
  2944.9 1164.81  3047.5 1161.16  3341.4 1157.68  3802.1 1145.71  4200.2 1143.93
    4389 1142.58  4553.4 1135.13  4586.6 1129.12  4619.6 1126.13  4853.9 1121.82
    4944 1110.16  4954.5 1108.82  4994.1 1099.13  5064.2 1103.29  5121.3  1098.2
  5124.1  1097.7  5127.3  1098.2  5174.4 1106.23  5224.5 1107.33  5244.5 1111.56
  5396.8 1121.13  5418.4  1126.1  5458.7 1124.06  5473.3 1127.85  5567.3 1150.52
  5737.2 1170.02  5786.5  1182.5  6027.4 1218.06  6041.6 1217.43  6091.7 1227.23
#Mann= 11 ,-1 , 0
  2944.9     .16       0  3047.5     .05       0  4200.2     .16       0
    4389     .05       0  4586.6      .1       0  4619.6     .05       0
  4954.5      .1       0  5121.3     .07       0  5127.3      .1       0
  5458.7     .05       0  5473.3      .1       0
#XS Ineff= 2 , 0
                         5427.27         1126.26
Permanent Ineff=
       T       T
Bank Sta=4944,5244.5
XS Rating Curve= 0 ,0
Exp/Cntr=0.3,0.1

Type RM Length L Ch R = 1 ,60339   ,1286,1286,1286
BEGIN DESCRIPTION:
MILLER CREEK 88.0
END DESCRIPTION:
XS GIS Cut Line= 4
      2931872.61     10046674.98       2932810.1     10045789.57
      2933712.87     10045390.26      2933877.81     10044192.32
#Sta/Elev= 30
    3264 1209.09  3631.2 1198.59  3797.9 1196.66  3861.1 1193.03  4061.3  1187.3
  4235.6 1153.09  4414.8 1122.55  4805.7 1115.99  4904.4 1105.64  4949.5 1096.73
  4994.6 1089.76  4997.3 1089.26  5000.6 1089.76  5096.2  1100.5  5153.7 1093.76
  5196.2 1103.39  5240.6  1107.3  5293.5 1115.55  5375.6 1116.72  5468.8 1118.77
  5706.1 1135.62  5838.5 1136.65  5839.1 1136.64  6002.2 1138.24  6199.7 1143.17
  6298.4 1146.76  6499.6 1156.49  6614.7 1151.91  6661.3 1154.75  6749.9  1170.4
#Mann= 19 ,-1 , 0
    3264     .16       0  3631.2      .1       0  3797.9     .16       0
  3861.1      .1       0  4235.6     .05       0  4949.5      .1       0
  4994.6     .07       0  5000.6      .1       0  5196.2     .05       0
  5375.6     .16       0  5468.8     .05       0  5706.1      .1       0
  5838.5     .05       0  5839.1      .1       0  6002.2     .16       0
  6199.7     .05       0  6298.4      .1       0  6614.7     .05       0
  6661.3      .1       0
#XS Ineff= 2 , 0
                         5547.73         1128.54
Permanent Ineff=
       T       T
Bank Sta=4904.4,5240.6
XS Rating Curve= 0 ,0
Exp/Cntr=0.3,0.1

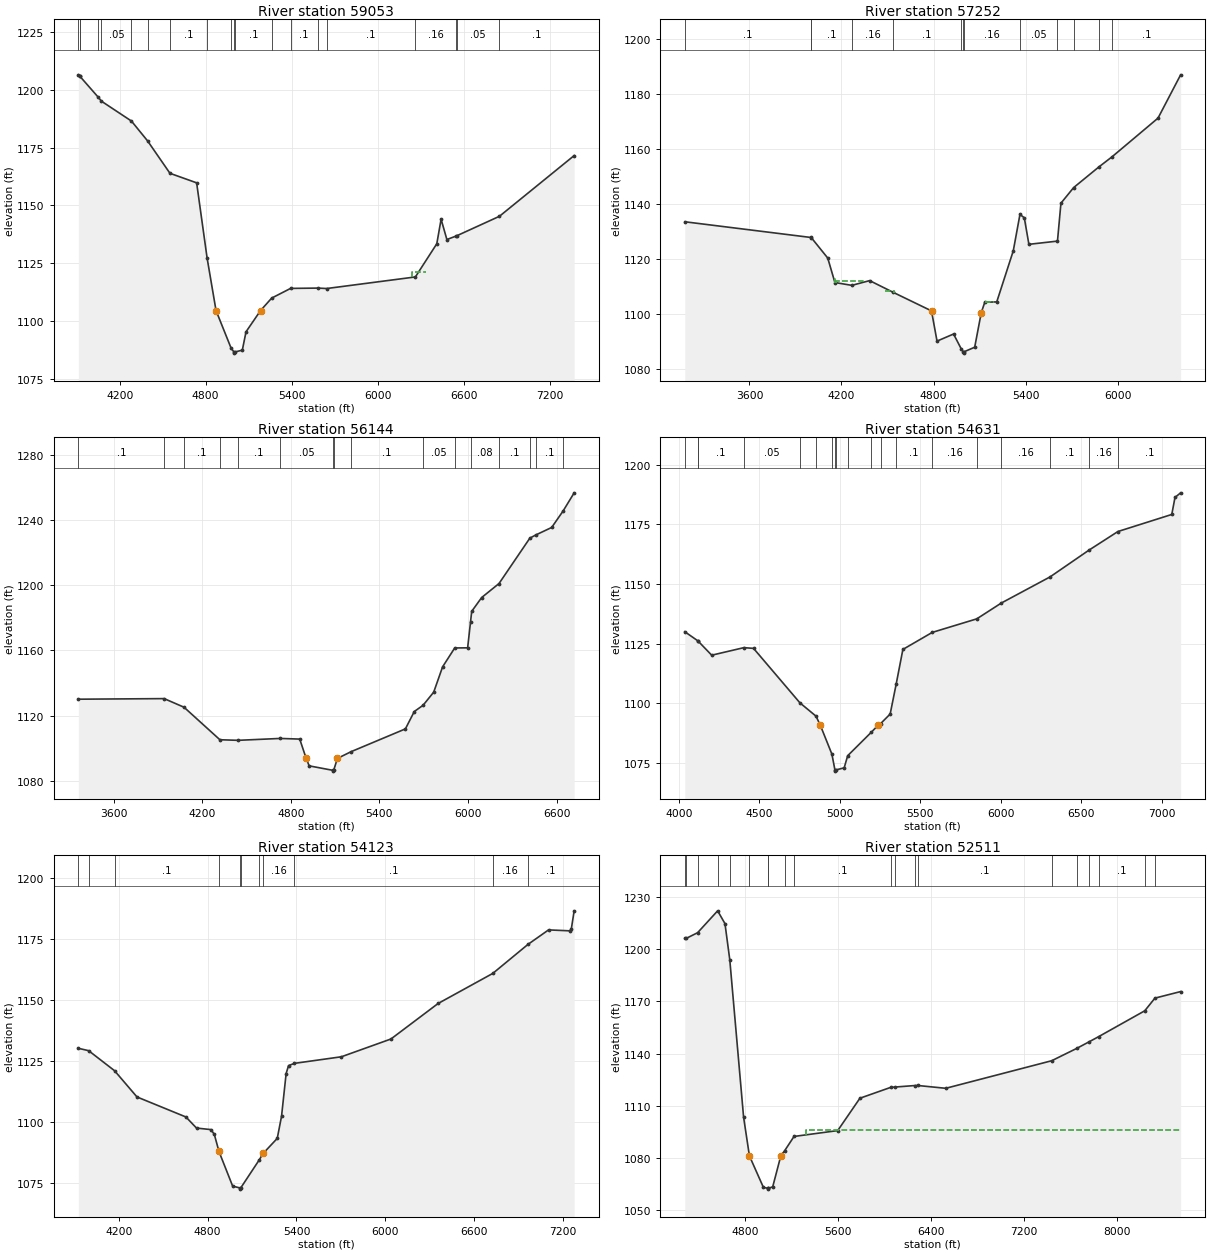
Type RM Length L Ch R = 1 ,59053   ,1801,1801,1801
BEGIN DESCRIPTION:
MILLER CREEK 86.0
END DESCRIPTION:
XS GIS Cut Line= 4
      2933573.39     10047391.15      2934026.53     10046896.34
      2934182.78     10045948.42      2933984.87     10044130.72
#Sta/Elev= 30
  3911.8  1206.4  3920.4 1205.91  3921.8 1205.83  4050.2 1196.77  4072.5 1195.04
  4282.3 1186.45  4395.4 1177.85  4551.3 1163.88  4737.4 1159.77  4810.4 1127.32
  4872.8 1104.62  4978.3 1088.34  4997.9 1086.75  5000.7 1086.25  5003.9 1086.75
  5056.2 1087.53    5082 1095.46  5183.6 1104.65  5261.1 1110.01  5392.9 1114.19
  5583.4 1114.33  5644.9 1114.14  6263.9 1119.14  6413.3 1133.46  6443.4 1144.04
  6483.7  1135.3  6546.8 1136.76  6552.2  1136.9  6850.4 1145.32  7371.9 1171.54
#Mann= 20 ,-1 , 0
  3911.8     .05       0  3920.4      .1       0  3921.8     .05       0
  4050.2      .1       0  4072.5     .05       0  4282.3      .1       0
  4395.4     .05       0  4551.3      .1       0  4810.4     .16       0
  4978.3      .1       0  4997.9     .07       0  5003.9      .1       0
  5261.1     .05       0  5392.9      .1       0  5583.4     .05       0
  5644.9      .1       0  6263.9     .16       0  6546.8      .1       0
  6552.2     .05       0  6850.4      .1       0
#XS Ineff= 2 ,-1
 5697.73 5890.91 1114.34 6238.64 6336.36 1121.18
Permanent Ineff=
       T       T
Bank Sta=4872.8,5183.6
XS Rating Curve= 0 ,0
Exp/Cntr=0.3,0.1

Type RM Length L Ch R = 1 ,57252   ,1108,1108,1108
BEGIN DESCRIPTION:
MILLER CREEK 84.0
END DESCRIPTION:
XS GIS Cut Line= 3
      2934490.08     10046714.02      2935083.82     10045359.88
      2934100.09      10043907.7
#Sta/Elev= 30
  3178.4 1133.53  4000.3 1127.83  4002.7  1127.8  4110.3 1120.36    4157 1111.47
  4267.2 1110.44  4383.7 1112.16  4538.3 1107.87  4786.8 1101.17  4822.8 1090.19
  4930.6 1092.77  4979.7 1087.48  4993.5 1086.33  4996.2 1085.83  4999.5 1086.33
  5068.4 1087.97  5111.3 1100.54  5134.2 1104.31  5212.2 1104.43    5320 1122.98
  5363.5  1136.2  5391.9 1134.97  5421.8 1125.34  5608.1 1126.51  5630.7 1140.28
  5713.5 1145.94  5877.3 1153.41  5963.2 1157.09  6263.6 1171.17    6411 1186.89
#Mann= 13 ,-1 , 0
  3178.4      .1       0  4000.3     .16       0  4002.7      .1       0
  4267.2     .16       0  4538.3      .1       0  4979.7     .16       0
  4993.5     .07       0  4999.5     .16       0  5363.5     .05       0
  5608.1     .16       0  5713.5      .1       0  5877.3     .16       0
  5963.2      .1       0
#XS Ineff= 4 ,-1
 4148.96 4160.82 1112.91 4166.01 4337.23 1111.87 4483.99 4541.81 1108.34
 5134.78 5193.34 1104.34
Permanent Ineff=
       T       T       T       T
Bank Sta=4786.8,5111.3
XS Rating Curve= 0 ,0
Exp/Cntr=0.3,0.1

Type RM Length L Ch R = 1 ,56144   ,1513,1513,1513
BEGIN DESCRIPTION:
MILLER CREEK 82.0
END DESCRIPTION:
XS GIS Cut Line= 4
       2934745.3     10046552.57      2935490.07     10045568.22
      2936135.91     10045036.97      2937270.25     10044428.17
#Sta/Elev= 30
  3361.4 1130.09  3942.8 1130.45  4077.4 1125.16  4320.1 1105.25  4442.6 1104.89
  4728.9 1106.05  4860.8 1105.65  4903.9 1093.97  4924.7 1089.25  5084.6 1086.52
  5087.3 1086.02  5090.6 1086.52  5116.2 1093.82  5208.8 1097.94  5576.5  1111.9
  5636.6 1122.54  5695.8 1126.34  5768.2 1134.41  5828.3  1149.9  5910.5 1161.49
    5998 1161.57  6017.7 1177.53  6025.6 1183.93  6093.2  1192.4  6210.5 1200.96
  6419.4 1228.78  6459.6 1230.73  6567.2 1235.32    6645 1245.48  6719.4 1256.54
#Mann= 16 ,-1 , 0
  3361.4      .1       0  3942.8     .05       0  4077.4      .1       0
  4320.1     .16       0  4442.6      .1       0  4728.9     .05       0
  5084.6    .035       0  5090.6     .05       0  5208.8      .1       0
  5695.8     .05       0  5910.5      .1       0  6017.7     .08       0
  6210.5      .1       0  6419.4     .16       0  6459.6      .1       0
    6645     .16       0
Bank Sta=4903.9,5116.2
XS Rating Curve= 0 ,0
Exp/Cntr=0.3,0.1

Type RM Length L Ch R = 1 ,54631   ,508,508,508
BEGIN DESCRIPTION:
MILLER CREEK 80.0
END DESCRIPTION:
XS GIS Cut Line= 4
      2934771.31     10046672.38      2935297.37     10046651.55
      2936557.78     10046922.38      2937823.42     10046854.67
#Sta/Elev= 30
  4035.6 1130.04  4117.5 1126.19  4119.9 1126.01  4202.9 1120.21  4402.9 1123.37
  4463.1 1123.07  4751.5 1100.25  4851.5 1094.68  4878.5 1090.83  4950.2  1078.8
  4969.1 1072.16  4971.9 1071.66  4975.1 1072.16  5026.6 1073.04  5048.5 1078.12
  5196.1 1087.99  5238.3 1090.93  5253.5 1091.58  5312.6 1095.57  5349.6 1107.97
  5391.7 1122.63  5574.4 1129.76  5851.2 1135.43  6003.9 1142.06  6306.9    1153
  6548.6  1164.2  6728.9 1172.01  7063.7 1179.15  7083.7 1186.28  7118.7 1188.21
#Mann= 19 ,-1 , 0
  4035.6      .1       0  4117.5     .05       0  4119.9      .1       0
  4402.9     .05       0  4751.5      .1       0  4851.5     .05       0
  4950.2      .1       0  4969.1     .07       0  4975.1      .1       0
  5048.5     .05       0  5196.1      .1       0  5253.5     .16       0
  5349.6      .1       0  5574.4     .16       0  5851.2      .1       0
  6003.9     .16       0  6306.9      .1       0  6548.6     .16       0
  6728.9      .1       0
Bank Sta=4878.5,5238.3
XS Rating Curve= 0 ,0
Exp/Cntr=0.3,0.1

Type RM Length L Ch R = 1 ,54123   ,1612,1612,1612
BEGIN DESCRIPTION:
MILLER CREEK 79.0
END DESCRIPTION:
XS GIS Cut Line= 4
      2934677.54     10046682.78      2935396.32      10047182.8
      2936125.49      10047370.3      2937807.74     10047000.52
#Sta/Elev= 30
    3926 1130.17  3995.8 1129.19  4170.8    1121  4322.4 1110.27  4653.2 1102.08
  4724.7 1097.55  4822.4 1096.92  4845.1 1094.96  4876.3    1088    4969  1073.8
  5017.6 1073.08  5020.4 1072.58  5023.6 1073.08  5148.8 1084.55  5172.7 1086.98
  5175.5 1087.21  5270.4 1093.33  5299.4  1102.4  5330.4 1119.85  5346.7 1123.09
  5386.8 1124.01  5703.8  1126.7  6038.8 1133.97  6357.4 1148.49    6727 1160.79
  6964.3 1172.63  7103.8 1178.58  7246.9  1178.2  7257.2 1178.76  7276.9 1186.38
#Mann= 11 ,-1 , 0
    3926      .1       0  3995.8     .05       0  4170.8      .1       0
  4876.3     .16       0  5017.6     .07       0  5023.6     .16       0
  5148.8      .1       0  5172.7     .16       0  5386.8      .1       0
    6727     .16       0  6964.3      .1       0
Bank Sta=4876.3,5175.5
XS Rating Curve= 0 ,0
Exp/Cntr=0.3,0.1

Type RM Length L Ch R = 1 ,52511   ,2054,2054,2054
BEGIN DESCRIPTION:
MILLER CREEK 76.0
END DESCRIPTION:
XS GIS Cut Line= 4
      2933823.41     10048318.21      2935099.45     10048286.97
      2935917.16     10047573.42      2937807.78     10047401.55
#Sta/Elev= 30
  4285.2  1206.4  4296.5 1206.25  4395.3 1209.54  4567.3 1222.12  4630.4 1214.76
  4671.7 1193.97  4790.4 1103.43  4840.4 1081.21  4960.5  1063.1  4997.5 1062.59
  5000.2 1062.09  5003.5 1062.59  5040.5  1063.4  5110.5  1081.3  5143.1 1084.16
  5223.6 1092.38    5599 1095.75  5789.8 1114.36  6053.4 1120.58  6087.4 1120.77
  6259.7 1121.64  6286.7 1121.68  6527.4 1120.07  7437.5 1135.92  7651.1 1142.96
  7762.2 1146.92  7840.6 1149.76  8236.9 1164.63  8324.6 1171.92  8545.3 1175.69
#Mann= 20 ,-1 , 0
  4285.2     .05       0  4296.5     .16       0  4395.3     .05       0
  4567.3      .1       0  4671.7     .05       0  4840.4      .1       0
  4997.5     .07       0  5003.5      .1       0  5143.1     .16       0
  5223.6      .1       0  6053.4     .05       0  6087.4      .1       0
  6259.7     .05       0  6286.7      .1       0  7437.5     .16       0
  7651.1      .1       0  7762.2     .16       0  7840.6      .1       0
  8236.9     .16       0  8324.6      .1       0
#XS Ineff= 2 , 0
                         5323.86         1096.05
Permanent Ineff=
       T       T
Bank Sta=4840.4,5110.5
XS Rating Curve= 0 ,0
Exp/Cntr=0.3,0.1