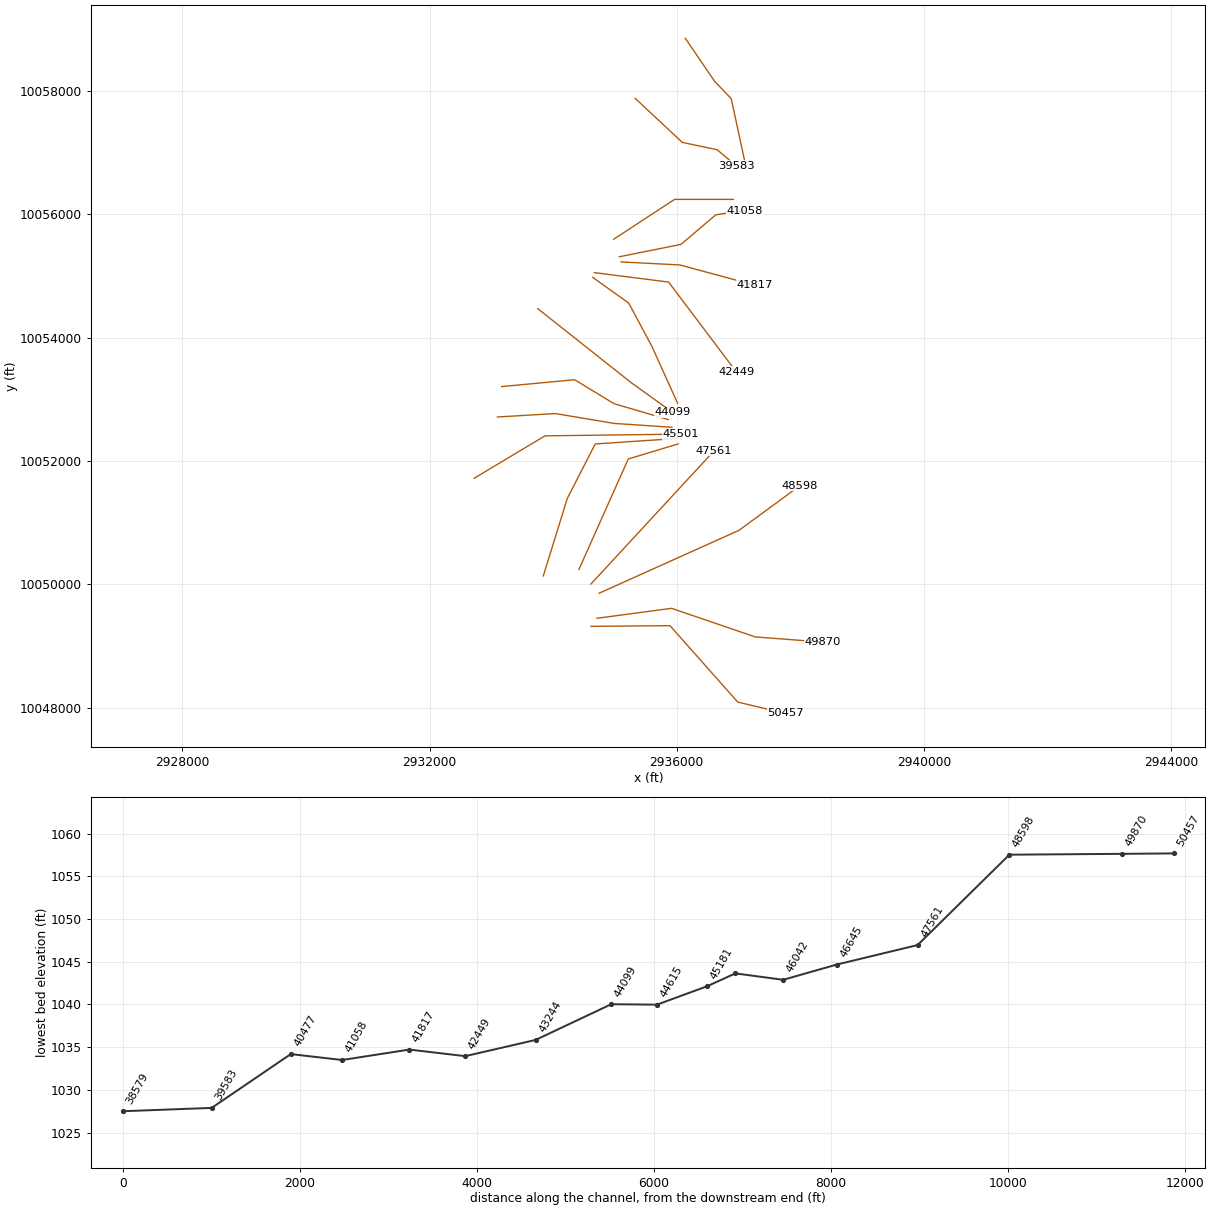
HEC-RAS study MILLER CREEK.prj: MILLER CREEK Base Level Engineering

--- MILLER CREEK.g01 (geometry) --- (continued)

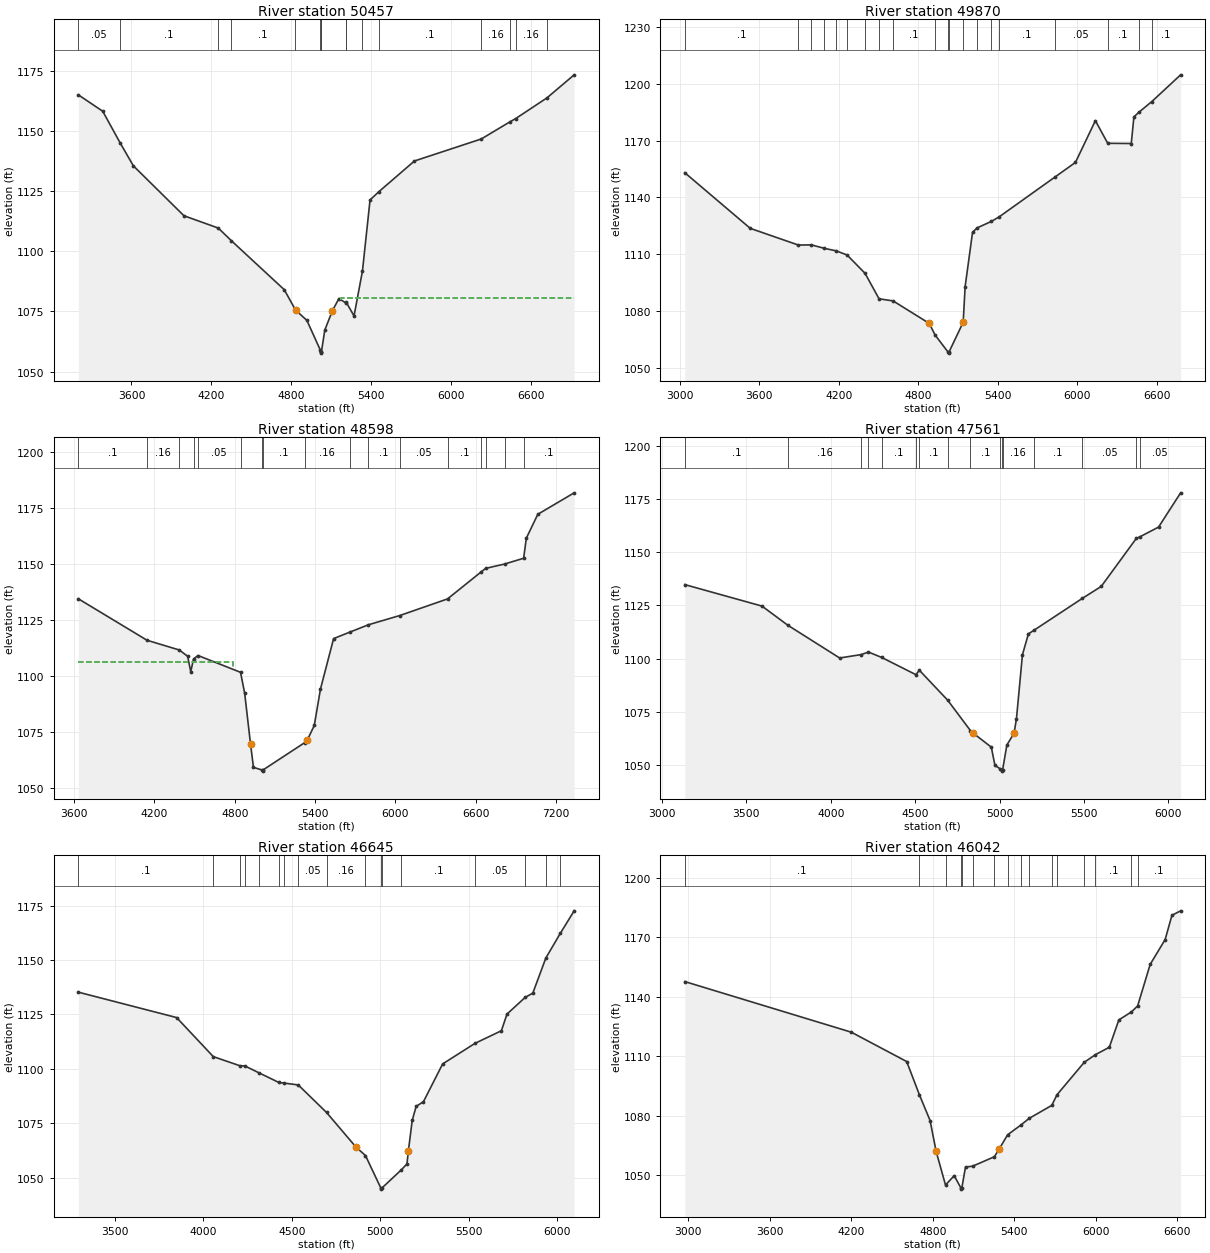
Type RM Length L Ch R = 1 ,50457   ,587,587,587
BEGIN DESCRIPTION:
MILLER CREEK 74.0
END DESCRIPTION:
XS GIS Cut Line= 4
       2934615.1     10049318.22      2935891.12     10049328.63
      2936990.07     10048089.05      2937760.87     10047906.76
#Sta/Elev= 30
  3200.8 1164.94  3384.2 1158.12  3513.9 1145.08  3614.2 1135.46  3994.2 1114.73
    4252 1109.62  4350.7 1104.35  4747.9 1084.01  4828.4 1075.98  4832.3 1075.57
  4917.6 1071.29  5018.6 1058.94  5020.9 1058.18  5023.6 1057.68  5026.9 1058.18
  5052.3 1067.25  5109.2 1075.27  5158.5 1080.36  5208.5 1078.58  5214.4 1078.71
  5271.9 1073.11  5335.2  1091.8  5392.2 1121.29  5456.6 1124.63  5725.6 1137.47
  6228.2 1146.62  6441.9 1153.69  6486.7  1155.1  6721.5 1163.69  6925.5 1173.25
#Mann= 16 ,-1 , 0
  3200.8     .05       0  3513.9      .1       0    4252     .05       0
  4350.7      .1       0  4828.4     .16       0  5018.6      .1       0
  5020.9     .07       0  5026.9      .1       0  5208.5     .05       0
  5214.4      .1       0  5335.2     .16       0  5456.6      .1       0
  6228.2     .16       0  6441.9      .1       0  6486.7     .16       0
  6721.5      .1       0
#XS Ineff= 2 , 0
                         5172.73         1080.65
Permanent Ineff=
       T       T
Bank Sta=4832.3,5109.2
XS Rating Curve= 0 ,0
Exp/Cntr=0.3,0.1

Type RM Length L Ch R = 1 ,49870   ,1272,1272,1272
BEGIN DESCRIPTION:
MILLER CREEK 73.0
END DESCRIPTION:
XS GIS Cut Line= 4
      2934708.86     10049448.43      2935917.16     10049609.88
      2937271.32     10049146.34       2938359.9       10049063.
#Sta/Elev= 30
  3037.7 1153.11  3531.7 1123.66  3895.1 1114.82    3993 1114.92    4092 1113.07
  4180.8 1111.74  4262.4 1109.57    4398 1099.87  4503.9 1086.37  4609.7 1085.27
  4882.4 1073.38  4927.2 1067.15  5025.3 1058.13  5028.1 1057.63  5031.3 1058.13
  5138.8 1073.97  5153.5 1092.87  5209.4 1121.57  5244.6 1123.94  5350.5  1127.3
  5409.5 1129.71  5829.5 1150.72  5986.1 1158.56  6136.5 1180.66  6229.7 1168.66
  6407.3 1168.56  6427.3 1182.66  6463.4 1185.01  6562.7 1190.78  6779.8 1204.91
#Mann= 20 ,-1 , 0
  3037.7      .1       0  3895.1     .16       0    3993      .1       0
    4092     .05       0  4180.8      .1       0  4262.4     .05       0
    4398      .1       0  4503.9     .16       0  4609.7      .1       0
  4927.2     .05       0  5025.3    .035       0  5031.3     .05       0
  5138.8     .16       0  5244.6      .1       0  5350.5     .05       0
  5409.5      .1       0  5829.5     .05       0  6229.7      .1       0
  6463.4     .05       0  6562.7      .1       0
Bank Sta=4882.4,5138.8
XS Rating Curve= 0 ,0
Exp/Cntr=0.3,0.1

Type RM Length L Ch R = 1 ,48598   ,1037,1037,1037
BEGIN DESCRIPTION:
MILLER CREEK 71.0
END DESCRIPTION:
XS GIS Cut Line= 3
      2934745.27     10049854.67      2937010.91     10050875.51
      2937993.89     10051598.44
#Sta/Elev= 30
  3631.2 1134.55  4144.3 1116.02  4385.8 1111.66  4448.1 1108.84  4471.3 1101.96
    4492 1107.61  4525.2  1109.2  4843.2  1101.7  4874.1  1092.4    4918 1069.66
  4939.9 1059.21  5004.7 1058.03  5007.5 1057.53  5010.7 1058.03  5324.4 1070.32
  5342.7 1071.46  5394.4 1077.94  5440.7 1094.22  5538.8 1116.75    5660 1119.65
  5798.6 1122.93    6033 1127.06  6390.2 1134.49  6641.4 1146.57  6674.7 1148.14
  6817.6 1150.09  6958.8 1152.67  6979.2 1161.66  7064.8 1172.31  7336.4  1181.9
#Mann= 17 ,-1 , 0
  3631.2      .1       0  4144.3     .16       0  4385.8      .1       0
    4492     .16       0  4525.2     .05       0  4843.2      .1       0
  5004.7     .07       0  5010.7      .1       0  5324.4     .16       0
    5660     .05       0  5798.6      .1       0    6033     .05       0
  6390.2      .1       0  6641.4     .05       0  6674.7      .1       0
  6817.6     .05       0  6958.8      .1       0
#XS Ineff= 2 , 0
         4788.64 1106.28
Permanent Ineff=
       T       T
Bank Sta=4918,5342.7
XS Rating Curve= 0 ,0
Exp/Cntr=0.3,0.1

Type RM Length L Ch R = 1 ,47561   ,916,916,916
BEGIN DESCRIPTION:
MILLER CREEK 70.0
END DESCRIPTION:
XS GIS Cut Line= 2
      2934612.44     10050003.51      2936604.47     10052162.12
#Sta/Elev= 30
  3135.2 1134.83  3592.6  1124.7  3745.6 1115.68  4052.5 1100.26  4179.8 1101.85
  4223.3 1103.05  4301.8  1100.5  4503.9 1092.41    4525 1094.46  4692.9 1080.34
  4827.3 1066.04  4845.2 1064.77  4951.2 1058.22  4972.5 1049.61  5004.6 1048.02
  5011.7 1047.45  5014.5 1046.95  5017.7 1047.45  5043.1 1059.23  5085.6 1064.81
  5099.8 1071.51  5135.5  1101.8  5170.7  1111.6  5203.8 1113.33  5490.4 1128.35
  5602.2 1133.97  5810.6 1156.66  5829.8 1157.29  5941.9 1161.94  6072.5 1178.07
#Mann= 16 ,-1 , 0
  3135.2      .1       0  3745.6     .16       0  4179.8      .1       0
  4223.3     .05       0  4301.8      .1       0  4503.9     .16       0
    4525      .1       0  4692.9     .16       0  4827.3      .1       0
  5004.6     .16       0  5011.7     .07       0  5017.7     .16       0
  5203.8      .1       0  5490.4     .05       0  5810.6      .1       0
  5829.8     .05       0
Bank Sta=4845.2,5085.6
XS Rating Curve= 0 ,0
Exp/Cntr=0.3,0.1

Type RM Length L Ch R = 1 ,46645   ,603,603,603
BEGIN DESCRIPTION:
MILLER CREEK 69.0
END DESCRIPTION:
XS GIS Cut Line= 3
      2934418.02     10050239.64      2935216.64     10052031.32
      2936022.15     10052274.37
#Sta/Elev= 30
  3292.9 1135.22  3848.5 1123.54  4055.8 1105.59  4206.9 1101.37  4234.8 1101.28
  4316.7 1098.03  4426.5  1093.7    4456 1093.42  4536.2 1092.56  4695.9 1079.92
    4863 1063.95  4916.3 1060.09    5003 1045.16  5005.7 1044.66    5009 1045.16
  5119.6 1053.58  5150.8 1056.27  5158.6 1062.17  5180.5 1076.27  5202.7 1082.73
  5243.7 1084.83  5352.5 1102.23  5535.9 1111.71  5684.7 1117.49    5716 1125.13
  5818.6 1132.79  5862.3  1134.8  5935.9 1150.94  6017.5 1162.25  6095.9 1172.62
#Mann= 17 ,-1 , 0
  3292.9      .1       0  4055.8     .16       0  4206.9      .1       0
  4234.8     .16       0  4316.7      .1       0  4426.5     .05       0
    4456      .1       0  4536.2     .05       0  4695.9     .16       0
  4916.3     .05       0    5003    .035       0    5009     .05       0
  5119.6      .1       0  5535.9     .05       0  5818.6      .1       0
  5935.9     .05       0  6017.5      .1       0
Bank Sta=4863,5158.6
XS Rating Curve= 0 ,0
Exp/Cntr=0.3,0.1

Type RM Length L Ch R = 1 ,46042   ,541,541,541
BEGIN DESCRIPTION:
MILLER CREEK 68.0
END DESCRIPTION:
XS GIS Cut Line= 4
      2933841.63     10050135.48      2934230.53     10051392.43
      2934681.91     10052274.38       2936022.2     10052364.66
#Sta/Elev= 30
  2974.6 1147.71  4200.8 1122.13    4608 1107.32  4702.2 1090.42  4780.1 1077.54
  4824.5 1061.99  4893.7 1044.96  4957.7 1049.68  5007.7 1043.38  5010.5 1042.88
  5013.7 1043.38  5040.9 1054.06  5092.9 1054.45  5253.3 1059.23  5287.6 1062.99
  5350.6  1070.3  5449.2 1075.29    5509  1078.6  5676.4  1085.2  5714.1 1090.52
  5914.8 1106.92  5997.2 1110.79  6099.5 1114.54  6169.6 1128.34  6262.6  1132.4
    6308 1135.41  6400.2 1156.38  6510.4 1168.92  6560.5 1181.19  6624.4 1183.44
#Mann= 16 ,-1 , 0
  2974.6      .1       0  4702.2     .16       0  4893.7      .1       0
  5007.7     .07       0  5013.7      .1       0  5092.9     .05       0
  5253.3     .16       0  5350.6      .1       0  5449.2     .05       0
    5509      .1       0  5676.4     .16       0  5714.1      .1       0
  5914.8     .05       0  5997.2      .1       0  6262.6     .05       0
    6308      .1       0
Bank Sta=4824.5,5287.6
XS Rating Curve= 0 ,0
Exp/Cntr=0.3,0.1

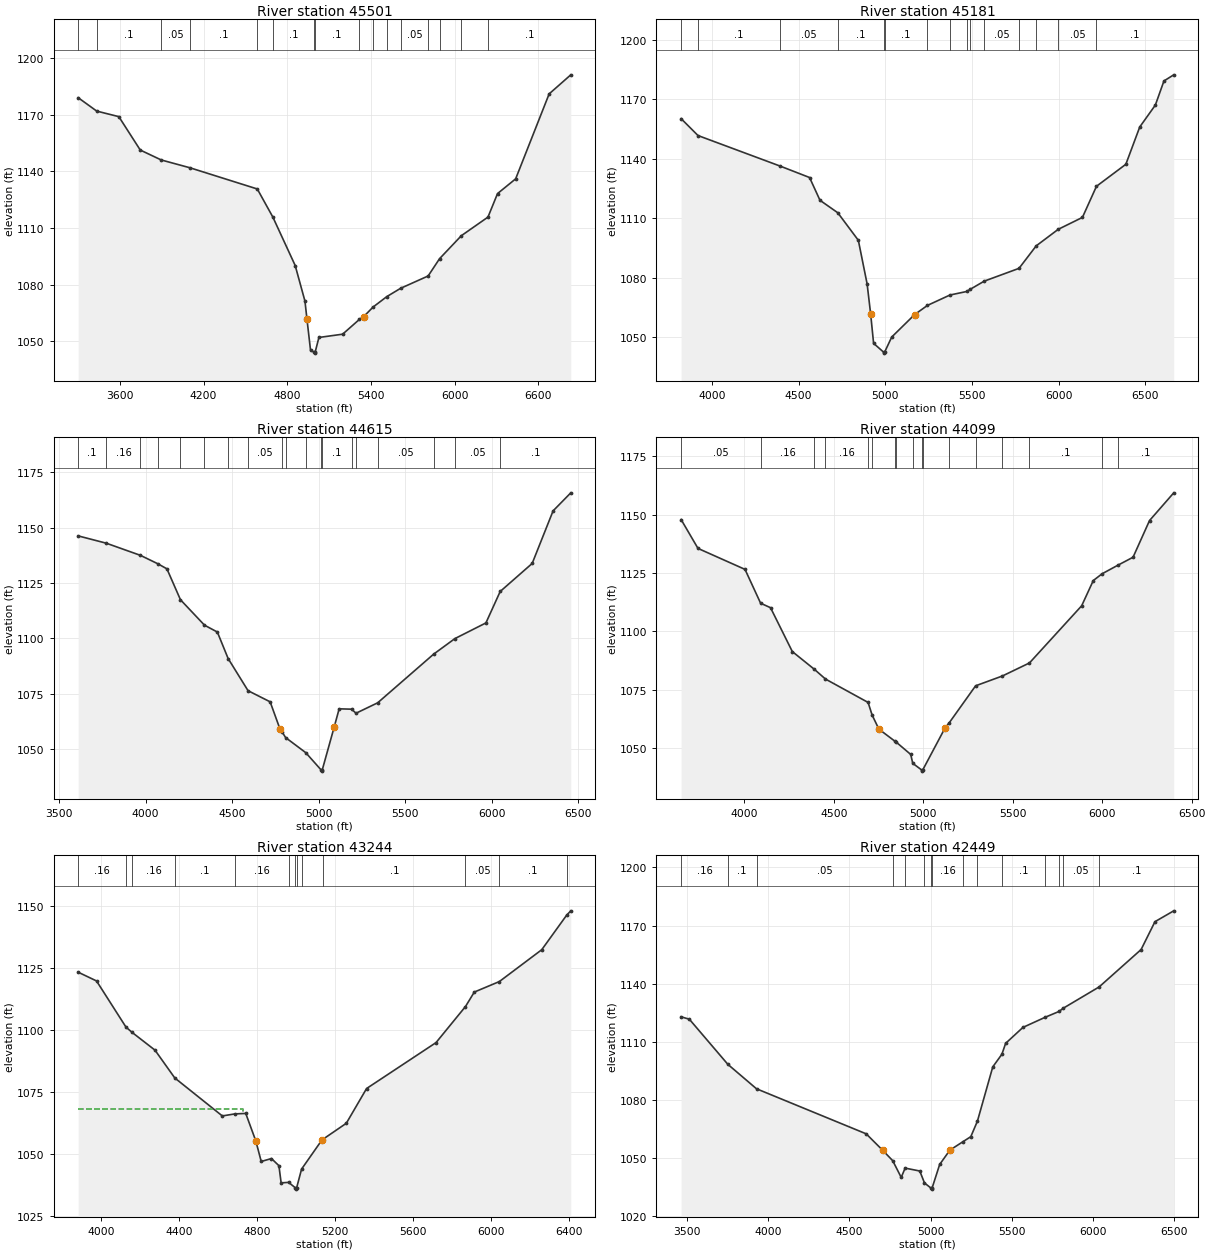
Type RM Length L Ch R = 1 ,45501   ,320,320,320
BEGIN DESCRIPTION:
MILLER CREEK 67.0
END DESCRIPTION:
XS GIS Cut Line= 3
      2932723.54      10051718.8      2933869.41     10052406.32
      2936063.63      10052434.1
#Sta/Elev= 30
  3301.1 1179.03    3434 1171.93  3592.5 1168.98  3746.1 1151.28  3896.4 1146.02
  4102.8 1141.87  4584.9 1130.64  4696.5 1115.73  4856.5 1090.07  4926.5  1071.2
 4940.91 1061.63  4966.5 1045.14  4993.5 1044.13  4996.2 1043.63  4999.5 1044.13
  5026.5 1051.93  5196.5 1053.67  5316.2 1061.47  5346.5 1062.92  5414.8 1068.06
  5513.4  1073.6    5612 1077.99  5809.3 1084.52    5891 1093.67  6047.4 1105.88
  6238.2 1115.74  6306.6 1128.19  6436.6 1136.02  6676.6 1181.05  6831.8 1191.15
#Mann= 16 ,-1 , 0
  3301.1     .05       0    3434      .1       0  3896.4     .05       0
  4102.8      .1       0  4584.9     .05       0  4696.5      .1       0
  4993.5     .07       0  4999.5      .1       0  5316.2     .16       0
  5414.8      .1       0  5513.4     .16       0    5612     .05       0
  5809.3     .16       0    5891      .1       0  6047.4     .05       0
  6238.2      .1       0
Bank Sta=4940.91,5346.5
XS Rating Curve= 0 ,0
Exp/Cntr=0.3,0.1

Type RM Length L Ch R = 1 ,45181   ,566,566,566
BEGIN DESCRIPTION:
MILLER CREEK 66.0
END DESCRIPTION:
XS GIS Cut Line= 4
      2933098.55     10052711.88      2934036.08     10052767.43
      2934987.47     10052607.71      2935924.21     10052545.26
#Sta/Elev= 30
  3821.8  1160.3  3919.2 1151.79  4394.2 1136.36    4563 1130.63  4623.1 1119.16
  4725.8 1112.87  4844.5 1098.98  4895.2 1076.96  4915.5 1061.84  4932.5 1047.05
  4990.1 1042.62  4992.9 1042.12  4996.1 1042.62  5037.2 1050.24    5169 1061.53
  5243.4 1066.18  5373.3 1071.41  5471.1 1073.21  5489.9 1074.28  5570.9  1078.4
  5771.7 1084.85  5870.8 1096.18  5997.9 1104.52  6137.6 1110.53  6218.6 1126.21
  6388.1  1137.3  6468.3  1156.1  6558.5 1167.16    6608 1179.31  6664.5 1182.39
#Mann= 15 ,-1 , 0
  3821.8     .16       0  3919.2      .1       0  4394.2     .05       0
  4725.8      .1       0  4990.1     .07       0  4996.1      .1       0
  5243.4     .05       0  5373.3      .1       0  5471.1     .05       0
  5489.9     .16       0  5570.9     .05       0  5771.7      .1       0
  5870.8     .16       0  5997.9     .05       0  6218.6      .1       0
Bank Sta=4915.5,5169
XS Rating Curve= 0 ,0
Exp/Cntr=0.3,0.1

Type RM Length L Ch R = 1 ,44615   ,516,516,516
BEGIN DESCRIPTION:
MILLER CREEK 65.0
END DESCRIPTION:
XS GIS Cut Line= 4
      2933168.03     10053204.93      2934348.58     10053316.04
      2934987.47     10052927.16      2935862.51      10052670.2
#Sta/Elev= 30
  3610.5 1146.33  3773.1 1143.02  3970.5 1137.52  4071.3  1133.7  4123.2 1131.43
  4201.3 1117.47  4340.2 1105.96  4414.5 1102.85  4476.7 1090.89  4591.8 1076.34
  4719.5  1071.3  4776.1 1059.03  4788.5  1057.7  4808.7 1055.15  4925.3 1048.31
  5014.3 1040.47  5017.1 1039.97  5020.3 1040.47  5088.8 1059.73  5118.1 1068.14
  5189.6 1067.98  5215.7 1066.15  5340.8 1070.87  5663.7 1092.85  5786.4 1099.88
  5965.9 1106.98  6048.3 1121.19  6233.1 1133.87    6354 1157.65  6456.2  1165.8
#Mann= 19 ,-1 , 0
  3610.5      .1       0  3773.1     .16       0  3970.5      .1       0
  4071.3     .05       0  4201.3      .1       0  4340.2     .05       0
  4476.7      .1       0  4591.8     .05       0  4788.5      .1       0
  4808.7     .05       0  4925.3      .1       0  5014.3     .07       0
  5020.3      .1       0  5189.6     .05       0  5215.7      .1       0
  5340.8     .05       0  5663.7      .1       0  5786.4     .05       0
  6048.3      .1       0
Bank Sta=4776.1,5088.8
XS Rating Curve= 0 ,0
Exp/Cntr=0.3,0.1

Type RM Length L Ch R = 1 ,44099   ,855,855,855
BEGIN DESCRIPTION:
MILLER CREEK 64.0
END DESCRIPTION:
XS GIS Cut Line= 3
      2933751.38      10054468.8      2935265.25     10053267.43
      2935931.56     10052788.52
#Sta/Elev= 30
  3646.7 1147.84    3741 1135.47  4003.8 1126.48    4091 1111.98  4146.4 1110.06
  4268.2 1091.26  4391.3 1083.66  4453.5 1079.48  4691.7 1069.46  4714.2 1064.05
    4752 1058.02  4841.9 1052.82  4845.9 1052.64  4929.9 1047.17  4941.3 1043.36
    4991 1040.52  4993.7 1040.02    4997 1040.52  5122.1 1058.57  5144.2 1060.63
  5292.5 1076.58  5442.7 1080.81  5593.7 1086.39  5885.3 1110.88  5950.3  1121.7
  5999.5  1124.6  6087.5 1128.26  6172.5 1131.69  6264.6 1147.41  6399.9 1159.29
#Mann= 17 ,-1 , 0
  3646.7     .05       0    4091     .16       0  4391.3     .05       0
  4453.5     .16       0  4691.7      .1       0  4714.2     .05       0
  4841.9      .1       0  4845.9     .05       0  4941.3      .1       0
    4991     .07       0    4997      .1       0  5144.2     .05       0
  5292.5      .1       0  5442.7     .05       0  5593.7      .1       0
  5999.5     .05       0  6087.5      .1       0
Bank Sta=4752,5122.1
XS Rating Curve= 0 ,0
Exp/Cntr=0.3,0.1

Type RM Length L Ch R = 1 ,43244   ,795,795,795
BEGIN DESCRIPTION:
MILLER CREEK 63.0
END DESCRIPTION:
XS GIS Cut Line= 4
      2934640.22     10054975.79      2935223.58      10054559.1
      2935598.58     10053857.71      2936015.25     10052934.09
#Sta/Elev= 30
  3884.4 1123.45  3978.5 1119.91  4129.6 1101.26  4160.5 1099.16  4278.3 1091.96
  4379.7 1080.73  4623.3  1065.4  4687.8 1066.22  4743.5 1066.41 4795.45 1055.22
  4822.8    1047  4875.3 1048.19  4913.5 1045.31  4924.9 1038.37  4963.2 1038.57
  4998.3 1036.34  5001.1 1035.84  5004.3 1036.34  5029.7 1043.93    5133 1055.56
  5141.5  1056.1    5259 1062.43    5363 1076.47  5719.1 1095.02  5869.9 1109.57
  5915.2 1115.42  6043.7 1119.67  6260.9 1132.52  6388.9  1146.5  6409.9 1148.23
#Mann= 13 ,-1 , 0
  3884.4     .16       0  4129.6      .1       0  4160.5     .16       0
  4379.7      .1       0  4687.8     .16       0  4963.2      .1       0
  4998.3     .07       0  5004.3      .1       0  5029.7     .16       0
  5141.5      .1       0  5869.9     .05       0  6043.7      .1       0
  6388.9     .16       0
#XS Ineff= 2 , 0
         4727.27 1068.01
Permanent Ineff=
       T       T
Bank Sta=4795.45,5133
XS Rating Curve= 0 ,0
Exp/Cntr=0.3,0.1

Type RM Length L Ch R = 1 ,42449   ,632,632,632
BEGIN DESCRIPTION:
MILLER CREEK 62.0
END DESCRIPTION:
XS GIS Cut Line= 3
      2934668.06     10055052.15      2935869.41     10054899.38
      2936966.62     10053441.07
#Sta/Elev= 30
  3462.8 1122.89  3513.6 1121.64    3751 1098.34  3927.4 1085.74  4603.5 1062.48
  4705.9 1053.92    4767  1048.6  4819.2 1039.99  4843.4 1044.79  4933.7 1043.29
  4962.6 1037.13  5003.3 1034.44    5006 1033.94  5009.3 1034.44  5056.3 1046.68
  5119.1 1054.06  5201.2  1058.5  5248.2 1061.03  5288.9 1069.04  5383.5 1097.04
  5439.8 1103.58  5462.7 1109.19  5569.4 1117.42  5706.3 1122.65  5792.8 1125.69
  5816.2 1127.24  6038.9 1138.31  6297.7 1157.62  6383.1    1172  6498.8  1177.6
#Mann= 15 ,-1 , 0
  3462.8     .16       0    3751      .1       0  3927.4     .05       0
    4767      .1       0  4843.4     .05       0  4962.6     .16       0
  5003.3     .07       0  5009.3     .16       0  5201.2      .1       0
  5288.9     .16       0  5439.8      .1       0  5706.3     .16       0
  5792.8      .1       0  5816.2     .05       0  6038.9      .1       0
Bank Sta=4705.9,5119.1
XS Rating Curve= 0 ,0
Exp/Cntr=0.3,0.1

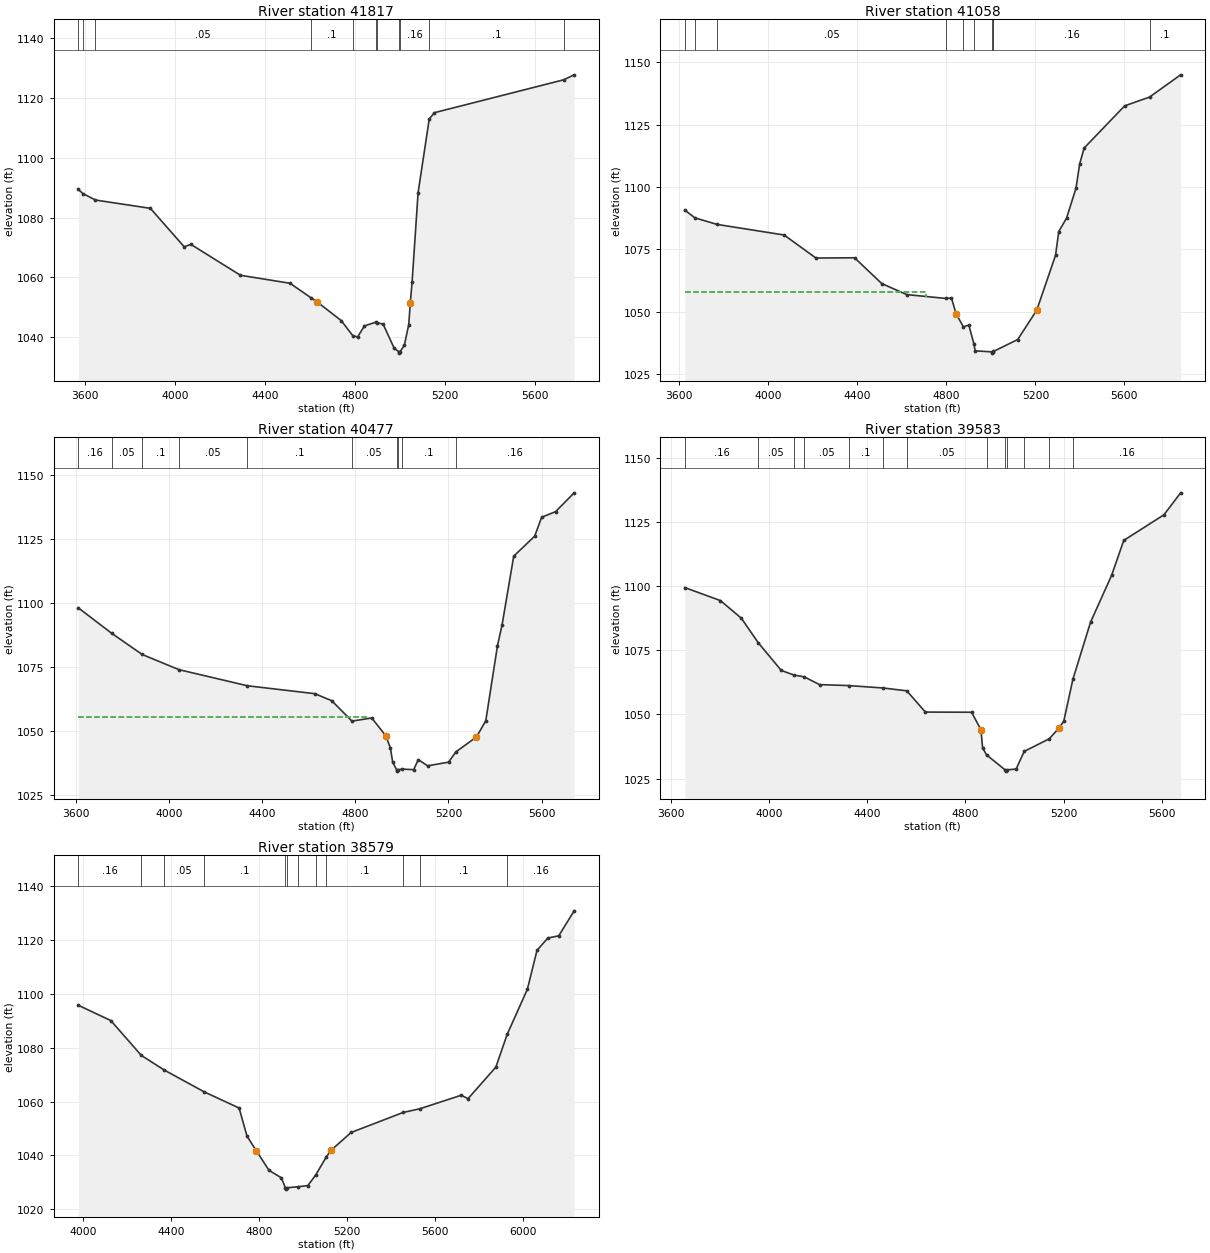
Type RM Length L Ch R = 1 ,41817   ,759,759,759
BEGIN DESCRIPTION:
MILLER CREEK 61.0
END DESCRIPTION:
XS GIS Cut Line= 3
      2935098.63     10055225.76      2936049.97     10055177.16
      2937258.28     10054850.77
#Sta/Elev= 30
  3571.1 1089.43  3591.6 1088.06  3647.3  1085.9  3891.4 1083.13  4041.6 1070.27
  4071.6 1071.07  4291.8 1060.74  4512.2 1058.07  4603.5 1053.31  4631.8 1051.89
  4739.7  1045.6    4791 1040.56  4812.2 1040.09  4843.2 1043.81  4894.4 1045.08
  4898.2 1044.91  4926.1 1044.39  4975.3 1036.33  4995.6 1035.21  4998.4 1034.71
  5001.6 1035.21  5020.3 1037.33    5040 1044.25 5046.88 1051.54    5055 1058.64
  5081.5 1088.35  5131.1    1113    5154 1115.11  5728.4  1126.1  5775.3 1127.77
#Mann= 11 ,-1 , 0
  3571.1     .16       0  3591.6      .1       0  3647.3     .05       0
  4603.5      .1       0    4791     .05       0  4894.4      .1       0
  4898.2     .16       0  4995.6     .07       0  5001.6     .16       0
  5131.1      .1       0  5728.4     .05       0
Bank Sta=4631.8,5046.88
XS Rating Curve= 0 ,0
Exp/Cntr=0.3,0.1

Type RM Length L Ch R = 1 ,41058   ,581,581,581
BEGIN DESCRIPTION:
MILLER CREEK 60.0
END DESCRIPTION:
XS GIS Cut Line= 4
      2935070.84     10055309.11       2936070.8     10055510.49
       2936633.3     10055989.66       2937097.3     10056058.91
#Sta/Elev= 30
  3624.4 1090.79  3669.6 1087.68  3769.3 1085.05  4070.8  1080.8  4213.6 1071.59
  4387.2 1071.68  4509.4 1061.36  4621.7 1056.93  4798.4 1055.39  4822.7 1055.56
  4843.6 1049.26  4876.3 1044.01  4900.7 1044.72  4923.4 1037.25  4929.3 1034.41
  5004.2 1033.99    5007 1033.49  5010.2 1033.99  5011.5 1034.17  5120.3 1038.93
    5206 1050.71  5290.5 1072.68  5304.8  1082.2  5339.9 1087.55  5382.6 1099.62
  5398.7 1109.23  5418.9 1115.64  5600.9 1132.53  5712.7 1136.04  5852.5 1144.96
#Mann= 10 ,-1 , 0
  3624.4     .16       0  3669.6      .1       0  3769.3     .05       0
  4798.4      .1       0  4876.3     .16       0  4923.4      .1       0
  5004.2     .07       0  5010.2      .1       0  5011.5     .16       0
  5712.7      .1       0
#XS Ineff= 2 , 0
         4708.81 1057.85
Permanent Ineff=
       T       T
Bank Sta=4843.6,5206
XS Rating Curve= 0 ,0
Exp/Cntr=0.3,0.1

Type RM Length L Ch R = 1 ,40477   ,894,894,894
BEGIN DESCRIPTION:
MILLER CREEK 59.0
END DESCRIPTION:
XS GIS Cut Line= 3
       2934980.5      10055593.8      2935966.64     10056239.66
      2936918.02     10056239.66
#Sta/Elev= 30
  3609.9    1098  3752.8 1088.08  3884.1 1079.78  4041.5 1073.86  4336.6 1067.54
  4626.1 1064.45  4698.5  1061.7  4785.5 1053.73  4870.5 1054.96  4930.5 1048.03
  4950.5 1043.27  4960.5 1037.67  4977.5 1034.68  4980.3 1034.18  4983.5 1034.68
  4999.8 1034.98  5050.5 1034.75  5070.5 1038.66  5110.5 1036.26  5200.5 1037.68
  5232.1 1041.72  5320.5 1047.53  5360.5 1053.89  5410.5 1083.13  5430.5 1091.37
  5480.5 1118.21  5570.5 1126.02  5600.5 1133.42  5660.5 1135.62  5740.1 1142.96
#Mann= 10 ,-1 , 0
  3609.9     .16       0  3752.8     .05       0  3884.1      .1       0
  4041.5     .05       0  4336.6      .1       0  4785.5     .05       0
  4977.5     .07       0  4983.5     .05       0  4999.8      .1       0
  5232.1     .16       0
#XS Ineff= 2 , 0
         4859.38 1055.22
Permanent Ineff=
       T       T
Bank Sta=4930.5,5320.5
XS Rating Curve= 0 ,0
Exp/Cntr=0.3,0.1

Type RM Length L Ch R = 1 ,39583   ,1004,1004,1004
BEGIN DESCRIPTION:
MILLER CREEK 58.0
END DESCRIPTION:
XS GIS Cut Line= 4
      2935327.76     10057878.54      2936091.64     10057163.27
      2936654.14     10057045.21      2936959.41      10056788.5
#Sta/Elev= 30
  3656.7 1099.39  3802.1 1094.31  3887.1 1087.45  3956.2 1077.87  4049.8  1067.1
  4102.2 1065.29    4143 1064.62  4205.6 1061.59  4323.9 1061.21  4464.7 1060.27
    4561 1059.17  4636.9 1050.89  4825.1 1050.82  4863.4 1043.99  4869.9 1037.03
  4885.9 1034.22  4961.6 1028.38  4964.3 1027.88  4967.6 1028.38  5006.5 1028.68
  5039.5 1035.57  5141.2 1040.45  5180.2 1044.54  5200.6  1047.3  5237.9 1063.66
  5309.9 1085.94  5395.7 1104.17  5445.1 1117.76    5609 1127.75  5676.8  1136.3
#Mann= 13 ,-1 , 0
  3656.7     .16       0  3956.2     .05       0  4102.2      .1       0
    4143     .05       0  4323.9      .1       0  4464.7     .16       0
    4561     .05       0  4885.9      .1       0  4961.6     .07       0
  4967.6      .1       0  5039.5     .16       0  5141.2     .05       0
  5237.9     .16       0
Bank Sta=4863.4,5180.2
XS Rating Curve= 0 ,0
Exp/Cntr=0.3,0.1

Type RM Length L Ch R = 1 ,38579   ,504,504,504
BEGIN DESCRIPTION:
MILLER CREEK 57.0
END DESCRIPTION:
XS GIS Cut Line= 4
      2936140.26     10058850.75      2936612.47     10058156.32
       2936883.3      10057871.6      2937098.57     10056871.63
#Sta/Elev= 30
  3979.2 1095.76    4127 1090.09  4265.7 1077.15  4369.4 1071.74  4552.6 1063.58
  4710.6 1057.61  4746.5 1047.17  4788.5 1041.78  4846.3 1034.49    4903 1031.69
    4921 1027.99  4923.8 1027.49    4927 1027.99  4977.4 1028.36  5023.1  1028.8
  5058.5 1032.67  5107.9 1039.52  5129.1 1041.93    5220 1048.52    5457 1055.97
  5532.6 1057.33  5721.2 1062.36  5751.9 1061.07  5878.8 1072.82    5930 1084.96
  6021.7 1101.66  6065.9 1116.18  6115.3 1120.75  6164.6 1121.56  6234.8 1130.84
#Mann= 12 ,-1 , 0
  3979.2     .16       0  4265.7      .1       0  4369.4     .05       0
  4552.6      .1       0    4921    .033       0    4927      .1       0
  4977.4     .05       0  5058.5     .16       0  5107.9      .1       0
    5457     .05       0  5532.6      .1       0    5930     .16       0
Bank Sta=4788.5,5129.1
XS Rating Curve= 0 ,0
Exp/Cntr=0.3,0.1