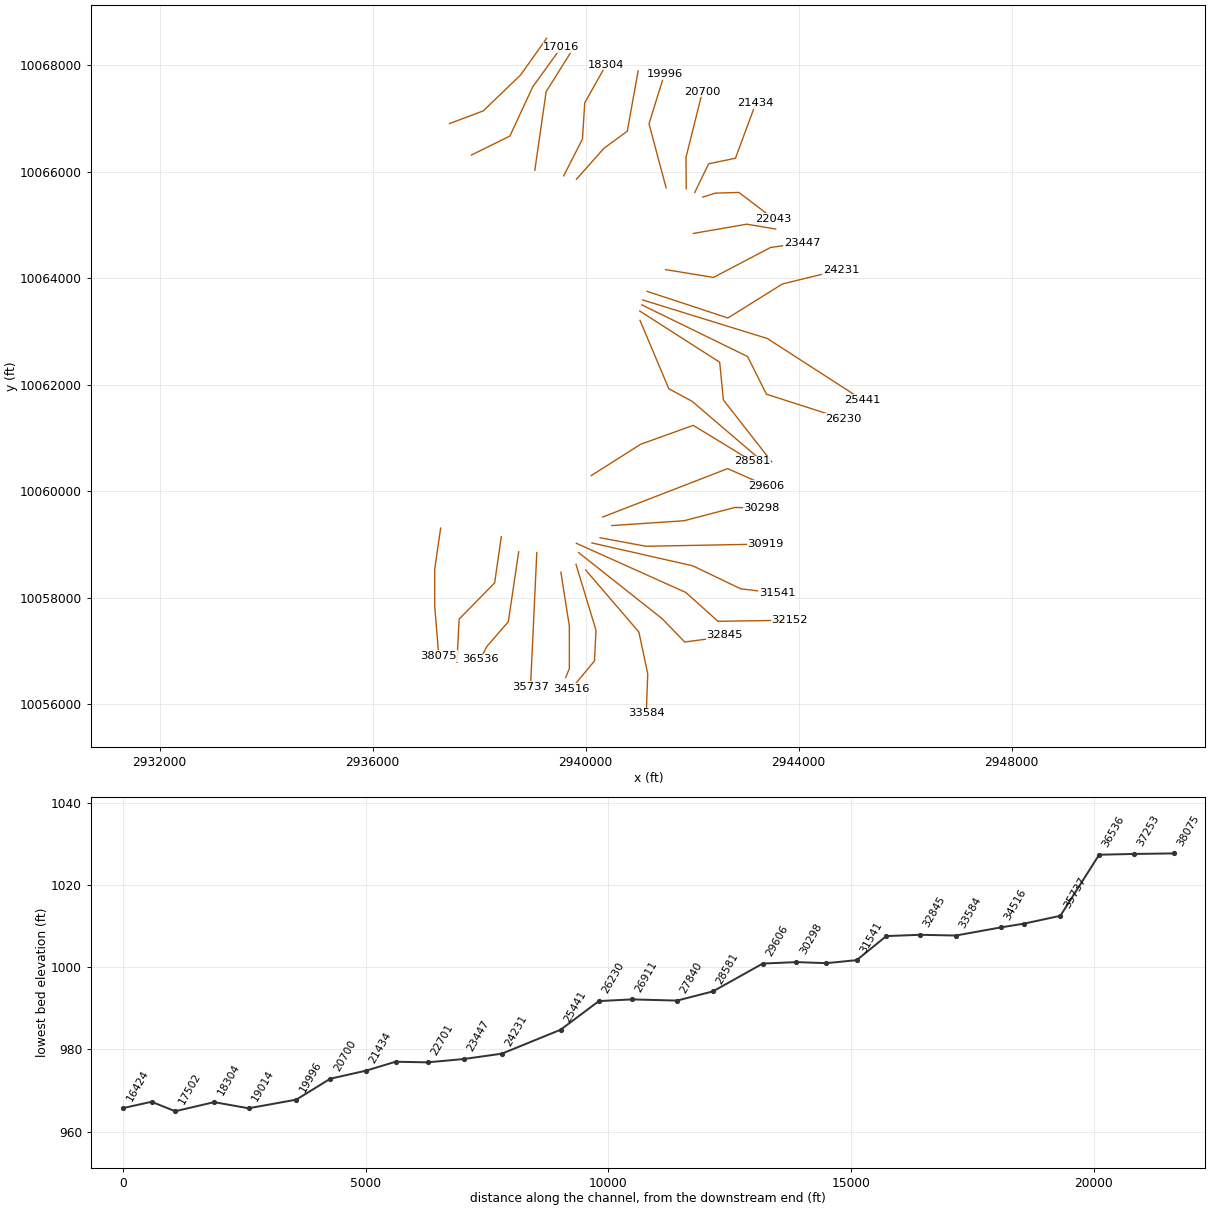
HEC-RAS study MILLER CREEK.prj: MILLER CREEK Base Level Engineering

--- MILLER CREEK.g01 (geometry) --- (continued)

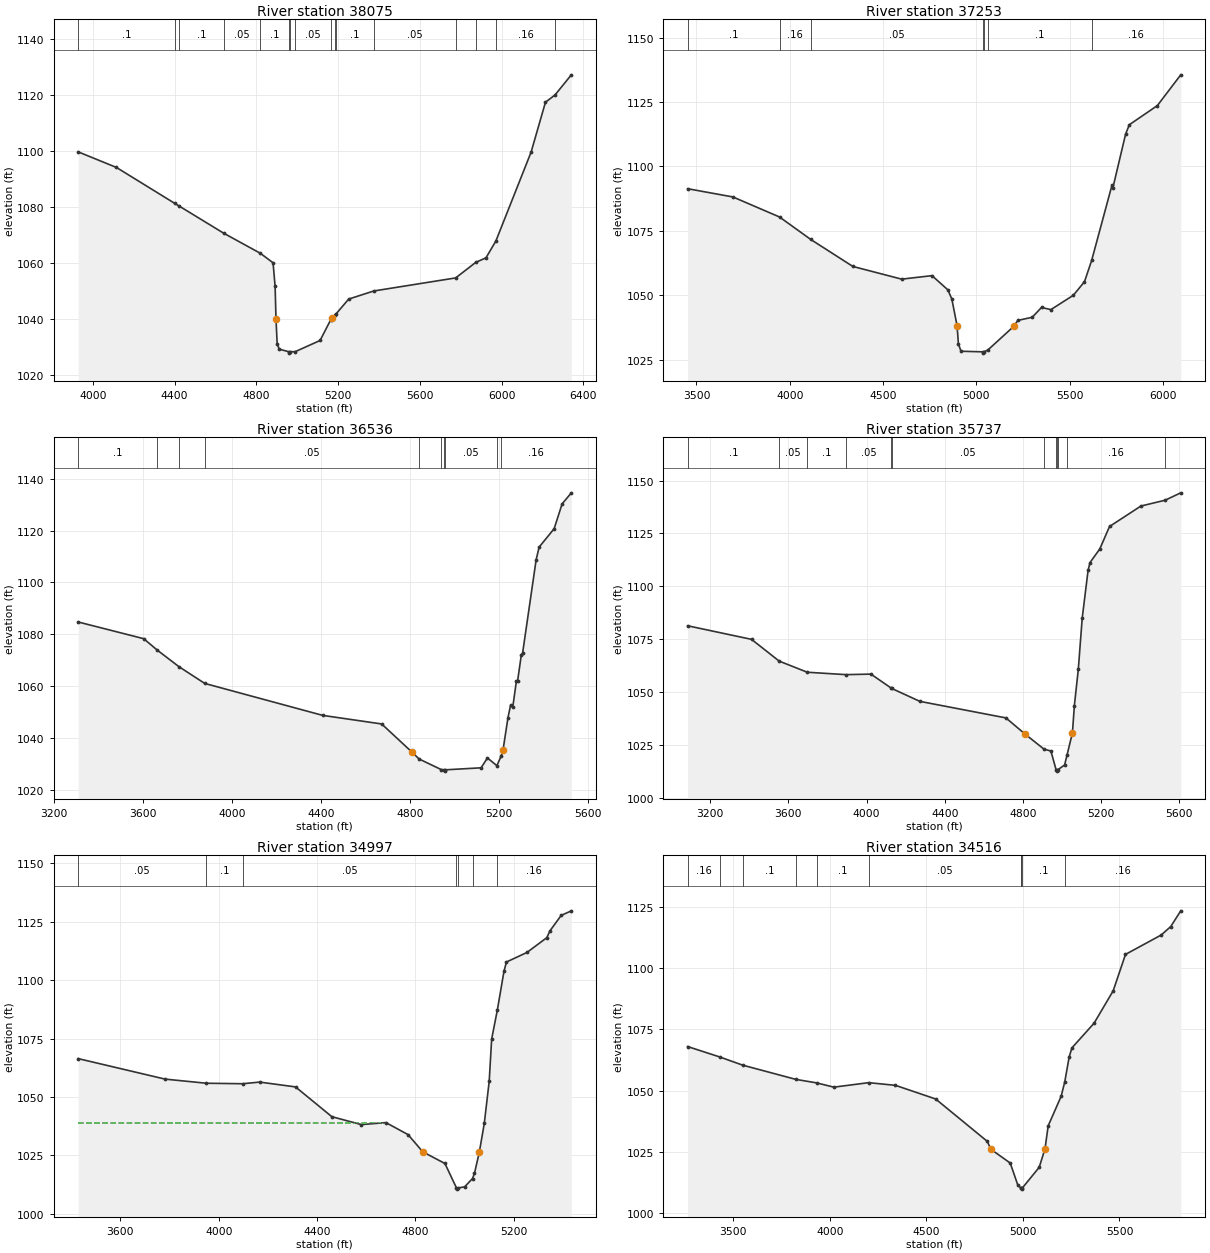
Type RM Length L Ch R = 1 ,38075   ,822,822,822
BEGIN DESCRIPTION:
MILLER CREEK 56.0
END DESCRIPTION:
XS GIS Cut Line= 4
      2937279.14     10059309.12      2937168.03     10058545.21
      2937168.03     10057836.88      2937244.32     10056907.48
#Sta/Elev= 30
  3928.3 1099.66  4115.6 1094.08  4400.1 1081.26  4421.1 1080.33  4640.2 1070.56
  4819.3 1063.38  4881.7 1059.97  4891.7 1051.51 4896.02 1039.97  4901.7 1031.08
  4911.7 1029.07  4958.7 1028.15  4961.5 1027.65  4964.7 1028.15  4990.3 1028.18
  5111.7 1032.18  5163.5 1039.54  5171.7 1040.07    5185 1041.24  5187.4 1041.48
  5251.7 1046.99  5374.5 1049.89  5775.1 1054.56  5873.4 1060.12  5923.4 1061.75
  5971.8 1067.76  6144.2 1099.58  6214.4 1117.43  6260.9    1120  6341.1 1127.23
#Mann= 16 ,-1 , 0
  3928.3      .1       0  4400.1     .05       0  4421.1      .1       0
  4640.2     .05       0  4819.3      .1       0  4958.7    .033       0
  4964.7      .1       0  4990.3     .05       0  5163.5      .1       0
    5185     .05       0  5187.4      .1       0  5374.5     .05       0
  5775.1      .1       0  5873.4     .05       0  5971.8     .16       0
  6260.9      .1       0
Bank Sta=4896.02,5171.7
XS Rating Curve= 0 ,0
Exp/Cntr=0.3,0.1

Type RM Length L Ch R = 1 ,37253   ,717,717,717
BEGIN DESCRIPTION:
MILLER CREEK 55.0
END DESCRIPTION:
XS GIS Cut Line= 4
      2938418.03     10059149.39      2938293.03     10058281.32
      2937626.36     10057600.77      2937584.71     10056788.53
#Sta/Elev= 30
  3452.4 1091.35  3695.2 1088.15  3945.1 1080.37  4111.7 1071.68  4338.1 1061.17
  4599.7 1056.24  4762.2  1057.6  4847.1  1052.1  4868.4 1048.56  4896.7 1038.12
  4903.7 1031.11  4917.8 1028.25  5035.1 1028.02  5037.9 1027.52  5041.1 1028.02
  5061.6 1028.73  5200.7 1037.93    5222 1040.21  5299.2 1041.44  5349.2 1045.25
  5399.3 1044.41  5519.4 1049.96  5579.5 1055.25  5617.9 1063.51  5726.9 1092.74
  5731.9 1091.78  5799.8 1112.54  5819.8 1116.19    5970 1123.62  6095.4 1135.56
#Mann= 7 ,-1 , 0
  3452.4      .1       0  3945.1     .16       0  4111.7     .05       0
  5035.1    .033       0  5041.1     .05       0  5061.6      .1       0
  5617.9     .16       0
Bank Sta=4896.7,5200.7
XS Rating Curve= 0 ,0
Exp/Cntr=0.3,0.1

Type RM Length L Ch R = 1 ,36536   ,799,799,799
BEGIN DESCRIPTION:
MILLER CREEK 53.0
END DESCRIPTION:
XS GIS Cut Line= 4
      2938744.41     10058864.64      2938549.97     10057552.16
      2938147.19     10057086.88      2938022.84     10056845.08
#Sta/Elev= 30
  3310.6 1084.78  3604.7 1078.35  3666.1 1073.91  3762.6 1067.59  3878.8 1061.11
  4408.6  1048.8  4673.1  1045.5  4807.3  1034.8  4841.3    1032  4940.1 1027.94
  4953.1 1027.83  4955.9 1027.33  4959.1 1027.83  5119.5 1028.61    5148 1032.41
  5190.3 1029.42  5209.5 1033.13  5218.3 1035.65  5240.2 1047.96  5251.6 1052.66
  5261.5 1051.88    5278 1062.01  5283.6 1062.22  5300.2 1072.16  5305.8 1072.78
  5366.7 1108.79    5380 1113.63  5447.5 1120.73  5483.2 1130.28  5524.7 1134.54
#Mann= 10 ,-1 , 0
  3310.6      .1       0  3666.1     .05       0  3762.6      .1       0
  3878.8     .05       0  4841.3      .1       0  4940.1     .05       0
  4953.1    .033       0  4959.1     .05       0  5190.3      .1       0
  5209.5     .16       0
Bank Sta=4807.3,5218.3
XS Rating Curve= 0 ,0
Exp/Cntr=0.3,0.1

Type RM Length L Ch R = 1 ,35737   ,740,740,740
BEGIN DESCRIPTION:
MILLER CREEK 52.0
END DESCRIPTION:
XS GIS Cut Line= 2
      2939084.69      10058850.8      2938966.64     10056329.96
#Sta/Elev= 30
  3084.4 1081.31  3411.8 1074.87    3553 1064.57  3696.9 1059.31  3894.3 1058.17
  4022.5 1058.42  4124.4 1051.92  4128.5 1051.65  4272.8 1045.52  4713.2 1037.69
  4813.4 1029.87  4908.1  1022.9  4943.5 1022.01  4970.5 1012.99  4973.3 1012.49
  4976.5 1012.99  4977.4 1013.04  5013.6 1015.39    5026 1020.09  5053.6 1030.58
  5063.6 1043.56  5083.7 1060.62  5103.7 1084.91  5133.7 1107.51  5143.7 1111.25
  5193.8 1117.69  5243.5 1128.31    5404 1137.99  5528.2 1140.76    5608 1144.25
#Mann= 12 ,-1 , 0
  3084.4      .1       0    3553     .05       0  3696.9      .1       0
  3894.3     .05       0  4124.4      .1       0  4128.5     .05       0
  4908.1      .1       0  4970.5    .035       0  4976.5      .1       0
  4977.4     .05       0    5026     .16       0  5528.2      .1       0
Bank Sta=4813.4,5053.6
XS Rating Curve= 0 ,0
Exp/Cntr=0.3,0.1

Type RM Length L Ch R = 1 ,34997   ,481,481,481
BEGIN DESCRIPTION:
MILLER CREEK 51.0
END DESCRIPTION:
XS GIS Cut Line= 4
      2939536.07     10058482.76       2939695.8     10057468.82
       2939695.8     10056670.21      2939626.36     10056503.55
#Sta/Elev= 30
  3428.5 1066.46  3781.8 1057.69  3949.9 1055.92  4097.8 1055.71  4166.5 1056.42
  4312.4 1054.35    4460 1041.61    4580 1038.22    4680 1039.07    4770 1033.93
    4830 1026.55    4920 1021.57    4967  1011.1  4969.8  1010.6    4973  1011.1
    5000 1011.57  5032.1 1015.14    5040  1017.3    5060 1026.52    5080 1038.71
    5100 1056.74    5110 1074.84    5133 1087.19    5160 1103.76    5170  1107.8
  5253.5  1111.9  5334.3 1118.23  5347.2 1121.18  5392.8 1127.76  5434.1 1129.72
#Mann= 7 ,-1 , 0
  3428.5     .05       0  3949.9      .1       0  4097.8     .05       0
    4967    .035       0    4973     .05       0  5032.1      .1       0
    5133     .16       0
#XS Ineff= 2 , 0
         4681.82 1039.07
Permanent Ineff=
       T       T
Bank Sta=4830,5060
XS Rating Curve= 0 ,0
Exp/Cntr=0.3,0.1

Type RM Length L Ch R = 1 ,34516   ,932,932,932
BEGIN DESCRIPTION:
MILLER CREEK 50.0
END DESCRIPTION:
XS GIS Cut Line= 4
      2939820.79     10058628.58       2940195.8     10057392.43
      2940168.03     10056816.04       2939730.7     10056288.48
#Sta/Elev= 30
  3263.4 1067.99    3429 1063.75    3549 1060.37  3824.5 1054.55    3931 1053.14
  4020.9 1051.38  4201.5 1053.22    4340 1052.12  4547.9 1046.55  4815.3 1029.23
  4834.2 1025.97  4934.3 1020.35  4974.4 1011.17  4989.7 1010.21  4991.4 1010.18
  4994.1 1009.68  4997.4 1010.18  5084.5 1018.61  5114.5 1026.22  5130.9 1035.56
  5197.9 1047.62  5216.8 1053.55  5239.5 1063.69  5253.9 1067.45  5368.5 1077.53
  5467.5 1090.78  5531.3 1105.67  5716.2  1113.6  5765.7 1117.06  5817.5 1123.49
#Mann= 10 ,-1 , 0
  3263.4     .16       0    3429     .05       0    3549      .1       0
  3824.5     .05       0    3931      .1       0  4201.5     .05       0
  4989.7      .1       0  4991.4     .07       0  4997.4      .1       0
  5216.8     .16       0
Bank Sta=4834.2,5114.5
XS Rating Curve= 0 ,0
Exp/Cntr=0.3,0.1

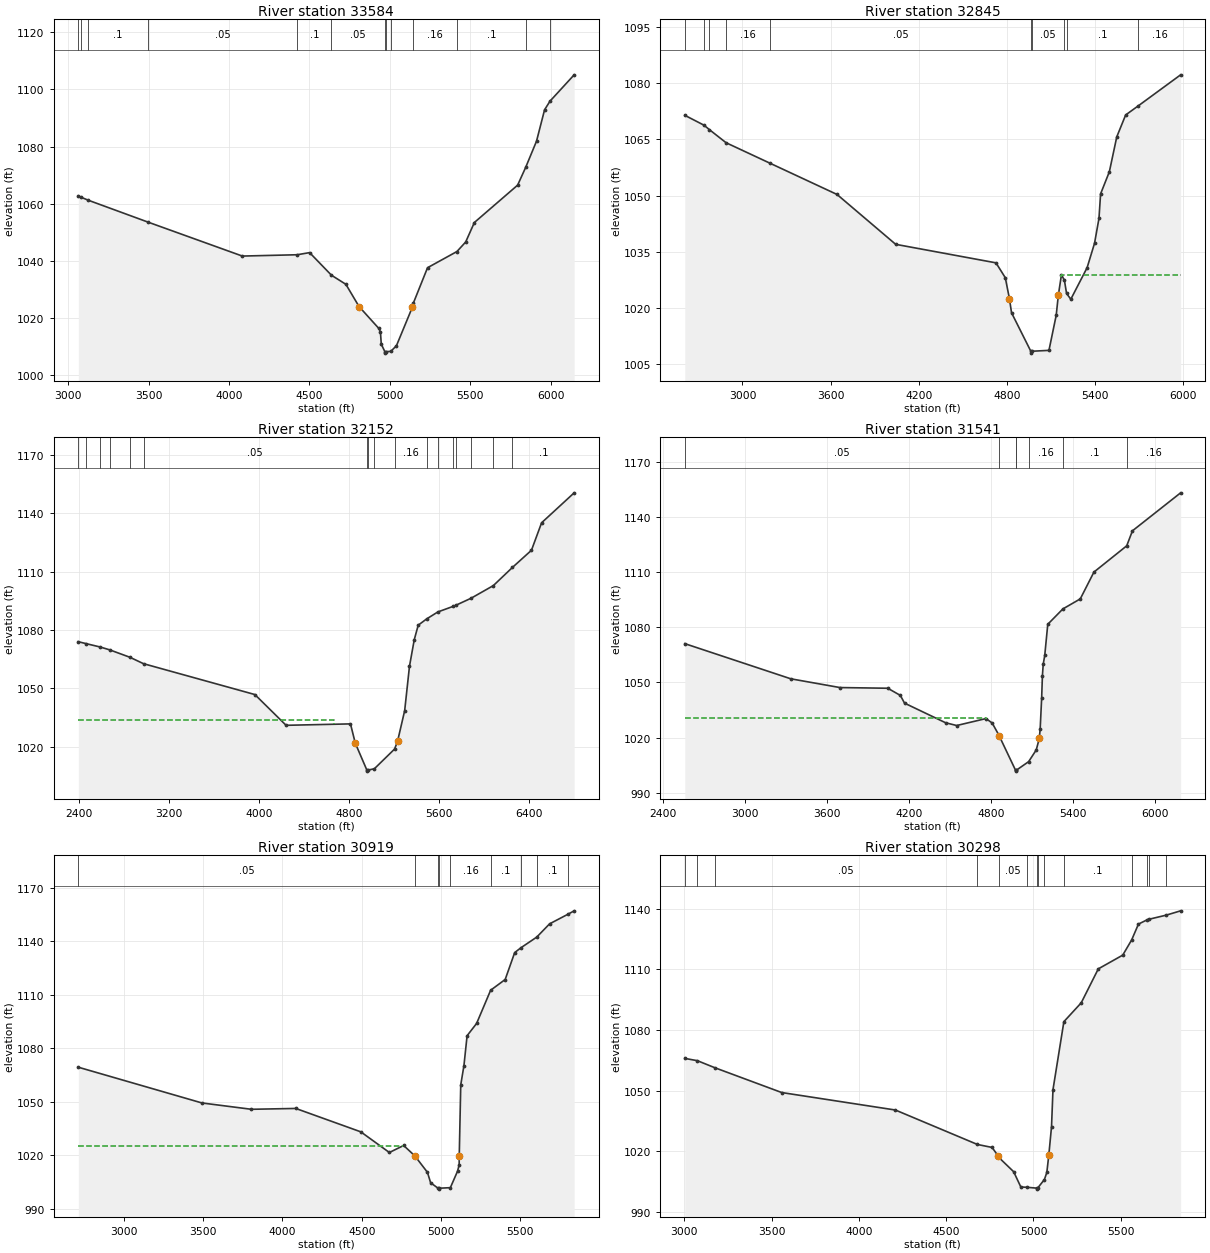
Type RM Length L Ch R = 1 ,33584   ,739,739,739
BEGIN DESCRIPTION:
MILLER CREEK 49.0
END DESCRIPTION:
XS GIS Cut Line= 4
      2940001.35     10058524.39      2941001.36     10057357.71
      2941168.03     10056572.99      2941140.25     10055829.94
#Sta/Elev= 30
  3063.7 1062.76  3078.5 1062.32  3125.5 1061.22  3495.3 1053.59  4083.2 1041.67
  4424.3 1042.13  4501.4 1042.88  4637.4 1034.96    4727 1031.78  4808.8    1024
  4931.5 1016.35  4941.7 1015.16  4947.1 1010.81  4969.4 1008.19  4972.2 1007.69
  4975.4 1008.19  5006.3 1008.31  5041.3 1010.28  5140.5  1023.8    5146 1025.14
  5234.6 1037.59  5417.4 1043.26  5471.8  1046.6  5525.7 1053.42  5794.7  1066.5
  5844.7 1072.72  5912.1 1081.89  5962.2 1092.88    5996 1095.91  6146.1 1105.12
#Mann= 13 ,-1 , 0
  3063.7      .1       0  3078.5     .05       0  3125.5      .1       0
  3495.3     .05       0  4424.3      .1       0  4637.4     .05       0
  4969.4    .035       0  4975.4     .05       0  5006.3      .1       0
    5146     .16       0  5417.4      .1       0  5844.7     .16       0
    5996      .1       0
Bank Sta=4808.8,5140.5
XS Rating Curve= 0 ,0
Exp/Cntr=0.3,0.1

Type RM Length L Ch R = 1 ,32845   ,693,693,693
BEGIN DESCRIPTION:
MILLER CREEK 48.0
END DESCRIPTION:
XS GIS Cut Line= 5
      2939869.42     10058850.76      2941438.86     10057607.71
      2941862.47     10057170.21      2942536.08     10057260.49
      2942612.48     10057295.22
#Sta/Elev= 30
  2607.4 1071.46  2738.2 1068.81  2775.3 1067.61  2888.5 1064.12  3189.3 1058.61
  3643.7 1050.29  4042.7 1036.96  4725.3 1032.01  4788.8 1028.03  4817.1 1022.37
  4831.2 1018.66  4962.5 1008.37  4965.3 1007.87  4968.5 1008.37  5085.9 1008.61
  5135.3    1018  5149.5 1023.29  5170.8 1028.81  5190.9 1027.38  5205.8 1023.82
  5234.6 1022.28  5345.6 1030.72    5396 1037.23  5426.3  1043.9  5437.3 1050.45
  5496.9 1056.36  5547.4 1065.69  5607.9 1071.55    5695 1074.02    5982 1082.28
#Mann= 10 ,-1 , 0
  2607.4      .1       0  2738.2     .16       0  2775.3      .1       0
  2888.5     .16       0  3189.3     .05       0  4962.5    .035       0
  4968.5     .05       0  5190.9     .16       0  5205.8      .1       0
    5695     .16       0
#XS Ineff= 2 , 0
                         5168.75         1028.84
Permanent Ineff=
       T       T
Bank Sta=4817.1,5149.5
XS Rating Curve= 0 ,0
Exp/Cntr=0.3,0.1

Type RM Length L Ch R = 1 ,32152   ,611,611,611
BEGIN DESCRIPTION:
MILLER CREEK 47.0
END DESCRIPTION:
XS GIS Cut Line= 4
      2939827.75     10059024.37       2941883.3     10058100.77
      2942487.47      10057559.1      2943827.76     10057579.93
#Sta/Elev= 30
  2395.1 1073.99  2465.3 1072.99  2590.4 1071.26  2673.9 1069.81  2853.6    1066
  2974.3 1062.71  3963.6 1046.87    4241 1031.08  4813.2 1031.81  4855.8 1021.92
    4959 1008.06  4961.7 1007.56    4965 1008.06    5025 1008.76  5204.9 1018.89
  5231.1  1022.8  5294.7 1038.64  5337.3 1061.37  5379.9 1075.06    5415 1082.48
  5490.8 1085.73  5589.4 1089.27  5725.9 1092.15  5746.8 1092.63  5885.3 1096.33
  6082.5  1102.8  6252.1 1112.12  6421.2 1120.94  6511.2 1135.04  6800.5 1150.42
#Mann= 17 ,-1 , 0
  2395.1     .16       0  2465.3     .05       0  2590.4      .1       0
  2673.9     .05       0  2853.6     .16       0  2974.3     .05       0
    4959    .035       0    4965     .05       0    5025      .1       0
  5204.9     .16       0  5490.8      .1       0  5589.4     .05       0
  5725.9      .1       0  5746.8     .05       0  5885.3      .1       0
  6082.5     .16       0  6252.1      .1       0
#XS Ineff= 2 , 0
         4670.45 1033.64
Permanent Ineff=
       T       T
Bank Sta=4855.8,5231.1
XS Rating Curve= 0 ,0
Exp/Cntr=0.3,0.1

Type RM Length L Ch R = 1 ,31541   ,622,622,622
BEGIN DESCRIPTION:
MILLER CREEK 46.0
END DESCRIPTION:
XS GIS Cut Line= 4
       2940119.4     10059031.33      2942015.25     10058600.77
      2942911.08     10058170.21       2943598.6     10058086.88
#Sta/Elev= 30
  2559.6 1071.17  3335.9 1052.01    3696 1047.24  4045.6 1046.87  4137.9 1042.97
  4168.6 1038.75  4469.4 1028.06  4550.4 1026.56  4765.2 1030.35  4810.5 1027.91
  4859.8 1021.28  4862.3 1020.84  4981.4 1002.21  4984.1 1001.71  4987.4 1002.21
  5077.2 1006.87  5132.9 1013.23  5155.6 1019.56  5161.9 1024.89  5172.7 1041.67
  5178.2 1053.75  5184.1 1059.94  5195.2 1064.72  5217.4 1081.71  5328.1 1090.09
  5455.4 1095.55  5555.5 1110.17  5795.5 1124.47  5837.4 1132.64  6190.2 1153.34
#Mann= 7 ,-1 , 0
  2559.6     .05       0  4859.8      .1       0  4981.4     .07       0
  4987.4      .1       0  5077.2     .16       0  5328.1      .1       0
  5795.5     .16       0
#XS Ineff= 2 , 0
         4765.91 1030.84
Permanent Ineff=
       T       T
Bank Sta=4862.3,5155.6
XS Rating Curve= 0 ,0
Exp/Cntr=0.3,0.1

Type RM Length L Ch R = 1 ,30919   ,621,621,621
BEGIN DESCRIPTION:
MILLER CREEK 45.0
END DESCRIPTION:
XS GIS Cut Line= 3
       2940272.2     10059128.54       2941133.3     10058968.82
      2943383.33     10059010.49
#Sta/Elev= 30
  2713.4 1069.34  3492.7  1049.3  3804.4 1045.75  4084.4 1046.22  4494.5  1033.1
  4674.5 1021.52  4764.6 1025.45  4834.6 1019.66  4836.6 1019.44  4914.6  1010.4
  4934.6 1004.57  4981.6 1001.48  4984.3 1000.98  4987.6 1001.48  5059.1  1001.8
  5104.6 1011.09  5114.6 1014.59 5115.06 1019.42  5124.6 1059.48  5144.6 1070.19
  5164.6 1087.01  5224.6  1093.9    5313 1112.51  5404.7 1118.53  5464.7 1133.63
  5504.9 1136.39  5603.6  1142.3  5684.7 1149.74  5800.8 1155.14  5839.6 1157.04
#Mann= 9 ,-1 , 0
  2713.4     .05       0  4836.6      .1       0  4981.6     .07       0
  4987.6      .1       0  5059.1     .16       0    5313      .1       0
  5504.9     .05       0  5603.6      .1       0  5800.8     .05       0
#XS Ineff= 2 , 0
         4763.07 1025.43
Permanent Ineff=
       T       T
Bank Sta=4834.6,5115.06
XS Rating Curve= 0 ,0
Exp/Cntr=0.3,0.1

Type RM Length L Ch R = 1 ,30298   ,692,692,692
BEGIN DESCRIPTION:
MILLER CREEK 44.0
END DESCRIPTION:
XS GIS Cut Line= 4
      2940494.45     10059357.71      2941848.58     10059447.99
      2942806.91     10059697.99      2943299.98      10059684.1
#Sta/Elev= 30
  3002.5 1065.97    3075 1064.82  3173.6 1061.38  3557.7 1049.06  4209.2  1040.4
  4678.9 1023.35  4763.2 1021.87  4798.5 1017.57  4801.3 1016.95  4886.6 1009.86
  4927.9 1002.27  4961.9 1002.15  5017.9 1001.73  5020.7 1001.23  5023.9 1001.73
  5062.8 1005.97  5076.7 1009.49 5088.07 1018.05  5103.6 1032.13    5112 1050.48
  5174.4 1084.15  5273.9  1093.5  5371.6  1110.3  5511.7 1117.11  5562.7 1124.62
  5601.7 1132.47  5652.6 1134.64  5661.5 1134.86  5760.3 1136.89  5843.3 1139.04
#Mann= 14 ,-1 , 0
  3002.5     .16       0    3075      .1       0  3173.6     .05       0
  4678.9      .1       0  4801.3     .05       0  4961.9      .1       0
  5017.9     .07       0  5023.9      .1       0  5062.8     .16       0
  5174.4      .1       0  5562.7     .05       0  5652.6      .1       0
  5661.5     .05       0  5760.3      .1       0
Bank Sta=4798.5,5088.07
XS Rating Curve= 0 ,0
Exp/Cntr=0.3,0.1

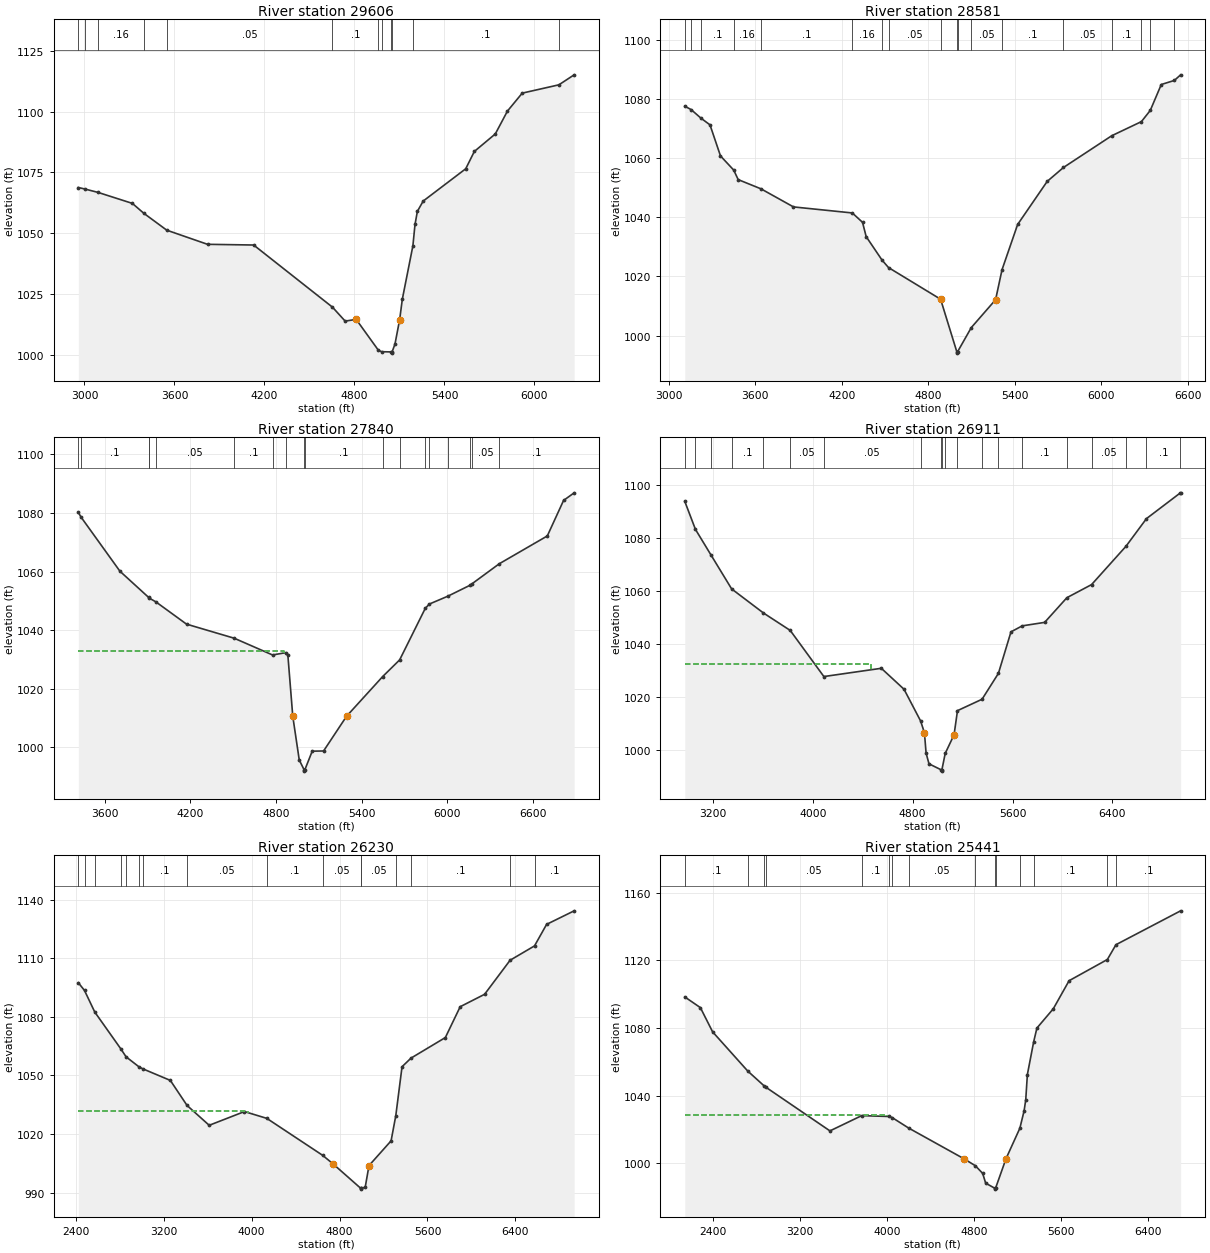
Type RM Length L Ch R = 1 ,29606   ,1025,1025,1025
BEGIN DESCRIPTION:
MILLER CREEK 43.0
END DESCRIPTION:
XS GIS Cut Line= 3
      2940320.77     10059517.42      2942668.03     10060427.16
      2943389.06     10060108.24
#Sta/Elev= 30
    2959 1068.82  3003.4 1068.19  3090.7 1066.81  3319.1 1062.31  3396.2 1058.22
  3548.5 1051.32  3820.2 1045.52  4127.9 1045.23  4653.5 1019.73  4737.9 1014.02
  4811.6 1014.71  4959.7 1002.04  4981.4 1001.46  5044.9 1001.38  5047.6 1000.88
  5050.9 1001.38  5070.2  1004.6  5101.5 1014.67  5119.3 1023.06  5189.6  1044.9
  5203.7 1053.66  5219.5 1059.04  5258.2 1063.26  5541.8 1076.51  5599.4 1083.62
  5739.1  1090.8  5819.9 1100.17  5918.6 1107.54    6163 1110.95  6264.8 1115.05
#Mann= 12 ,-1 , 0
    2959     .16       0  3003.4     .05       0  3090.7     .16       0
  3396.2      .1       0  3548.5     .05       0  4653.5      .1       0
  4959.7     .05       0  4981.4     .16       0  5044.9     .07       0
  5050.9     .16       0  5189.6      .1       0    6163     .05       0
Bank Sta=4811.6,5101.5
XS Rating Curve= 0 ,0
Exp/Cntr=0.3,0.1

Type RM Length L Ch R = 1 ,28581   ,741,741,741
BEGIN DESCRIPTION:
MILLER CREEK 42.0
END DESCRIPTION:
XS GIS Cut Line= 4
      2940105.55     10060295.23      2941036.08     10060885.49
      2942022.19     10061239.66      2943124.95     10060566.91
#Sta/Elev= 30
  3110.3 1077.51  3154.9 1076.33  3222.4 1073.46  3285.2 1071.19    3358 1060.71
  3449.7 1055.93  3480.9 1052.71  3639.3 1049.59  3864.7 1043.49  4272.9 1041.45
  4343.9 1038.29  4369.3 1033.45  4479.4 1025.53  4524.3 1023.01  4885.8 1012.32
  4998.1  994.62  5000.8  994.12  5004.1  994.62  5098.9 1002.75  5267.5 1012.16
  5312.2 1022.29  5420.5 1037.56  5625.6  1052.1  5738.5  1056.8  6073.6 1067.52
  6279.6 1072.29    6341 1076.06  6417.5 1084.82  6508.4  1086.2  6551.8 1088.09
#Mann= 18 ,-1 , 0
  3110.3      .1       0  3154.9     .16       0  3222.4      .1       0
  3449.7     .16       0  3639.3      .1       0  4272.9     .16       0
  4479.4      .1       0  4524.3     .05       0  4885.8      .1       0
  4998.1     .07       0  5004.1      .1       0  5098.9     .05       0
  5312.2      .1       0  5738.5     .05       0  6073.6      .1       0
  6279.6     .05       0    6341      .1       0  6508.4     .05       0
Bank Sta=4885.8,5267.5
XS Rating Curve= 0 ,0
Exp/Cntr=0.3,0.1

Type RM Length L Ch R = 1 ,27840   ,929,929,929
BEGIN DESCRIPTION:
MILLER CREEK 41.0
END DESCRIPTION:
XS GIS Cut Line= 4
       2941022.2     10063211.87      2941563.86     10061927.16
      2942001.36     10061691.04      2943202.74     10060663.28
#Sta/Elev= 30
  3415.4 1080.17  3435.6  1078.5  3706.8 1060.11  3907.2  1051.2  3910.2 1050.98
  3957.4 1049.69  4173.1 1042.05  4506.7 1037.25  4775.4 1031.53    4871 1032.33
    4883 1031.35  4917.2 1010.59  4962.6  995.68  4996.1  992.38  4998.8  991.88
  5002.1  992.38  5053.4  998.69    5133  998.76  5294.2 1010.63    5547 1024.17
  5665.7 1029.85  5844.7  1047.4  5873.3  1048.9  6002.8 1051.58  6156.3 1055.27
  6172.6 1055.83  6363.7 1062.67  6699.7 1072.15  6813.8 1084.28  6887.8 1086.87
#Mann= 18 ,-1 , 0
  3415.4     .05       0  3435.6      .1       0  3907.2     .05       0
  3910.2      .1       0  3957.4     .05       0  4506.7      .1       0
  4775.4     .05       0    4871      .1       0  4996.1     .07       0
  5002.1      .1       0    5547     .05       0  5665.7      .1       0
  5844.7     .05       0  5873.3      .1       0  6002.8     .05       0
  6156.3      .1       0  6172.6     .05       0  6363.7      .1       0
#XS Ineff= 2 , 0
         4859.09 1032.87
Permanent Ineff=
       T       T
Bank Sta=4917.2,5294.2
XS Rating Curve= 0 ,0
Exp/Cntr=0.3,0.1

Type RM Length L Ch R = 1 ,26911   ,681,681,681
BEGIN DESCRIPTION:
MILLER CREEK 39.0
END DESCRIPTION:
XS GIS Cut Line= 4
      2941017.42     10063387.43       2942518.8     10062425.01
      2942588.09     10061716.67      2943496.63     10060554.05
#Sta/Elev= 30
  2975.7 1093.81  3060.7 1083.29  3187.6 1073.45  3350.9 1060.83  3605.5 1051.76
    3820 1045.19  4089.4 1027.81  4549.6 1030.92  4731.3 1023.02  4864.2 1011.06
 4894.89 1006.58  4907.9  998.98  4931.2  994.92  5028.6  992.67  5031.4  992.17
  5034.6  992.67    5061  998.83  5132.1  1005.9  5159.4 1014.96  5356.2 1019.26
  5487.1    1029  5587.8 1044.65  5677.7 1046.91  5857.3 1048.22  6035.4 1057.52
  6233.2 1062.46  6508.4 1076.88  6672.8 1087.32  6944.7 1097.04  6946.3 1097.04
#Mann= 20 ,-1 , 0
  2975.7      .1       0  3060.7      .1       0  3187.6     .05       0
  3350.9      .1       0  3605.5      .1       0    3820     .05       0
  4089.4     .05       0  4864.2      .1       0  5028.6     .07       0
  5034.6      .1       0    5061     .05       0  5159.4      .1       0
  5356.2      .1       0  5487.1     .16       0  5677.7      .1       0
  6035.4     .05       0  6233.2     .05       0  6508.4      .1       0
  6672.8      .1       0  6944.7      .1       0
#XS Ineff= 2 , 0
         4468.75 1032.72
Permanent Ineff=
       T       T
Bank Sta=4894.89,5132.1
XS Rating Curve= 0 ,0
Exp/Cntr=0.3,0.1

Type RM Length L Ch R = 1 ,26230   ,789,789,789
BEGIN DESCRIPTION:
MILLER CREEK 38.0
END DESCRIPTION:
XS GIS Cut Line= 4
      2941055.89     10063502.93      2943042.35      10062532.8
      2943396.51     10061824.46      2944834.86     10061362.96
#Sta/Elev= 30
  2422.2 1097.54  2478.4 1093.56  2571.9  1082.5  2808.8 1063.65    2857 1059.55
  2970.4  1054.6  3007.4 1053.45  3259.7 1047.47  3411.9 1034.64  3613.5 1024.47
  3934.4 1031.51  4137.8 1028.02  4647.2 1009.04  4742.6  1004.6  4991.2  992.26
  4993.9  991.76  4997.2  992.26  5033.3  992.68  5067.9 1003.82  5269.1 1016.51
  5311.9 1029.42  5368.7 1054.49  5450.2 1058.89    5763 1069.44    5898 1085.24
    6120  1091.6  6352.4 1109.06  6574.6 1116.41  6684.6 1127.44  6935.4 1134.38
#Mann= 16 ,-1 , 0
  2422.2      .1       0  2478.4     .05       0  2571.9      .1       0
  2808.8     .05       0    2857      .1       0  2970.4     .05       0
  3007.4      .1       0  3411.9     .05       0  4137.8      .1       0
  4647.2     .05       0  4991.2     .07       0  4997.2     .05       0
  5311.9     .16       0  5450.2      .1       0  6352.4     .05       0
  6574.6      .1       0
#XS Ineff= 2 , 0
         3968.75 1031.66
Permanent Ineff=
       T       T
Bank Sta=4742.6,5067.9
XS Rating Curve= 0 ,0
Exp/Cntr=0.3,0.1

Type RM Length L Ch R = 1 ,25441   ,1210,1210,1210
BEGIN DESCRIPTION:
MILLER CREEK 36.0
END DESCRIPTION:
XS GIS Cut Line= 3
      2941071.33      10063595.3      2943411.91     10062871.57
      2945190.41      10061724.4
#Sta/Elev= 30
    2138 1098.32  2281.5 1092.01  2394.3 1077.69  2718.3  1054.5  2868.2 1045.81
  2885.1 1044.97  3474.8 1019.19  3766.8  1028.2  4021.4  1027.7    4047 1027.09
  4198.8  1020.9  4706.3 1002.82  4813.8  998.62  4881.3  994.08  4908.9  988.31
  4993.7  985.29  4996.4  984.79  4999.7  985.29  5096.4  1002.8  5223.9 1020.79
  5262.7 1031.01  5277.9 1037.53    5293 1052.49  5350.8 1071.78  5380.8 1079.94
  5531.9 1091.35  5677.1 1107.91  6029.6 1120.43  6108.7 1129.18  6704.3 1149.19
#Mann= 15 ,-1 , 0
    2138      .1       0  2718.3     .05       0  2868.2      .1       0
  2885.1     .05       0  3766.8      .1       0  4021.4     .05       0
    4047      .1       0  4198.8     .05       0  4813.8      .1       0
  4993.7     .07       0  4999.7      .1       0  5223.9     .16       0
  5350.8      .1       0  6029.6     .16       0  6108.7      .1       0
#XS Ineff= 2 , 0
         4002.84 1028.44
Permanent Ineff=
       T       T
Bank Sta=4706.3,5096.4
XS Rating Curve= 0 ,0
Exp/Cntr=0.3,0.1

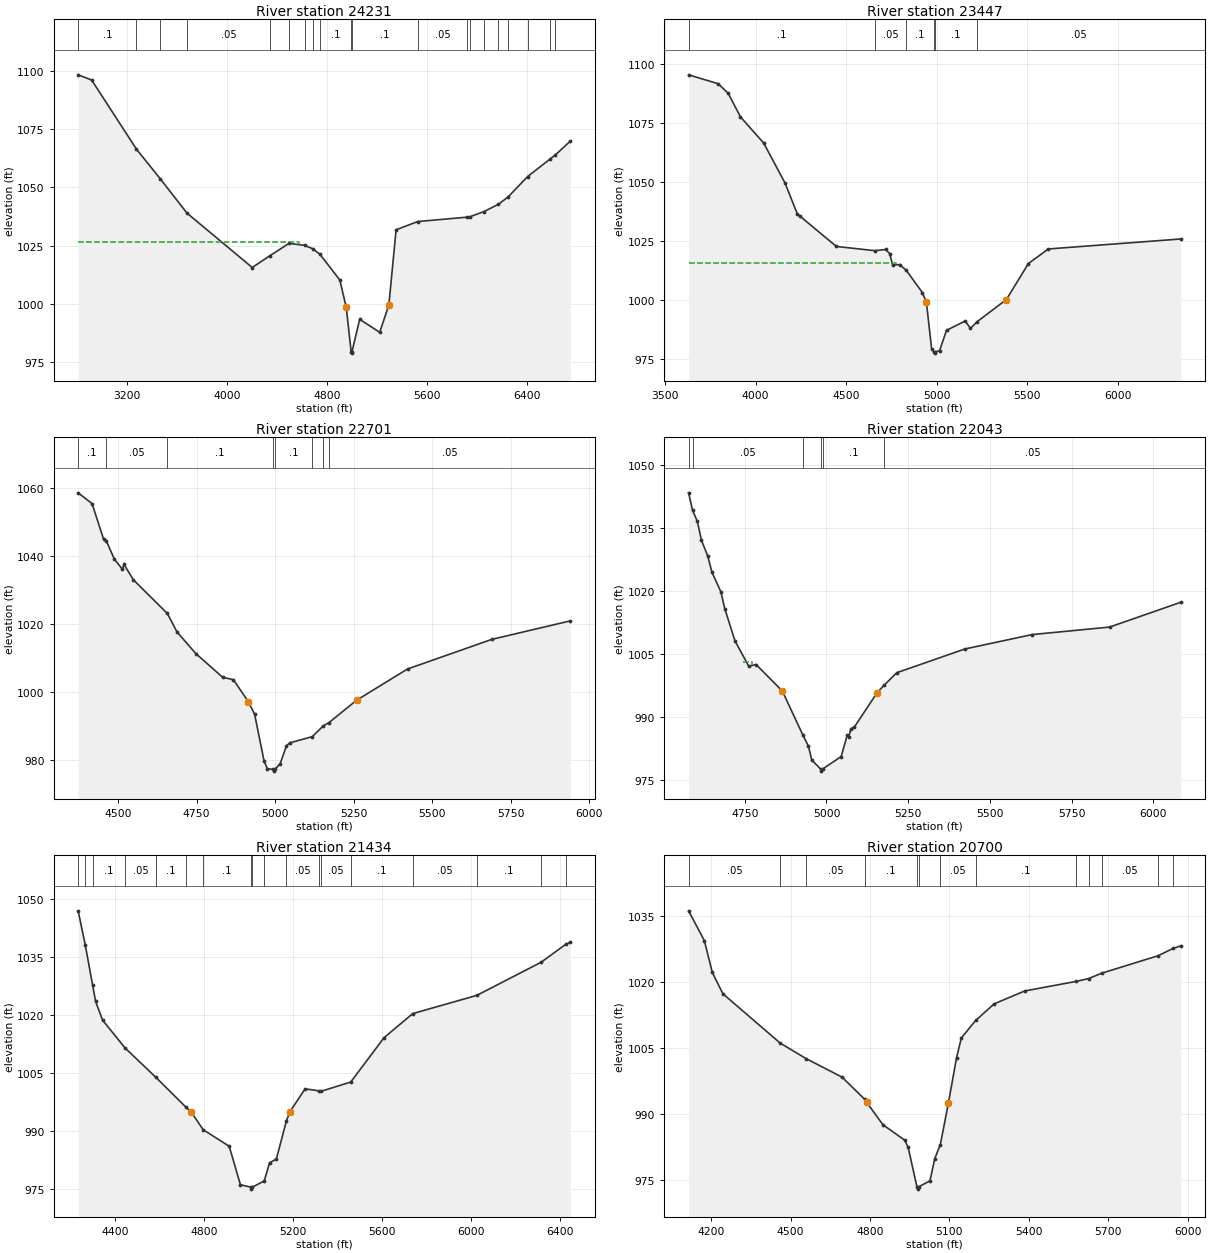
Type RM Length L Ch R = 1 ,24231   ,784,784,784
BEGIN DESCRIPTION:
MILLER CREEK 35.0
END DESCRIPTION:
XS GIS Cut Line= 4
      2941156.03     10063756.98      2942672.78     10063256.53
      2943696.79     10063895.57      2944797.76     10064165.04
#Sta/Elev= 30
  2810.8  1098.2  2918.7 1095.98  3276.8 1066.38  3467.8 1053.66  3681.5 1038.95
  4203.4 1015.66  4343.8 1020.68    4498 1025.99  4621.7 1025.14    4687 1023.71
  4745.2 1021.31  4903.6 1010.35  4955.5  998.59  4994.9  979.48  4997.7  978.98
  5000.9  979.48    5063  993.48  5223.2  987.89  5296.4  999.62  5354.2 1031.81
  5526.8 1035.35  5924.2 1037.23  5946.7 1037.43  6056.5 1039.61  6173.1 1042.74
  6250.6 1045.91    6406 1054.61  6583.2 1062.01  6627.6 1063.84  6748.5 1069.83
#Mann= 20 ,-1 , 0
  2810.8      .1       0  3276.8     .05       0  3467.8      .1       0
  3681.5     .05       0  4343.8      .1       0    4498     .05       0
  4621.7      .1       0    4687     .05       0  4745.2      .1       0
  4994.9     .07       0  5000.9      .1       0  5526.8     .05       0
  5924.2      .1       0  5946.7     .05       0  6056.5      .1       0
  6173.1     .05       0  6250.6     .16       0    6406      .1       0
  6583.2     .16       0  6627.6      .1       0
#XS Ineff= 2 , 0
         4573.86 1026.41
Permanent Ineff=
       T       T
Bank Sta=4955.5,5296.4
XS Rating Curve= 0 ,0
Exp/Cntr=0.3,0.1

Type RM Length L Ch R = 1 ,23447   ,746,746,746
BEGIN DESCRIPTION:
MILLER CREEK 34.0
END DESCRIPTION:
XS GIS Cut Line= 4
      2941502.46     10064165.05      2942403.31     10064018.76
      2943473.51      10064580.8      2944064.95      10064665.3
#Sta/Elev= 30
    3630 1095.62  3793.6 1091.85  3848.8 1087.81  3916.8 1077.77  4045.1  1066.7
  4162.9 1049.75  4229.8 1036.83  4243.9  1035.8  4446.6 1022.88  4658.1  1021.1
  4719.1  1021.6  4741.1 1019.82  4757.6 1014.92    4796 1015.22  4832.5 1012.76
  4921.2 1003.37  4943.8  999.25  4972.4  979.55  4985.8  978.18  4988.5  977.68
  4991.8  978.18  5016.5  978.73  5054.9  987.35  5158.4   991.3  5187.2  988.14
  5222.7  990.94  5385.7  1000.4  5506.7 1015.62  5616.9 1021.82  6348.9 1026.06
#Mann= 6 ,-1 , 0
    3630      .1       0  4658.1     .05       0  4832.5      .1       0
  4985.8     .07       0  4991.8      .1       0  5222.7     .05       0
#XS Ineff= 2 , 0
          4776.7 1015.89
Permanent Ineff=
       T       T
Bank Sta=4943.8,5385.7
XS Rating Curve= 0 ,0
Exp/Cntr=0.3,0.1

Type RM Length L Ch R = 1 ,22701   ,658,658,658
BEGIN DESCRIPTION:
MILLER CREEK 33.0
END DESCRIPTION:
XS GIS Cut Line= 3
      2942024.84      10064844.7       2943027.4      10065018.3
      2943569.92     10064927.16
#Sta/Elev= 30
  4372.7 1058.47    4417 1055.31  4453.7 1044.86  4461.9 1044.46    4488 1039.03
  4513.5 1036.06  4518.5  1037.5  4548.9 1032.94  4656.8 1023.09  4687.6 1017.66
  4747.4 1011.35  4833.1 1004.36  4866.9  1003.7  4914.3  997.28  4934.6  993.59
    4965  979.74  4975.2   977.6  4992.5  977.37  4995.2  976.87  4998.5  977.37
  5015.8  978.98    5036  984.28  5046.2  985.15    5118  986.97  5153.8  990.16
  5171.7  991.11  5259.3  997.65  5421.7 1006.82  5689.9  1015.5  5940.3 1020.93
#Mann= 8 ,-1 , 0
  4372.7      .1       0  4461.9     .05       0  4656.8      .1       0
  4992.5     .07       0  4998.5      .1       0    5118     .05       0
  5153.8      .1       0  5171.7     .05       0
Bank Sta=4914.3,5259.3
XS Rating Curve= 0 ,0
Exp/Cntr=0.3,0.1

Type RM Length L Ch R = 1 ,22043   ,609,609,609
BEGIN DESCRIPTION:
MILLER CREEK 32.0
END DESCRIPTION:
XS GIS Cut Line= 4
       2942202.9     10065527.82      2942437.23     10065601.59
      2942879.94     10065614.61      2943530.99     10065119.82
#Sta/Elev= 30
    4578 1043.42  4590.4 1039.21  4604.8 1036.63  4617.4 1032.13  4636.3 1028.41
  4649.8 1024.44  4676.9  1019.8  4688.7  1015.8  4720.1 1008.08  4762.1 1002.06
  4784.6 1002.46  4864.9  996.13  4928.4  985.53    4945  982.93    4955  979.68
    4982  977.52  4984.7  977.02    4988  977.52    5045   980.5  5063.3  985.55
  5068.3  985.26    5075  987.15    5085   987.5    5155  995.73    5177  997.56
  5215.1  1000.5  5423.4 1006.16  5629.3  1009.6  5866.3 1011.39  6084.3 1017.31
#Mann= 6 ,-1 , 0
    4578      .1       0  4590.4     .05       0  4928.4      .1       0
    4982     .07       0    4988      .1       0    5177     .05       0
#XS Ineff= 1 ,-1
 4744.66 4771.25 1002.94
Permanent Ineff=
       T
Bank Sta=4864.9,5155
XS Rating Curve= 0 ,0
Exp/Cntr=0.3,0.1

Type RM Length L Ch R = 1 ,21434   ,734,734,734
BEGIN DESCRIPTION:
MILLER CREEK 31.0
END DESCRIPTION:
XS GIS Cut Line= 4
      2942050.96     10065614.63      2942311.37     10066152.81
      2942814.84     10066256.98      2943196.56     10067289.36
#Sta/Elev= 30
  4232.6 1046.83  4264.5 1038.01  4297.2 1027.74  4311.1 1023.38  4342.7 1018.53
  4443.7 1011.35  4580.7 1003.83  4716.4  996.09  4740.3  994.82  4794.7  990.21
  4911.7  985.94  4961.9  975.99  5009.1  975.35  5011.8  974.85  5015.1  975.35
  5069.1  976.97    5093  981.65  5123.6  982.63    5169  992.56  5184.9   994.9
  5252.9 1000.79  5313.7 1000.28  5324.7 1000.16  5457.9 1002.55  5607.7 1014.02
  5736.6 1020.25  6025.2 1024.97  6313.8 1033.53  6426.9 1038.27  6445.3 1038.65
#Mann= 18 ,-1 , 0
  4232.6      .1       0  4264.5     .05       0  4297.2      .1       0
  4443.7     .05       0  4580.7      .1       0  4716.4     .05       0
  4794.7      .1       0  5009.1     .07       0  5015.1      .1       0
  5069.1     .12       0    5169     .05       0  5313.7     .12       0
  5324.7     .05       0  5457.9      .1       0  5736.6     .05       0
  6025.2      .1       0  6313.8     .16       0  6426.9     .05       0
#XS Ineff= 1 ,-1
 5393.41 5404.56 1001.37
Permanent Ineff=
       T
Bank Sta=4740.3,5184.9
XS Rating Curve= 0 ,0
Exp/Cntr=0.3,0.1

Type RM Length L Ch R = 1 ,20700   ,704,704,704
BEGIN DESCRIPTION:
MILLER CREEK 30.0
END DESCRIPTION:
XS GIS Cut Line= 3
      2941890.36     10065684.01      2941886.02     10066274.34
      2942193.81      10067505.5
#Sta/Elev= 30
  4114.6 1036.08  4174.3 1029.32  4204.3 1022.08  4244.3 1017.25  4461.2 1006.03
  4559.5  1002.5  4694.3  998.33  4780.6  993.26  4786.8  992.66  4848.6  987.53
  4931.1  984.01  4944.2  982.36  4977.3   973.4    4980   972.9  4983.3   973.4
  5026.6  974.79  5044.5  979.82  5065.7  983.02    5096  992.39  5126.9 1002.74
  5145.2 1007.25  5199.4  1011.2  5268.9 1014.96  5384.6 1017.89    5578 1020.05
  5625.5 1020.69  5674.8 1021.91  5888.9  1025.9  5944.6 1027.54    5974 1028.14
#Mann= 13 ,-1 , 0
  4114.6     .05       0  4461.2      .1       0  4559.5     .05       0
  4780.6      .1       0  4977.3     .07       0  4983.3      .1       0
  5065.7     .05       0  5199.4      .1       0    5578     .05       0
  5625.5      .1       0  5674.8     .05       0  5888.9      .1       0
  5944.6     .05       0
Bank Sta=4786.8,5096
XS Rating Curve= 0 ,0
Exp/Cntr=0.3,0.1

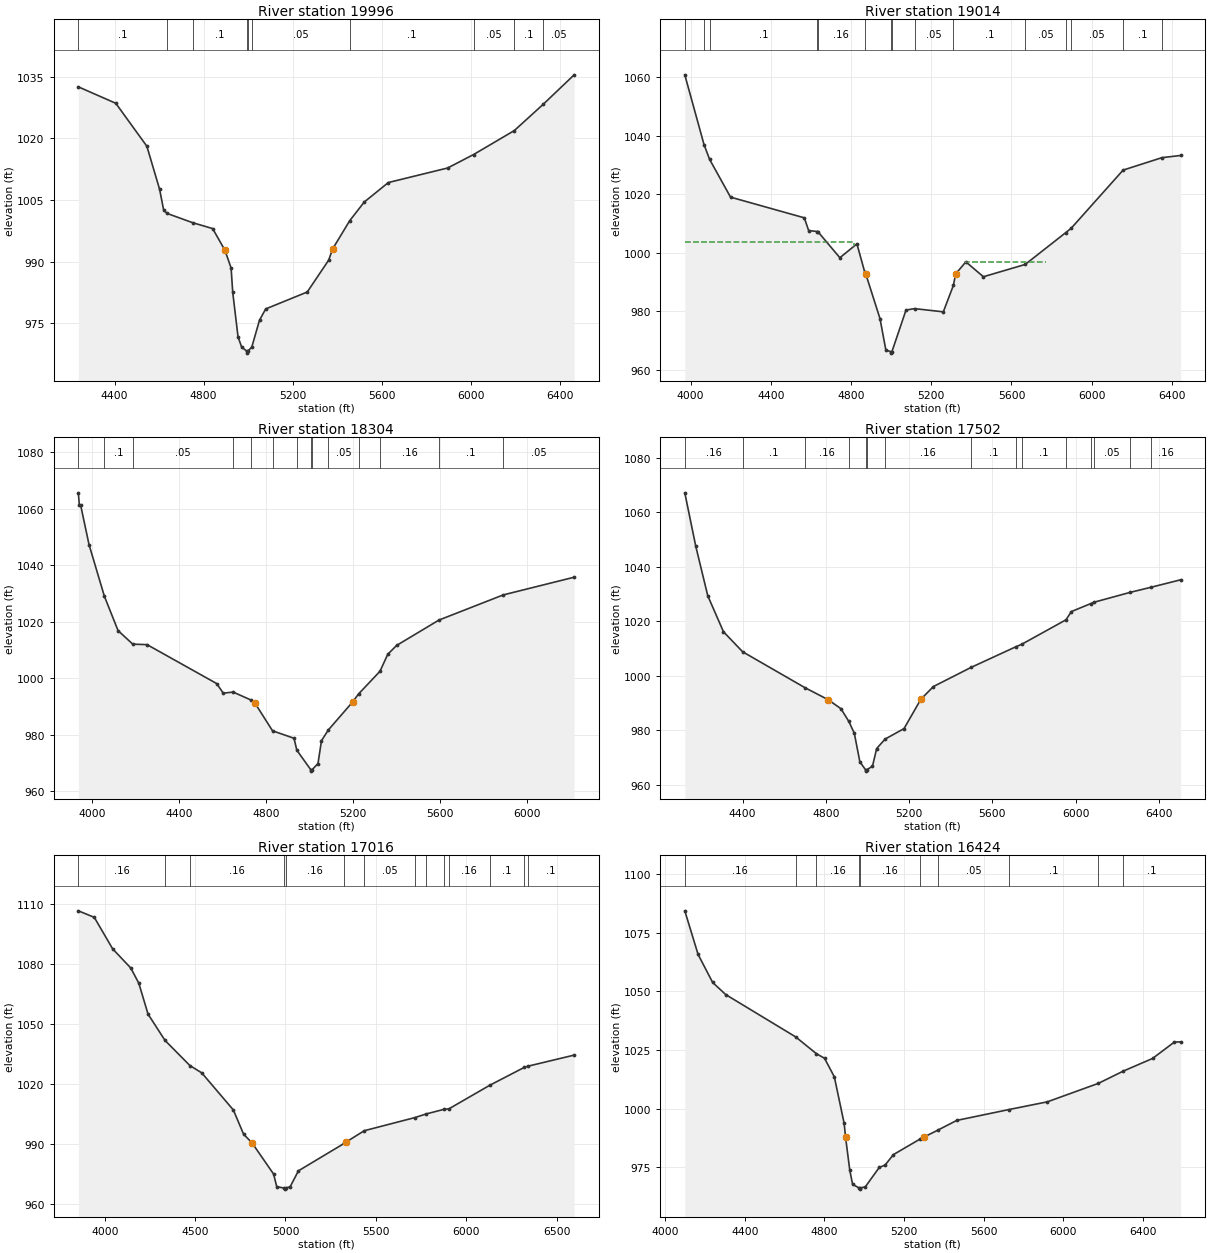
Type RM Length L Ch R = 1 ,19996   ,982,982,982
BEGIN DESCRIPTION:
MILLER CREEK 29.0
END DESCRIPTION:
XS GIS Cut Line= 3
      2941512.75     10065701.44      2941191.57     10066903.68
        2941482.     10067839.97
#Sta/Elev= 30
  4237.6  1032.5  4405.6 1028.51  4545.1 1018.07  4602.2 1007.61    4620 1002.69
  4634.5 1001.77  4750.7  999.49  4840.3  998.06  4895.4  992.79  4923.1  988.48
  4930.3  982.59  4954.2  971.75  4970.3  969.29  4992.6   968.3  4995.3   967.8
  4998.6   968.3    5016  969.28  5050.5  975.81  5078.4  978.54  5264.7  982.65
  5360.7  990.38  5378.6  993.12  5455.3  999.98  5520.4 1004.51  5628.6 1009.25
  5894.5 1012.78  6011.3 1016.06  6193.9 1021.88  6323.5 1028.26  6462.3 1035.42
#Mann= 10 ,-1 , 0
  4237.6      .1       0  4634.5     .05       0  4750.7      .1       0
  4992.6     .07       0  4998.6      .1       0    5016     .05       0
  5455.3      .1       0  6011.3     .05       0  6193.9      .1       0
  6323.5     .05       0
Bank Sta=4895.4,5378.6
XS Rating Curve= 0 ,0
Exp/Cntr=0.3,0.1

Type RM Length L Ch R = 1 ,19014   ,710,710,710
BEGIN DESCRIPTION:
MILLER CREEK 28.0
END DESCRIPTION:
XS GIS Cut Line= 4
      2939828.74     10065862.03      2940345.22     10066443.61
      2940783.59     10066764.79      2940987.58     10067897.63
#Sta/Elev= 30
  3971.2 1060.76    4067 1036.94  4094.9 1031.89  4199.2 1018.99  4567.1 1011.92
  4588.7 1007.58  4630.8 1007.25  4634.2 1007.24  4744.4   998.3  4829.5 1003.02
  4868.1  993.45  4873.5  992.76  4944.5   977.5  4973.8  966.75    4998  966.21
  5000.7  965.71    5004  966.21  5074.2  980.42  5116.8  980.91  5260.2  979.81
  5310.3  988.81  5321.9  992.78  5372.7  996.88    5460   991.8  5668.3  995.99
  5869.8 1006.82  5897.7 1008.35  6156.7 1028.22  6349.8 1032.46  6443.5 1033.22
#Mann= 15 ,-1 , 0
  3971.2     .16       0    4067     .05       0  4094.9      .1       0
  4630.8     .05       0  4634.2     .16       0  4868.1      .1       0
    4998     .07       0    5004      .1       0  5116.8     .05       0
  5310.3      .1       0  5668.3     .05       0  5869.8      .1       0
  5897.7     .05       0  6156.7      .1       0  6349.8     .05       0
#XS Ineff= 2 ,-1
  3971.2  4812.5  1003.7 5368.18 5770.45  996.95
Permanent Ineff=
       T       T
Bank Sta=4873.5,5321.9
XS Rating Curve= 0 ,0
Exp/Cntr=0.3,0.1

Type RM Length L Ch R = 1 ,18304   ,802,802,802
BEGIN DESCRIPTION:
MILLER CREEK 27.0
END DESCRIPTION:
XS GIS Cut Line= 4
      2939589.99     10065927.08      2939941.57     10066617.22
      2939984.98     10067298.64      2940388.62     10068014.79
#Sta/Elev= 30
  3936.4 1065.71  3941.2 1061.32  3946.8 1061.42  3985.6 1047.37  4056.1 1029.11
  4119.1 1016.93  4186.7 1012.15  4252.5 1011.97  4572.3   998.2  4602.7   994.8
  4648.3  995.18  4730.3  992.36  4747.5  991.39  4829.1  981.48  4927.9  978.83
    4941  974.58    5005   967.7  5007.8   967.2    5011   967.7  5038.1  969.87
  5054.2  977.98  5085.9  981.79  5198.4  991.77  5224.4   994.5  5323.2 1002.55
  5358.8 1008.55  5399.6 1011.69  5594.4 1020.68  5889.5 1029.57  6215.8 1035.84
#Mann= 14 ,-1 , 0
  3936.4     .16       0  4056.1      .1       0  4186.7     .05       0
  4648.3      .1       0  4730.3     .05       0  4829.1     .16       0
    4941      .1       0    5005     .07       0    5011      .1       0
  5085.9     .05       0  5224.4      .1       0  5323.2     .16       0
  5594.4      .1       0  5889.5     .05       0
Bank Sta=4747.5,5198.4
XS Rating Curve= 0 ,0
Exp/Cntr=0.3,0.1

Type RM Length L Ch R = 1 ,17502   ,486,486,486
BEGIN DESCRIPTION:
MILLER CREEK 26.0
END DESCRIPTION:
XS GIS Cut Line= 3
      2939047.48     10066031.33      2939260.15     10067506.98
      2939733.22     10068262.15
#Sta/Elev= 30
  4122.1 1067.14    4175 1047.46  4232.4 1029.37  4307.8 1016.16  4400.1 1008.79
  4698.7  995.65  4811.6  991.17  4872.2   987.9  4910.1  983.24  4936.5   978.9
  4963.1  968.41  4990.4  965.49  4993.2  964.99  4996.4  965.49  5023.7  966.78
  5043.9  973.29  5084.5  976.76  5175.3   980.6  5256.1  991.36  5316.7  996.05
    5498 1003.08    5715 1010.72  5739.8 1011.51  5953.4 1020.53    5979 1023.55
  6072.6 1026.49  6087.9 1026.98  6261.9 1030.61  6363.7 1032.51  6504.1 1035.22
#Mann= 15 ,-1 , 0
  4122.1     .16       0  4400.1      .1       0  4698.7     .16       0
  4910.1     .05       0  4990.4    .035       0  4996.4     .05       0
  5084.5     .16       0    5498      .1       0    5715     .16       0
  5739.8      .1       0  5953.4     .05       0  6072.6      .1       0
  6087.9     .05       0  6261.9      .1       0  6363.7     .16       0
Bank Sta=4811.6,5256.1
XS Rating Curve= 0 ,0
Exp/Cntr=0.3,0.1

Type RM Length L Ch R = 1 ,17016   ,592,592,592
BEGIN DESCRIPTION:
MILLER CREEK 25.0
END DESCRIPTION:
XS GIS Cut Line= 4
      2937858.22     10066317.73      2938578.73     10066673.64
      2939008.41     10067598.12      2939546.62     10068344.67
#Sta/Elev= 30
  3853.9 1106.62  3942.2 1103.35  4043.8 1087.58  4144.1 1077.99  4188.8 1070.31
  4239.5 1054.92  4333.5 1041.75  4471.3 1029.14  4536.8  1025.5  4711.7 1006.91
  4768.5  994.75  4814.3  990.54  4934.3  974.83  4951.7  968.54  4994.4  967.79
  4997.2  967.29  5000.4  967.79  5025.8  968.46  5071.6  976.45  5325.1   990.2
  5334.4   990.8  5435.8  996.53  5715.3 1003.09  5779.5 1004.95  5874.6 1007.18
  5904.6  1007.5  6129.5 1019.25  6321.7 1028.25  6340.8 1028.82  6597.3 1034.39
#Mann= 14 ,-1 , 0
  3853.9     .16       0  4333.5      .1       0  4471.3     .16       0
  4994.4     .07       0  5000.4     .16       0  5325.1      .1       0
  5435.8     .05       0  5715.3      .1       0  5779.5     .05       0
  5874.6      .1       0  5904.6     .16       0  6129.5      .1       0
  6321.7     .05       0  6340.8      .1       0
Bank Sta=4814.3,5334.4
XS Rating Curve= 0 ,0
Exp/Cntr=0.3,0.1

Type RM Length L Ch R = 1 ,16424   ,546,546,546
BEGIN DESCRIPTION:
MILLER CREEK 24.0
END DESCRIPTION:
XS GIS Cut Line= 4
      2937445.94     10066908.03      2938079.59     10067146.73
      2938782.72     10067823.82      2939268.52     10068509.14
#Sta/Elev= 30
  4097.6 1084.34  4164.4 1065.76  4237.7 1053.81  4303.4 1048.65  4655.2 1030.61
    4759 1023.48  4800.2 1021.51  4849.6 1013.59    4899  993.71  4906.2  987.76
  4927.3  973.74  4941.4  967.79    4974  966.24  4976.7  965.74    4980  966.24
  5005.3  966.71    5076  975.04  5104.3  975.95  5146.8  980.46  5281.2  987.11
  5302.1     988  5369.3  990.84    5465  995.02  5728.6  999.67  5920.7 1002.94
  6176.9  1010.8    6303 1016.05  6449.7 1021.42  6559.2  1028.4  6590.9  1028.5
#Mann= 10 ,-1 , 0
  4097.6     .16       0  4655.2      .1       0    4759     .16       0
    4974     .07       0    4980     .16       0  5281.2      .1       0
  5369.3     .05       0  5728.6      .1       0  6176.9     .16       0
    6303      .1       0
Bank Sta=4906.2,5302.1
XS Rating Curve= 0 ,0
Exp/Cntr=0.3,0.1