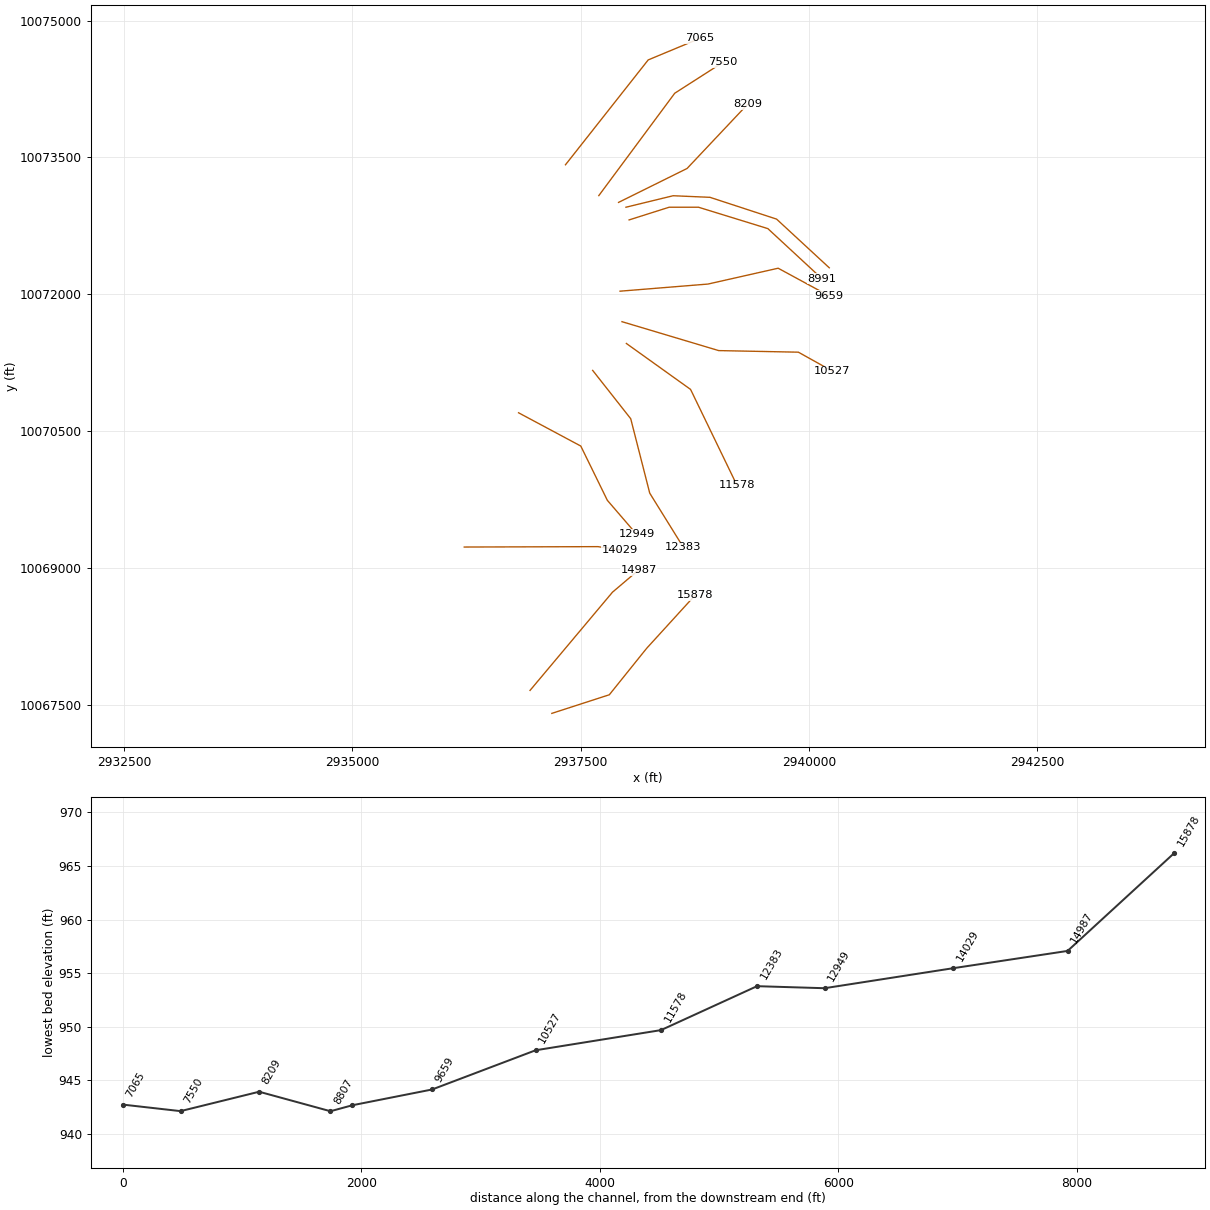
HEC-RAS study MILLER CREEK.prj: MILLER CREEK Base Level Engineering

--- MILLER CREEK.g01 (geometry) --- (continued)

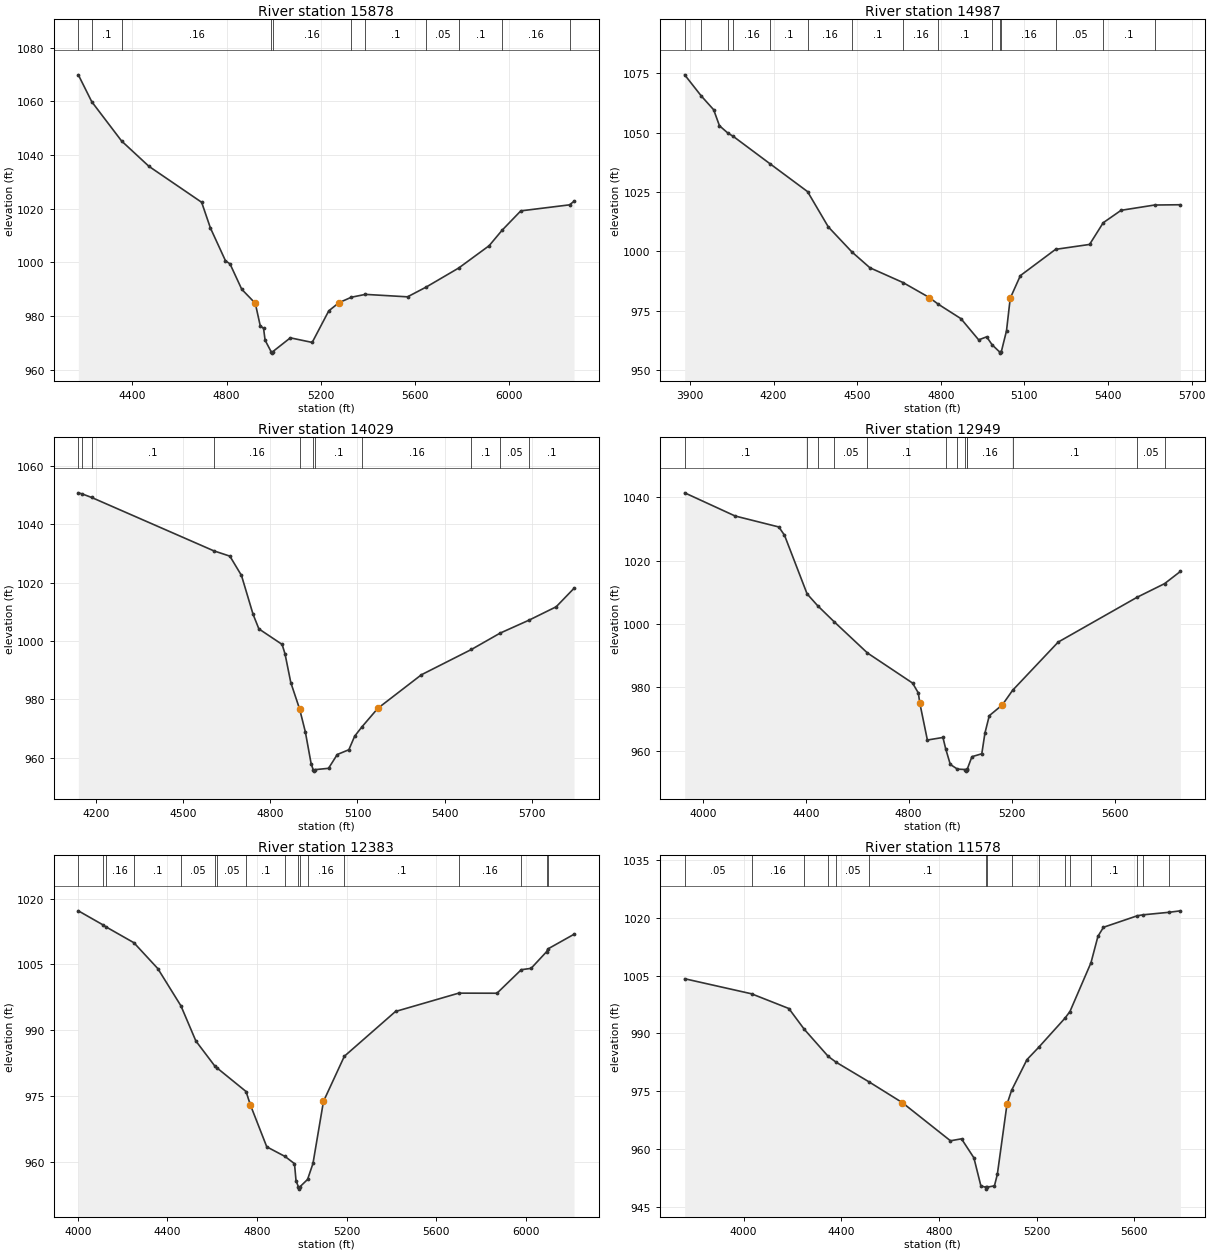
Type RM Length L Ch R = 1 ,15878   ,891,891,891
BEGIN DESCRIPTION:
MILLER CREEK 23.0
END DESCRIPTION:
XS GIS Cut Line= 4
      2937185.49     10067407.15      2937814.84     10067611.14
      2938222.82     10068118.95      2938756.71     10068704.92
#Sta/Elev= 30
  4170.6 1069.93  4227.8 1059.88  4354.5 1045.25  4470.5 1035.82  4694.4 1022.42
  4731.6 1012.85  4795.6 1000.63    4815  999.43  4864.8  989.98  4922.3  984.76
  4943.2  976.43  4957.5  975.37    4964  970.99  4989.8  966.68  4992.5  966.18
  4995.8  966.68  5071.2  971.88    5164  970.17  5234.4  981.94  5277.6  984.98
  5330.6  987.02  5389.9  988.08    5569  987.17  5647.6  990.78    5786  997.89
  5915.7 1006.23  5970.6 1011.99  6050.1 1019.21    6257 1021.46  6276.3 1022.78
#Mann= 11 ,-1 , 0
  4170.6     .16       0  4227.8      .1       0  4354.5     .16       0
  4989.8     .07       0  4995.8     .16       0  5330.6     .05       0
  5389.9      .1       0  5647.6     .05       0    5786      .1       0
  5970.6     .16       0    6257      .1       0
Bank Sta=4922.3,5277.6
XS Rating Curve= 0 ,0
Exp/Cntr=0.3,0.1

Type RM Length L Ch R = 1 ,14987   ,958,958,958
BEGIN DESCRIPTION:
MILLER CREEK 22.0
END DESCRIPTION:
XS GIS Cut Line= 3
       2936946.8     10067658.91      2937849.56     10068735.27
      2938134.72     10068977.22
#Sta/Elev= 30
  3880.9 1074.43  3940.7 1065.48  3984.9 1059.71  4005.7 1052.96  4037.1 1049.75
  4053.6 1048.62  4188.7 1036.79  4321.8 1025.19  4396.2 1010.32  4481.2  999.72
  4545.6  993.07  4664.1  986.86  4758.9  980.51  4790.6  977.73  4872.1  971.63
  4935.9  962.67  4964.5  963.96    4984  960.61  5010.9  957.58  5013.7  957.08
  5016.9  957.58  5035.7  966.49  5049.1  980.23  5085.5  989.77  5211.8 1000.84
  5333.8 1002.91  5382.8 1012.07  5446.9  1017.3    5567 1019.53  5659.7 1019.65
#Mann= 15 ,-1 , 0
  3880.9      .1       0  3940.7     .16       0  4037.1      .1       0
  4053.6     .16       0  4188.7      .1       0  4321.8     .16       0
  4481.2      .1       0  4664.1     .16       0  4790.6      .1       0
    4984     .16       0  5010.9     .07       0  5016.9     .16       0
  5211.8     .05       0  5382.8      .1       0    5567     .16       0
Bank Sta=4758.9,5049.1
XS Rating Curve= 0 ,0
Exp/Cntr=0.3,0.1

Type RM Length L Ch R = 1 ,14029   ,1080,1080,1080
BEGIN DESCRIPTION:
MILLER CREEK 21.0
END DESCRIPTION:
XS GIS Cut Line= 3
       2936226.3     10069230.07      2937688.97     10069234.41
      2937932.03     10069199.68
#Sta/Elev= 30
  4138.2 1050.76  4151.9 1050.37  4183.9 1049.18    4605  1030.9  4660.4 1029.08
  4700.4 1022.46  4740.4 1009.15  4760.4 1004.17  4840.4  998.86  4850.4  995.63
  4870.4  985.78  4900.4  976.83    4901  976.62  4920.4  968.95  4940.4  958.04
  4947.4  955.97  4950.1  955.47  4953.4  955.97  5000.4  956.43  5030.4  961.16
  5070.4  962.79  5090.4  967.43    5116  970.69  5170.4  976.99  5320.4  988.46
    5493  997.14  5591.6 1002.72  5691.8 1007.19  5784.8 1011.74  5846.4 1018.08
#Mann= 11 ,-1 , 0
  4138.2      .1       0  4151.9     .16       0  4183.9      .1       0
    4605     .16       0    4901      .1       0  4947.4     .07       0
  4953.4      .1       0    5116     .16       0    5493      .1       0
  5591.6     .05       0  5691.8      .1       0
Bank Sta=4900.4,5170.4
XS Rating Curve= 0 ,0
Exp/Cntr=0.3,0.1

Type RM Length L Ch R = 1 ,12949   ,566,566,566
BEGIN DESCRIPTION:
MILLER CREEK 19.0
END DESCRIPTION:
XS GIS Cut Line= 4
      2936820.93     10070701.41      2937502.34     10070336.84
      2937793.14     10069742.22      2938113.89     10069369.45
#Sta/Elev= 30
  3929.5 1041.38  4125.6 1034.07  4295.4 1030.61  4317.4 1028.01  4405.2 1009.51
  4446.7 1005.74  4510.1 1000.74  4639.9  990.86  4815.1  981.38  4837.6  978.25
  4843.2  975.08  4872.7  963.41  4933.2  964.22  4943.8  960.66  4961.8  955.71
  4989.4  954.24  5020.3   954.1    5023   953.6  5026.3   954.1  5027.6  954.21
  5045.8  958.15  5084.2  959.08  5096.4  965.62  5113.3  971.09  5163.9  974.49
  5203.9  979.09    5381   994.3  5687.7 1008.44  5794.6 1012.74    5856 1016.59
#Mann= 13 ,-1 , 0
  3929.5      .1       0  4405.2     .05       0  4446.7      .1       0
  4510.1     .05       0  4639.9      .1       0  4943.8     .05       0
  4989.4      .1       0  5020.3     .07       0  5026.3      .1       0
  5027.6     .16       0  5203.9      .1       0  5687.7     .05       0
  5794.6      .1       0
Bank Sta=4843.2,5163.9
XS Rating Curve= 0 ,0
Exp/Cntr=0.3,0.1

Type RM Length L Ch R = 1 ,12383   ,805,805,805
BEGIN DESCRIPTION:
MILLER CREEK 18.0
END DESCRIPTION:
XS GIS Cut Line= 4
      2937632.55     10071165.83      2938049.21     10070636.32
      2938257.55     10069820.34      2938625.52     10069227.26
#Sta/Elev= 30
    4002 1017.22  4110.7 1014.06  4124.3  1013.6  4250.2 1009.95  4356.9 1004.06
  4460.3  995.56  4526.9  987.56  4612.1  981.81  4620.7  981.44    4751  976.04
    4770  973.04  4843.6  963.43  4925.4  961.23  4967.4  959.59  4974.3  955.69
  4985.1  954.29  4987.8  953.79  4991.1  954.29  5025.8     956    5050  959.65
  5096.8  973.78    5190  984.07  5418.5  994.28  5700.9  998.46  5871.7  998.44
  5980.2  1003.8  6024.1 1004.11    6093 1007.89  6098.9 1008.53  6215.9 1011.88
#Mann= 17 ,-1 , 0
    4002     .16       0  4110.7      .1       0  4124.3     .16       0
  4250.2      .1       0  4460.3     .05       0  4612.1      .1       0
  4620.7     .05       0    4751      .1       0  4925.4     .05       0
  4985.1     .07       0  4991.1     .05       0  5025.8     .16       0
    5190      .1       0  5700.9     .16       0  5980.2      .1       0
    6093     .16       0  6098.9      .1       0
Bank Sta=4770,5096.8
XS Rating Curve= 0 ,0
Exp/Cntr=0.3,0.1

Type RM Length L Ch R = 1 ,11578   ,1051,1051,1051
BEGIN DESCRIPTION:
MILLER CREEK 17.0
END DESCRIPTION:
XS GIS Cut Line= 3
      2938001.51     10071460.94      2938704.59      10070957.5
      2939212.01     10069907.97
#Sta/Elev= 30
  3758.5 1004.18  4032.4 1000.28  4185.2  996.47  4248.2   991.1  4346.6  984.06
  4379.1  982.55  4513.4  977.48  4649.6  972.11  4847.2  962.21  4892.4  962.72
  4943.1   957.8  4971.8  950.53    4991  950.19  4993.7  949.69    4997  950.19
  5027.3  950.54  5039.1  953.49  5078.7  971.67  5097.7   975.3  5160.6  983.24
  5208.7  986.43  5315.7  993.93  5336.6  995.69  5422.7 1008.32  5451.3 1015.18
  5473.9 1017.51    5613  1020.5  5636.8 1020.74  5743.9  1021.4    5789 1021.77
#Mann= 16 ,-1 , 0
  3758.5     .05       0  4032.4     .16       0  4248.2      .1       0
  4346.6     .16       0  4379.1     .05       0  4513.4      .1       0
    4991     .07       0    4997      .1       0  5097.7     .16       0
  5208.7     .05       0  5315.7      .1       0  5336.6     .05       0
  5422.7      .1       0    5613     .05       0  5636.8      .1       0
  5743.9     .05       0
Bank Sta=4649.6,5078.7
XS Rating Curve= 0 ,0
Exp/Cntr=0.3,0.1

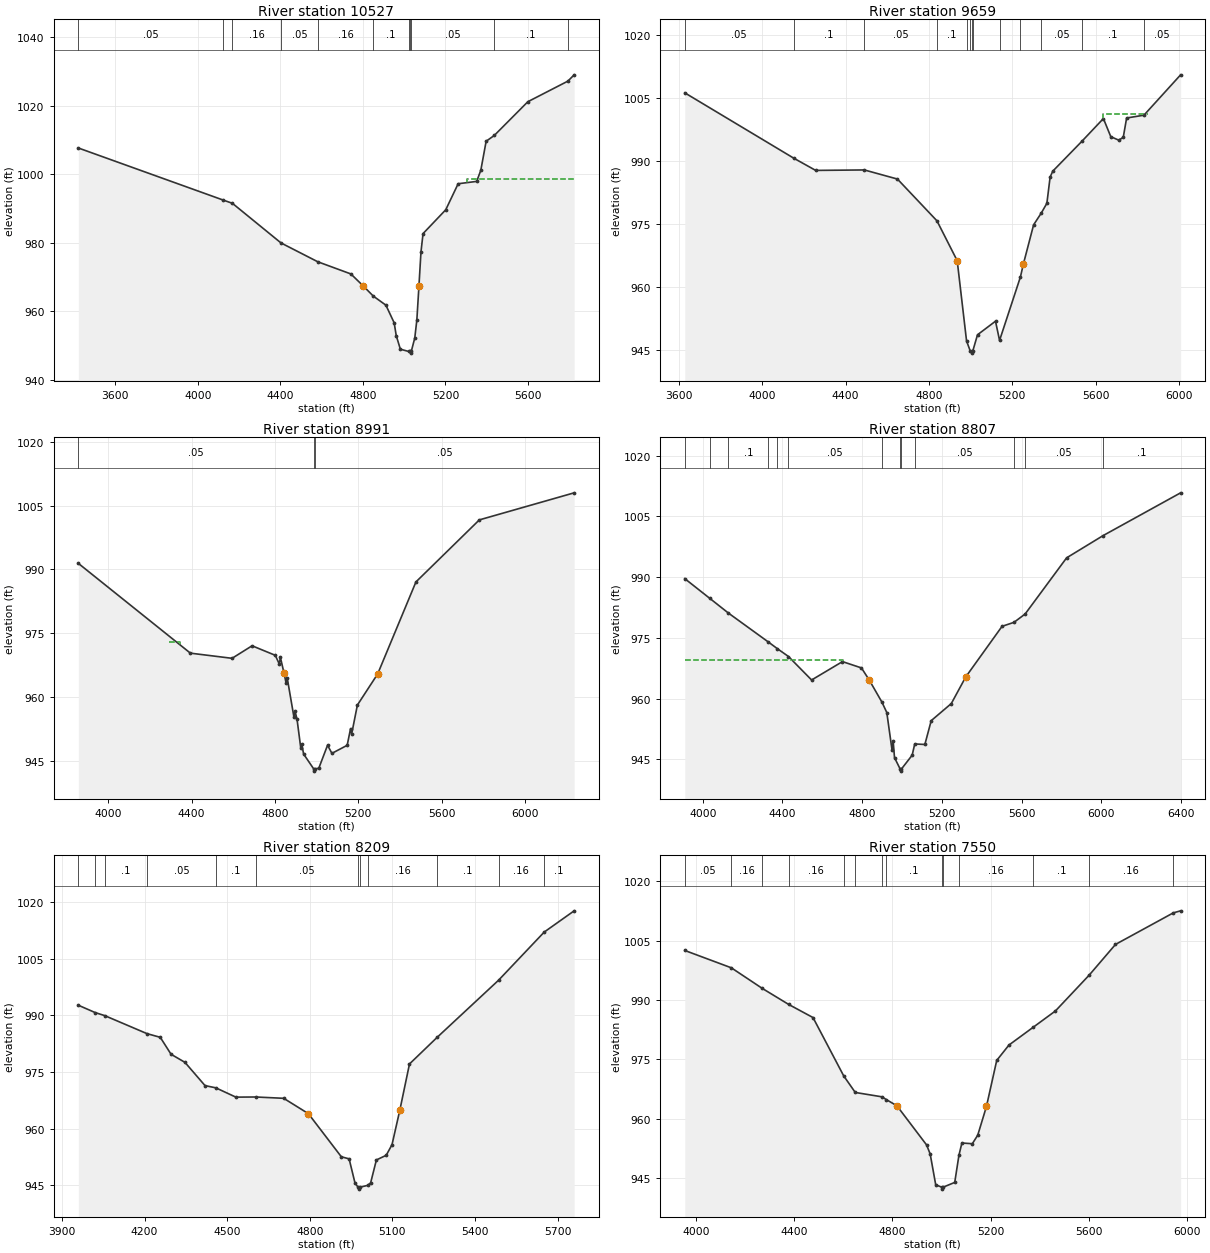
Type RM Length L Ch R = 1 ,10527   ,868,868,868
BEGIN DESCRIPTION:
MILLER CREEK 16.0
END DESCRIPTION:
XS GIS Cut Line= 4
      2937953.73     10071699.68      2939012.75     10071382.84
      2939885.15     10071365.48      2940256.98     10071157.95
#Sta/Elev= 30
  3420.4 1007.62  4123.4  992.42  4167.3  991.49  4403.1  979.93  4581.4  974.44
  4741.6   970.9  4801.6   967.4  4850.5  964.43  4911.6  961.79  4951.6  956.65
  4961.6  952.93  4981.6  948.95  5021.1  948.31  5028.6  948.31  5031.4  947.81
  5034.6  948.31  5051.6  952.26  5061.6  957.52  5071.6  967.25  5081.6  977.34
  5091.6  982.66  5201.7  989.61  5261.7  997.19  5351.7  997.88  5371.7 1001.13
  5397.5 1009.59  5436.9 1011.27  5599.7 1021.11  5793.7 1027.11  5824.2 1028.95
#Mann= 11 ,-1 , 0
  3420.4     .05       0  4123.4      .1       0  4167.3     .16       0
  4403.1     .05       0  4581.4     .16       0  4850.5      .1       0
  5021.1     .05       0  5028.6     .07       0  5034.6     .05       0
  5436.9      .1       0  5793.7     .05       0
#XS Ineff= 2 , 0
                         5302.84          998.57
Permanent Ineff=
       T       T
Bank Sta=4801.6,5071.6
XS Rating Curve= 0 ,0
Exp/Cntr=0.3,0.1

Type RM Length L Ch R = 1 ,9659    ,668,668,668
BEGIN DESCRIPTION:
MILLER CREEK 15.0
END DESCRIPTION:
XS GIS Cut Line= 4
      2937931.99     10072033.88      2938895.57     10072112.01
       2939663.8     10072285.62      2940214.26     10071986.55
#Sta/Elev= 30
  3627.7 1006.13  4150.9  990.57  4256.2  987.66  4489.8  987.77  4648.7   985.6
  4838.5  975.65  4935.7  966.16  4980.6  947.06  4998.3  944.66  5004.5  944.65
  5007.2  944.15  5010.5  944.65  5033.2  948.52  5119.6  951.75  5139.1  947.18
  5239.3  962.29  5253.6  965.39  5302.6   974.7  5339.5  977.51  5366.3  979.83
  5381.9  986.09  5394.8  987.49  5534.4  994.59  5637.7 1000.01  5673.2  995.69
  5711.2  994.87    5733  995.52  5749.2 1000.14  5832.4 1000.81  6008.5 1010.42
#Mann= 13 ,-1 , 0
  3627.7     .05       0  4150.9      .1       0  4489.8     .05       0
  4838.5      .1       0  4980.6     .16       0  4998.3      .1       0
  5004.5     .07       0  5010.5      .1       0  5139.1     .16       0
  5239.3      .1       0  5339.5     .05       0  5534.4      .1       0
  5832.4     .05       0
#XS Ineff= 1 ,-1
  5635.8 5853.98 1001.18
Permanent Ineff=
       T
Bank Sta=4935.7,5253.6
XS Rating Curve= 0 ,0
Exp/Cntr=0.3,0.1

Type RM Length L Ch R = 1 ,8991    ,184,184,184
BEGIN DESCRIPTION:
MILLER CREEK 14.0
END DESCRIPTION:
XS GIS Cut Line= 5
      2938031.82     10072815.12      2938470.22     10072954.02
       2938791.4     10072954.02      2939550.95     10072719.65
      2940141.21     10072172.79
#Sta/Elev= 30
  3856.3  991.43  4394.4  970.36  4594.4  969.15  4690.5  972.09  4801.7  969.86
  4821.2  967.82  4826.4  969.38  4843.6  965.75  4853.8  963.35    4859  964.61
  4891.7   955.3  4896.9   956.7  4906.4  954.84  4924.4  948.07  4929.6  948.95
  4937.8   946.7  4986.7  943.18  4989.4  942.68  4992.7  943.18    5011  943.38
  5052.9  948.76  5073.8  946.85  5147.1  948.74  5163.4  952.66  5168.6  951.39
  5196.1  958.18  5293.6  965.49  5477.2  987.07  5781.6 1001.63  6236.9 1007.98
#Mann= 3 ,-1 , 0
  3856.3     .05       0  4986.7     .04       0  4992.7     .05       0
#XS Ineff= 2 ,-1
 4291.46 4344.43  973.09 4376.33 4657.47  970.92
Permanent Ineff=
       T       T
Bank Sta=4843.6,5293.6
XS Rating Curve= 0 ,0
Exp/Cntr=0.3,0.1

Type RM Length L Ch R = 1 ,8807    ,598,598,598
BEGIN DESCRIPTION:
MILLER CREEK 13.0
END DESCRIPTION:
XS GIS Cut Line= 5
      2937997.09     10072954.01      2938513.62     10073079.89
      2938917.27     10073062.53      2939646.43     10072823.82
      2940223.55     10072290.09
#Sta/Elev= 30
  3909.7  989.64  4034.7  984.79  4128.7  981.14  4329.7  973.98    4375  972.33
  4430.2  970.42  4546.3  964.62  4701.2  969.16  4796.5   967.6  4836.6  964.53
  4899.2  959.16  4923.7  956.59  4950.3  947.23  4955.6  949.57  4962.4  945.46
  4990.9  942.62  4993.7  942.12  4996.9  942.62  5051.1  946.06    5064  948.83
  5114.8   948.7  5146.7  954.58  5247.5   958.8  5320.1  965.38  5502.3  977.87
    5562  978.85  5618.1  980.91  5826.4  994.78  6009.6 1000.27  6398.7 1010.83
#Mann= 13 ,-1 , 0
  3909.7      .1       0  4034.7     .05       0  4128.7      .1       0
  4329.7     .05       0    4375      .1       0  4430.2     .05       0
  4899.2      .1       0  4990.9     .07       0  4996.9      .1       0
    5064     .05       0    5562     .16       0  5618.1     .05       0
  6009.6      .1       0
#XS Ineff= 2 , 0
          4701.7  969.44
Permanent Ineff=
       T       T
Bank Sta=4836.6,5320.1
XS Rating Curve= 0 ,0
Exp/Cntr=0.3,0.1

Type RM Length L Ch R = 1 ,8209    ,659,659,659
BEGIN DESCRIPTION:
MILLER CREEK 12.0
END DESCRIPTION:
XS GIS Cut Line= 3
      2937916.13     10073006.93      2938666.42     10073378.69
      2939327.43     10074080.18
#Sta/Elev= 30
  3959.3  992.72  4020.5  990.77  4055.3  989.96  4208.9  985.18  4256.9  984.21
  4296.2  979.71  4346.6  977.57  4419.5   971.4  4458.7  970.81  4531.6  968.34
  4603.8  968.38  4705.3  968.03    4795  963.96  4914.7  952.52    4943  951.97
  4964.4  945.55  4975.6  944.44  4978.4  943.94  4981.6  944.44  5010.1  944.93
  5021.1  945.59  5042.1  951.68  5077.7  952.91  5098.8  955.73  5127.1  964.85
  5162.3  977.14  5263.5  984.25  5485.7  999.34  5651.8 1012.13  5760.5 1017.76
#Mann= 12 ,-1 , 0
  3959.3      .1       0  4020.5     .05       0  4055.3      .1       0
  4208.9     .05       0  4458.7      .1       0  4603.8     .05       0
  4975.6    .035       0  4981.6     .05       0  5010.1     .16       0
  5263.5      .1       0  5485.7     .16       0  5651.8      .1       0
Bank Sta=4795,5127.1
XS Rating Curve= 0 ,0
Exp/Cntr=0.3,0.1

Type RM Length L Ch R = 1 ,7550    ,485,485,485
BEGIN DESCRIPTION:
MILLER CREEK 11.0
END DESCRIPTION:
XS GIS Cut Line= 3
      2937699.87     10073081.29      2938531.23     10074203.29
      2939058.46     10074541.26
#Sta/Elev= 30
  3952.8 1002.52  4142.7  998.13  4269.1  992.91  4376.7  988.86  4475.9  985.54
    4601  970.79  4648.2  966.59  4757.7  965.48  4774.6   964.8  4818.2  963.21
  4939.2  953.31  4953.8  951.03  4976.4  943.23  5000.9  942.63  5003.6  942.13
  5006.9  942.63    5054  943.83  5071.2  950.72  5083.2   953.8  5125.8  953.62
  5147.9  955.79  5183.4  963.05  5225.3   974.7  5275.2  978.59    5375  983.13
  5464.7  987.21  5603.2  996.33  5709.8 1004.05  5945.5 1012.03  5975.5 1012.55
#Mann= 14 ,-1 , 0
  3952.8     .05       0  4142.7     .16       0  4269.1      .1       0
  4376.7     .16       0    4601     .05       0  4648.2     .16       0
  4757.7     .05       0  4774.6      .1       0  5000.9     .07       0
  5006.9      .1       0  5071.2     .16       0    5375      .1       0
  5603.2     .16       0  5945.5     .05       0
Bank Sta=4818.2,5183.4
XS Rating Curve= 0 ,0
Exp/Cntr=0.3,0.1

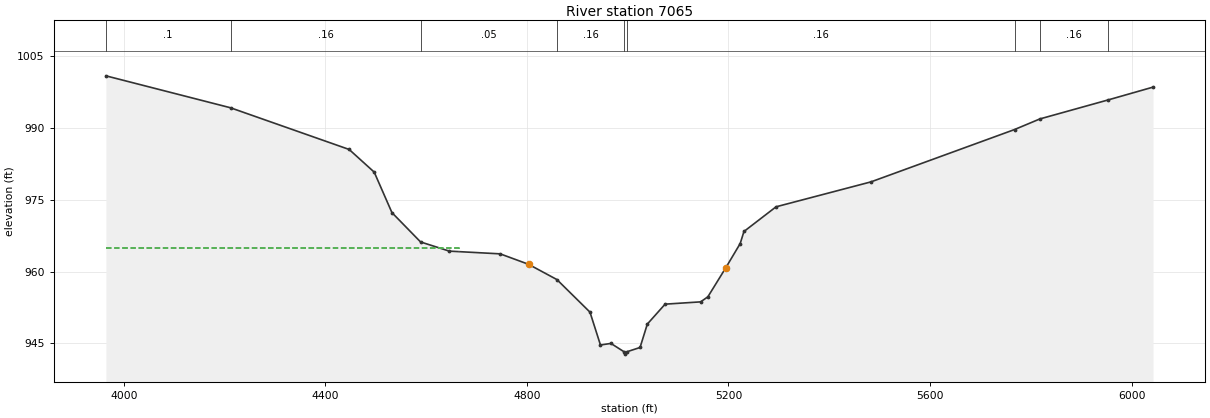
Type RM Length L Ch R = 1 ,7065    ,818,818,818
BEGIN DESCRIPTION:
MILLER CREEK 10.0
END DESCRIPTION:
XS GIS Cut Line= 3
      2937334.87     10073419.23      2938240.59     10074568.28
      2938808.37     10074804.86
#Sta/Elev= 30
  3964.5 1000.94  4211.8  994.26  4447.3  985.54    4497   980.8  4532.2  972.33
    4589   966.2  4646.1  964.28    4747  963.71  4803.2  961.53  4859.6  958.33
  4925.2  951.52    4946  944.65  4966.8  944.98  4992.7  943.24  4995.4  942.74
  4998.7  943.24  5024.6  944.13    5039  949.02  5074.3  953.19  5144.8  953.67
  5159.2  954.73  5194.5  960.76  5223.3  965.86  5230.8  968.39  5294.5  973.55
  5482.8  978.76  5767.9  989.71  5818.2  991.93  5954.2  995.92  6042.7  998.58
#Mann= 9 ,-1 , 0
  3964.5      .1       0  4211.8     .16       0    4589     .05       0
  4859.6     .16       0  4992.7     .07       0  4998.7     .16       0
  5767.9      .1       0  5818.2     .16       0  5954.2      .1       0
#XS Ineff= 2 , 0
         4665.91  964.88
Permanent Ineff=
       T       T
Bank Sta=4803.2,5194.5
XS Rating Curve= 0 ,0
Exp/Cntr=0.3,0.1