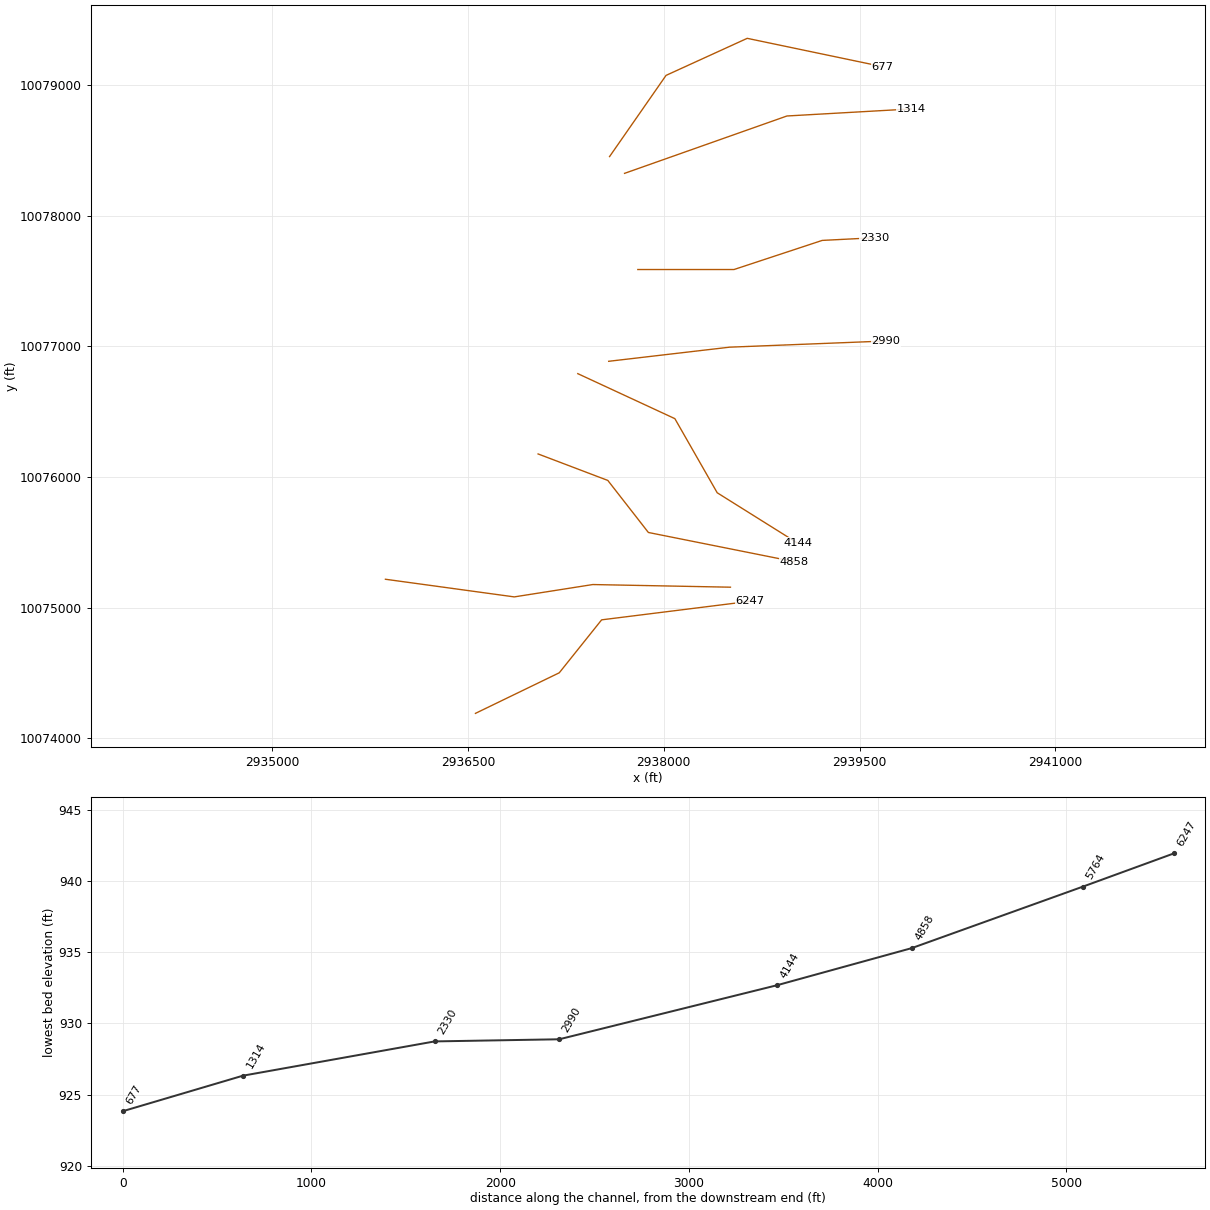
HEC-RAS study MILLER CREEK.prj: MILLER CREEK Base Level Engineering

--- MILLER CREEK.g01 (geometry) --- (continued)

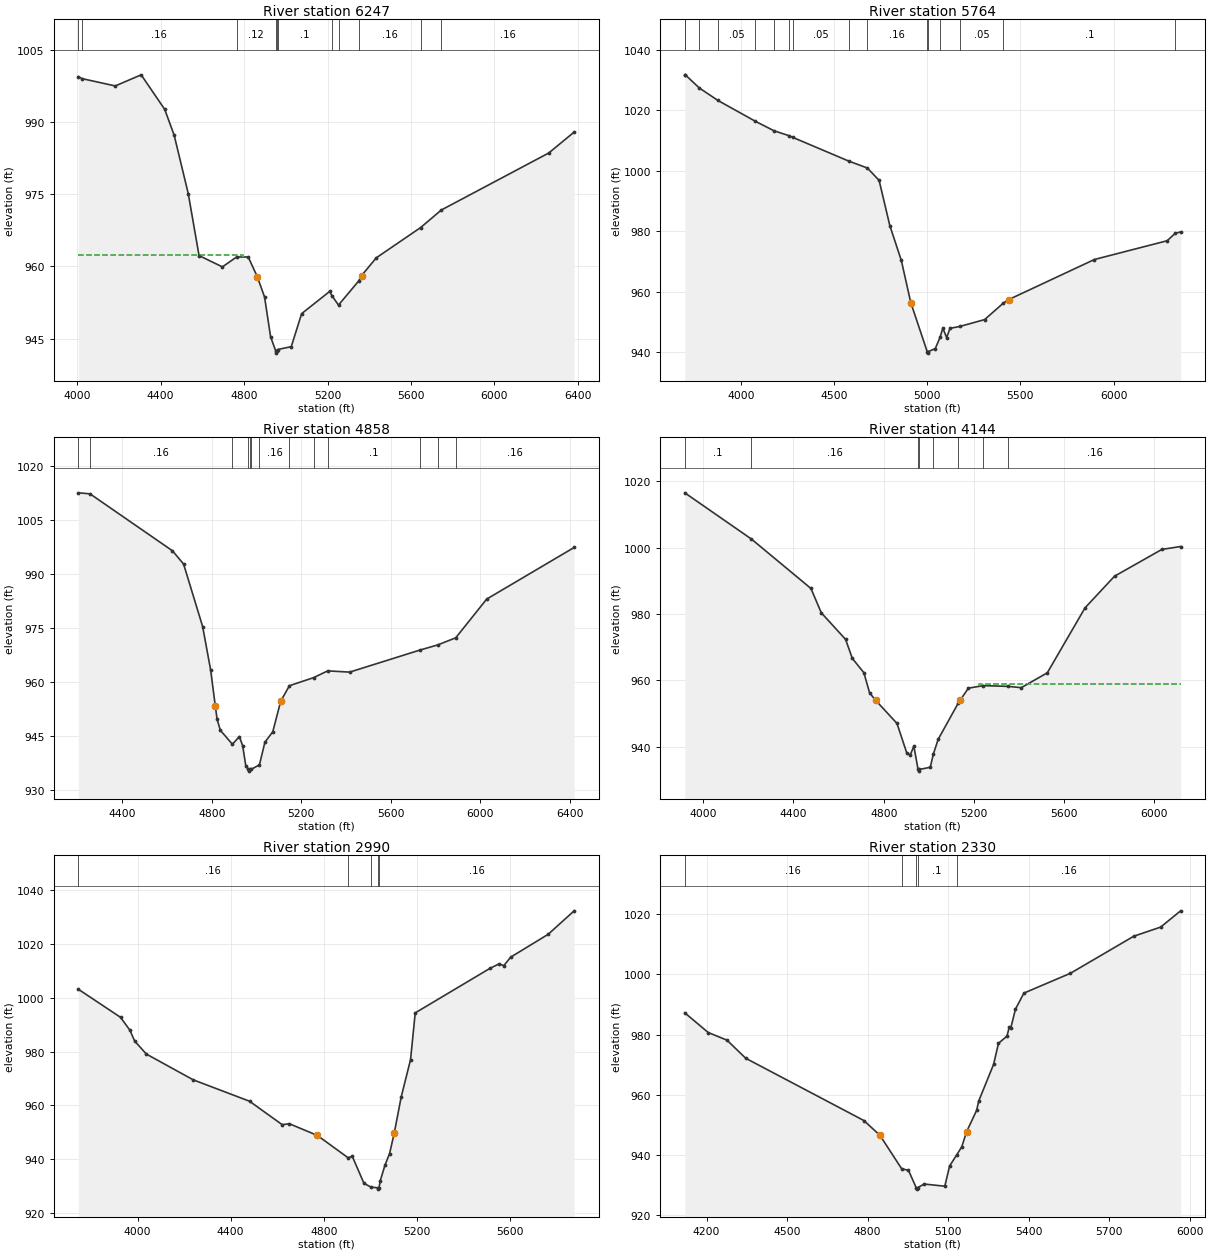
Type RM Length L Ch R = 1 ,6247    ,483,483,483
BEGIN DESCRIPTION:
MILLER CREEK 9.0
END DESCRIPTION:
XS GIS Cut Line= 4
      2936557.59     10074189.78       2937199.7     10074500.69
      2937524.14     10074906.24      2938659.63     10075048.17
#Sta/Elev= 30
  4005.3  999.45  4023.1  999.03  4182.5  997.51  4306.5  999.82  4419.4  992.64
  4464.6  987.29  4532.3  975.12    4584  962.24    4696  959.89  4763.8  961.94
  4819.7  961.95  4862.9  957.88  4898.2  953.62    4927  945.36  4951.2  942.46
  4953.9  941.96  4957.2  942.46  4960.5   942.7  5026.2  943.31  5075.9  950.17
  5210.3  954.79  5221.2   953.9  5252.6  951.95  5349.7  956.98  5363.4  958.09
  5433.9  961.78  5646.5  968.07  5745.4  971.71  6260.3  983.56  6382.4  987.92
#Mann= 11 ,-1 , 0
  4005.3      .1       0  4023.1     .16       0  4763.8     .12       0
  4951.2     .07       0  4957.2     .12       0  4960.5      .1       0
  5221.2     .05       0  5252.6      .1       0  5349.7     .16       0
  5646.5      .1       0  5745.4     .16       0
#XS Ineff= 2 , 0
         4795.45  962.38
Permanent Ineff=
       T       T
Bank Sta=4862.9,5363.4
XS Rating Curve= 0 ,0
Exp/Cntr=0.3,0.1

Type RM Length L Ch R = 1 ,5764    ,906,906,906
BEGIN DESCRIPTION:
MILLER CREEK 8.0
END DESCRIPTION:
XS GIS Cut Line= 4
      2935868.17     10075217.15      2936854.99     10075081.97
      2937456.54      10075176.6      2938510.96     10075156.32
#Sta/Elev= 30
  3700.1  1031.8  3703.1 1031.78  3777.9 1027.45  3878.1  1023.3  4078.5 1016.42
  4178.6 1013.27  4256.4  1011.7  4277.9 1011.12  4579.4 1003.23  4679.5 1000.93
  4742.4  996.84  4799.9  981.85  4861.6  970.31  4912.2  956.37  5000.3  940.12
  5003.1  939.62  5006.3  940.12  5043.8  941.15  5069.8  944.92  5084.3  947.91
  5104.6  944.76  5122.8  947.84  5175.8  948.46  5308.5  950.73    5409   956.2
    5437  957.34  5897.1  970.63  6287.2  976.84  6330.4  979.28  6359.7  979.78
#Mann= 16 ,-1 , 0
  3700.1      .1       0  3703.1     .05       0  3777.9      .1       0
  3878.1     .05       0  4078.5      .1       0  4178.6     .05       0
  4256.4      .1       0  4277.9     .05       0  4579.4      .1       0
  4679.5     .16       0  5000.3     .07       0  5006.3     .16       0
  5069.8      .1       0  5175.8     .05       0    5409      .1       0
  6330.4     .16       0
Bank Sta=4912.2,5437
XS Rating Curve= 0 ,0
Exp/Cntr=0.3,0.1

Type RM Length L Ch R = 1 ,4858    ,714,714,714
BEGIN DESCRIPTION:
MILLER CREEK 7.0
END DESCRIPTION:
XS GIS Cut Line= 4
      2937037.49     10076176.94      2937571.45     10075974.17
      2937882.37     10075575.38      2938997.65     10075352.33
#Sta/Elev= 30
  4204.4 1012.52  4256.6 1012.24  4624.9  996.43  4674.5  992.75  4759.5  975.42
  4795.1  963.42  4815.9  953.46  4824.1  949.69  4838.5  946.64  4892.4  942.76
  4923.6  944.89  4938.1  942.38  4952.5  936.69  4963.3   935.8  4966.1   935.3
  4969.3   935.8  4977.3  935.84  5013.1  937.03  5037.6  943.32  5072.8  946.23
  5108.1   954.7  5147.1     959  5254.6  961.23  5318.2  963.12    5416  962.77
  5730.3   968.9    5810  970.33  5889.9   972.3  6027.9  983.03  6418.6  997.36
#Mann= 13 ,-1 , 0
  4204.4      .1       0  4256.6     .16       0  4892.4     .05       0
  4963.3     .07       0  4969.3     .05       0  4977.3      .1       0
  5013.1     .16       0  5147.1      .1       0  5254.6     .05       0
  5318.2      .1       0  5730.3     .16       0    5810      .1       0
  5889.9     .16       0
Bank Sta=4815.9,5108.1
XS Rating Curve= 0 ,0
Exp/Cntr=0.3,0.1

Type RM Length L Ch R = 1 ,4144    ,1154,1154,1154
BEGIN DESCRIPTION:
MILLER CREEK 6.0
END DESCRIPTION:
XS GIS Cut Line= 4
      2937341.65     10076792.01      2938085.14      10076447.3
      2938409.57     10075879.54      2939024.05     10075494.65
#Sta/Elev= 30
  3918.1 1016.52  4213.6 1002.59  4477.5  987.71  4523.3  980.38  4631.1  972.37
  4660.8  966.66  4712.1  962.34  4737.6  956.26  4764.8  953.98  4858.9  947.07
    4903  938.02  4917.9  937.56  4933.8  940.23  4952.4  933.19  4955.1  932.69
  4958.4  933.19  5006.6  933.86  5020.4  937.86  5041.8   942.3    5131  953.23
  5138.2  953.97  5175.6  957.68  5241.6  958.44  5352.2  958.22  5409.9  957.83
  5525.4   962.3  5692.8  981.88  5823.6  991.41  6033.4  999.47  6116.6 1000.35
#Mann= 8 ,-1 , 0
  3918.1      .1       0  4213.6     .16       0  4952.4     .07       0
  4958.4     .16       0  5020.4     .05       0    5131      .1       0
  5241.6     .05       0  5352.2     .16       0
#XS Ineff= 2 , 0
                          5223.3          958.92
Permanent Ineff=
       T       T
Bank Sta=4764.8,5138.2
XS Rating Curve= 0 ,0
Exp/Cntr=0.3,0.1

Type RM Length L Ch R = 1 ,2990    ,660,660,660
BEGIN DESCRIPTION:
MILLER CREEK 4.0
END DESCRIPTION:
XS GIS Cut Line= 3
      2937578.26     10076886.64       2938504.2     10076994.78
      2939700.53      10077042.1
#Sta/Elev= 30
  3745.8  1003.2  3927.2  992.75  3967.5  987.94  3987.6  983.95    4038   979.1
  4239.3  969.52    4481  961.57  4621.4  952.85  4652.1   953.2  4772.4  948.85
  4904.3  940.56  4922.5  941.06  4972.5  931.04  5002.9  929.63  5031.3  929.39
    5034  928.89  5037.3  929.39  5042.6  932.02  5062.6  937.76  5082.6  942.12
  5102.6  949.75  5132.7  963.25  5172.7  977.06  5192.7  994.41    5513 1010.93
    5553 1012.64    5573 1011.98    5603 1015.15  5763.2 1023.59  5875.3 1032.35
#Mann= 5 ,-1 , 0
  3745.8     .16       0  4904.3      .1       0  5002.9     .16       0
  5031.3     .07       0  5037.3     .16       0
Bank Sta=4772.4,5102.6
XS Rating Curve= 0 ,0
Exp/Cntr=0.3,0.1

Type RM Length L Ch R = 1 ,2330    ,1016,1016,1016
BEGIN DESCRIPTION:
MILLER CREEK 3.0
END DESCRIPTION:
XS GIS Cut Line= 4
      2937801.24     10077589.58      2938537.99     10077589.58
       2939213.9     10077812.63      2939612.67     10077832.91
#Sta/Elev= 30
  4118.8  987.24    4206  980.71    4276  978.17    4346  972.16    4786  951.51
    4846   946.6  4926.9  935.51  4952.3  934.98  4981.1  929.24  4983.8  928.74
  4987.1  929.24  5010.6  930.43  5087.7  929.71  5105.8  936.44  5131.8  940.06
  5150.9  942.77  5169.3  947.86  5206.3  954.86  5214.1  957.96  5269.8  970.19
  5287.8  977.13  5319.4   979.5  5328.1  982.55  5333.3  982.07    5351  988.44
  5382.6  993.79  5555.6 1000.35  5792.2 1012.67  5892.3  1015.7  5966.6 1021.09
#Mann= 5 ,-1 , 0
  4118.8     .16       0  4926.9      .1       0  4981.1     .07       0
  4987.1      .1       0  5131.8     .16       0
Bank Sta=4846,5169.3
XS Rating Curve= 0 ,0
Exp/Cntr=0.3,0.1

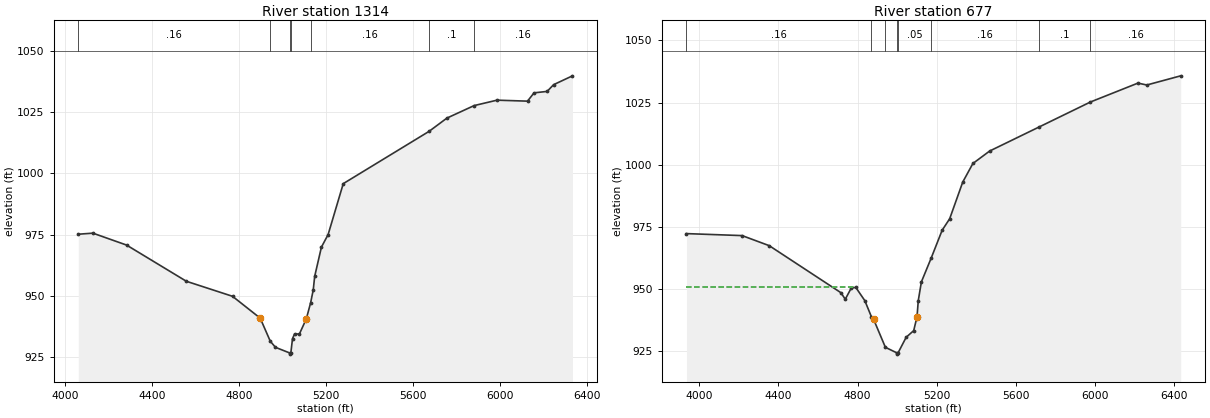
Type RM Length L Ch R = 1 ,1314    ,637,637,637
BEGIN DESCRIPTION:
MILLER CREEK 2.0
END DESCRIPTION:
XS GIS Cut Line= 3
      2937699.83      10078326.3      2938943.54     10078765.66
      2939894.98     10078819.64
#Sta/Elev= 30
  4061.7   975.2  4129.1  975.63  4283.7  970.78  4558.7  956.02  4770.8   949.9
  4898.1  940.99  4944.4   931.6  4968.3   929.1    5033  926.83  5035.7  926.33
    5039  926.83  5046.6  932.63  5055.8   934.5  5078.4  934.56  5110.2  940.73
    5130  947.29    5142  952.53  5148.6  958.04  5179.5  969.93  5210.4  975.08
  5279.9  995.81  5674.6 1017.13  5756.3 1022.52  5881.5 1027.62  5986.6 1029.83
  6126.9 1029.43  6156.9 1032.81    6217  1033.4    6247 1036.15  6333.7 1039.75
#Mann= 7 ,-1 , 0
  4061.7     .16       0  4944.4     .05       0    5033    .035       0
    5039     .05       0    5130     .16       0  5674.6      .1       0
  5881.5     .16       0
Bank Sta=4898.1,5110.2
XS Rating Curve= 0 ,0
Exp/Cntr=0.3,0.1

Type RM Length L Ch R = 1 ,677     ,0,0,0
BEGIN DESCRIPTION:
MILLER CREEK 1.0
END DESCRIPTION:
XS GIS Cut Line= 4
      2937584.96     10078454.74      2938017.55     10079076.57
      2938639.38     10079360.45      2939673.54     10079144.16
#Sta/Elev= 30
  3935.1   972.3  4216.4   971.5  4353.4  967.45  4715.6  948.54  4737.6   945.9
  4767.6  950.37  4790.6  950.68  4836.5  945.33  4869.6  938.88  4880.5  937.88
  4940.4  926.57  4998.4  924.33  5001.2  923.83  5004.4  924.33  5045.4  930.61
  5083.5  933.29  5100.3  938.89  5106.5  945.32  5122.3  952.89  5171.2  962.34
  5227.2  973.66  5265.2  978.27  5331.2  993.02  5382.5  1000.5  5467.2 1005.51
  5718.6 1015.24  5976.7 1025.24  6216.5 1032.83  6261.4 1032.07  6432.7 1035.76
#Mann= 8 ,-1 , 0
  3935.1     .16       0  4869.6      .1       0  4940.4     .05       0
  4998.4    .035       0  5004.4     .05       0  5171.2     .16       0
  5718.6      .1       0  5976.7     .16       0
#XS Ineff= 2 , 0
         4788.64  950.79
Permanent Ineff=
       T       T
Bank Sta=4880.5,5100.3
XS Rating Curve= 0 ,0
Exp/Cntr=0.3,0.1

Chan Stop Cuts=-1
Use User Specified Reach Order=0
Composite Channel Slope=5