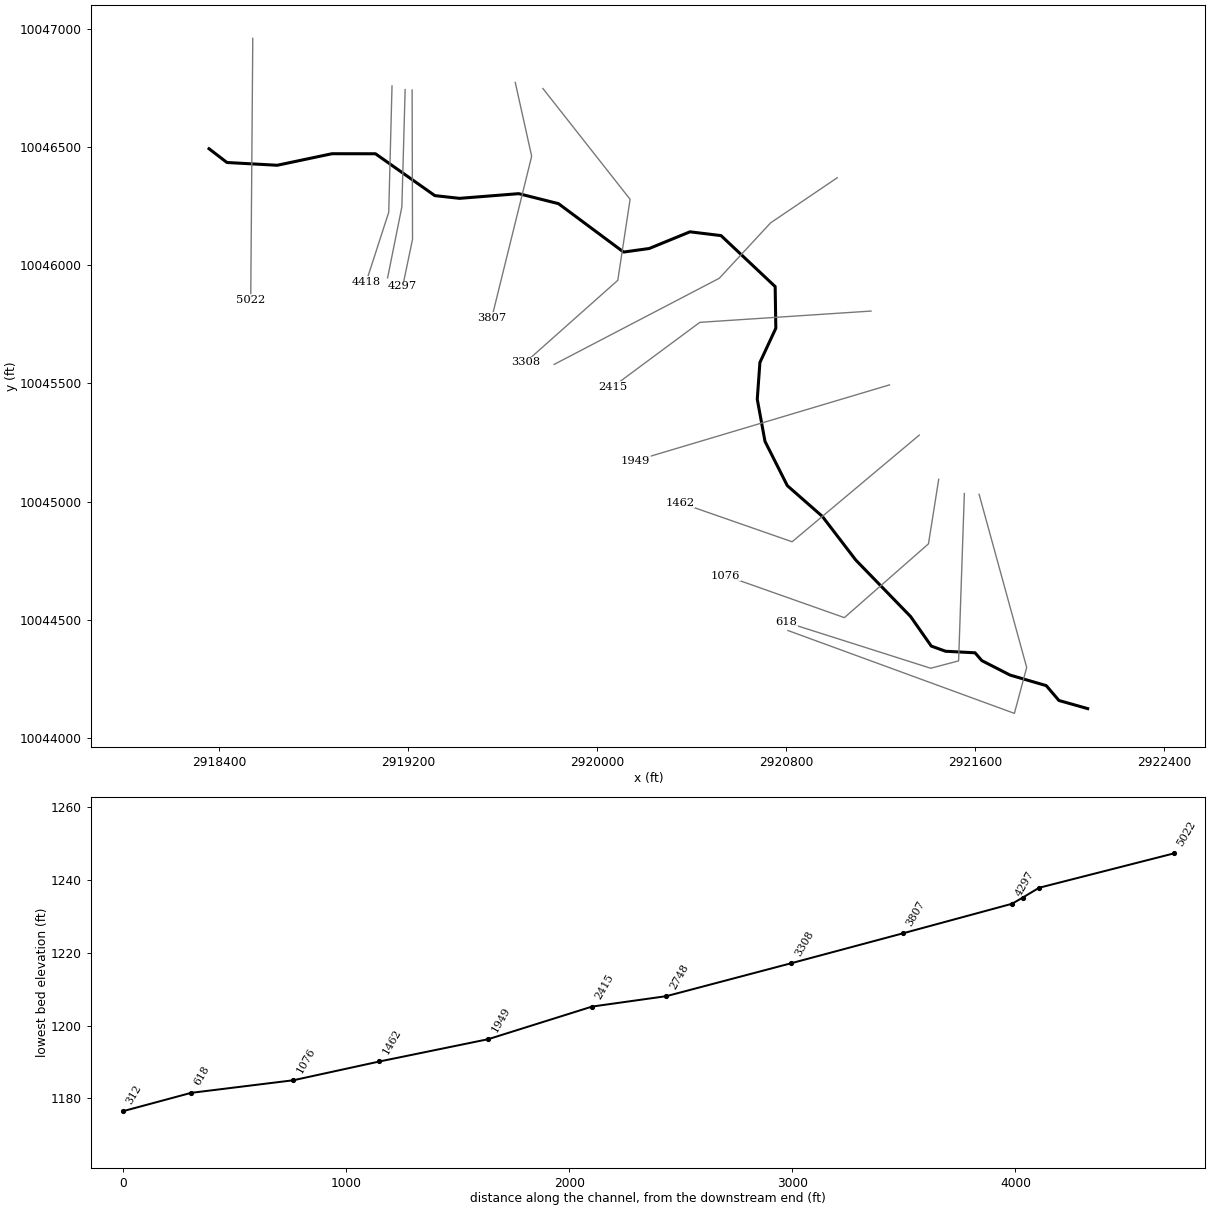
--- MILLSEAT BRANCH.prj (project) ---

Proj Title=MILLSEAT BRANCH Base Level Engineering
Current Plan=p01
Default Exp/Contr=0.3,0.1
English Units
Geom File=g01
Flow File=f01
Plan File=p01
Y Axis Title=Elevation
X Axis Title(PF)=Main Channel Distance
X Axis Title(XS)=Station
BEGIN DESCRIPTION:
MILLSEAT BRANCH
END DESCRIPTION:
DSS Export Rating Curves= 0
DSS Export Rating Curve Sorted= 0
DSS Export Volume Flow Curves= 0
DXF OffsetX= 0
DXF OffsetY= 0
DXF ScaleX= 1
DXF ScaleY= 10

--- MILLSEAT BRANCH.p01 (plan) ---

Plan Title=Multiple Run
Short Identifier=Multiple
Geom File=g01
Flow File=f01
Subcritical Flow
K Sum by GR= 0
Std Step Tol= 0.01
Critical Tol= 0.01
Num of Std Step Trials= 20
Max Error Tol= 0.3
Flow Tol Ratio= 0.001
Split Flow NTrial= 30
Split Flow Tol= 0.02
Split Flow Ratio= 0.02
Log Output Level= 0
Friction Slope Method= 1
Unsteady Friction Slope Method= 2
Unsteady Bridges Friction Slope Method= 1
Parabolic Critical Depth
Global Vel Dist=  1 , 1 , 1
Global Log Level= 0
CheckData=True
Encroach Param= -1, 0, 0, 0
BEGIN DESCRIPTION:
Multiple Run
END DESCRIPTION:

--- MILLSEAT BRANCH.f01 (steady flow) ---

Flow Title=Multiple
Program Version=4.10
Number of Profiles= 7
Profile Names=10-year,25-year,50-year,1pct_min,100-year,1pct_plu,500-year
River Rch & RM=MILLSEAT BRANCH,Reach-1         ,5022
     935    1362    1736    1621    2192    2965    3508
River Rch & RM=MILLSEAT BRANCH,Reach-1         ,2748
    1169    1723    2212    2079    2812    3803    4560
Boundary for River Rch & Prof#=MILLSEAT BRANCH,Reach-1         , 1
Up Type= 0
Dn Type= 3
Dn Slope=0.016
Boundary for River Rch & Prof#=MILLSEAT BRANCH,Reach-1         , 2
Up Type= 0
Dn Type= 3
Dn Slope=0.016
Boundary for River Rch & Prof#=MILLSEAT BRANCH,Reach-1         , 3
Up Type= 0
Dn Type= 3
Dn Slope=0.016
Boundary for River Rch & Prof#=MILLSEAT BRANCH,Reach-1         , 4
Up Type= 0
Dn Type= 3
Dn Slope=0.016
Boundary for River Rch & Prof#=MILLSEAT BRANCH,Reach-1         , 5
Up Type= 0
Dn Type= 3
Dn Slope=0.016
Boundary for River Rch & Prof#=MILLSEAT BRANCH,Reach-1         , 6
Up Type= 0
Dn Type= 3
Dn Slope=0.016
Boundary for River Rch & Prof#=MILLSEAT BRANCH,Reach-1         , 7
Up Type= 0
Dn Type= 3
Dn Slope=0.016
DSS Import GetInterval= 0
DSS Import GetPeak= 0
DSS Import FillOption= 0

--- MILLSEAT BRANCH.g01 (geometry) ---

Geom Title=Existing Conditions
Program Version=4.10

River Reach=MILLSEAT BRANCH ,Reach-1
Reach XY= 30
      2918358.21     10046493.63      2918433.99     10046435.39
      2918646.91     10046423.65       2918878.6     10046472.53
      2919062.79     10046472.36      2919314.08     10046295.19
      2919418.49     10046283.64      2919669.18     10046303.47
      2919837.41     10046261.18      2920113.06     10046056.27
      2920221.72     10046071.39        2920394.     10046141.96
      2920525.52     10046125.97      2920754.68     10045910.13
      2920757.49     10045733.84      2920690.09     10045588.77
      2920678.89     10045433.23      2920711.62     10045255.04
      2920806.12     10045067.42      2920954.14     10044937.57
      2921095.84     10044752.62      2921327.87     10044513.56
      2921415.54     10044388.35       2921476.1     10044366.44
      2921600.68     10044359.93      2921629.68     10044326.71
      2921749.22     10044265.56      2921902.22     10044220.96
      2921955.83     10044158.04      2922077.55     10044123.64

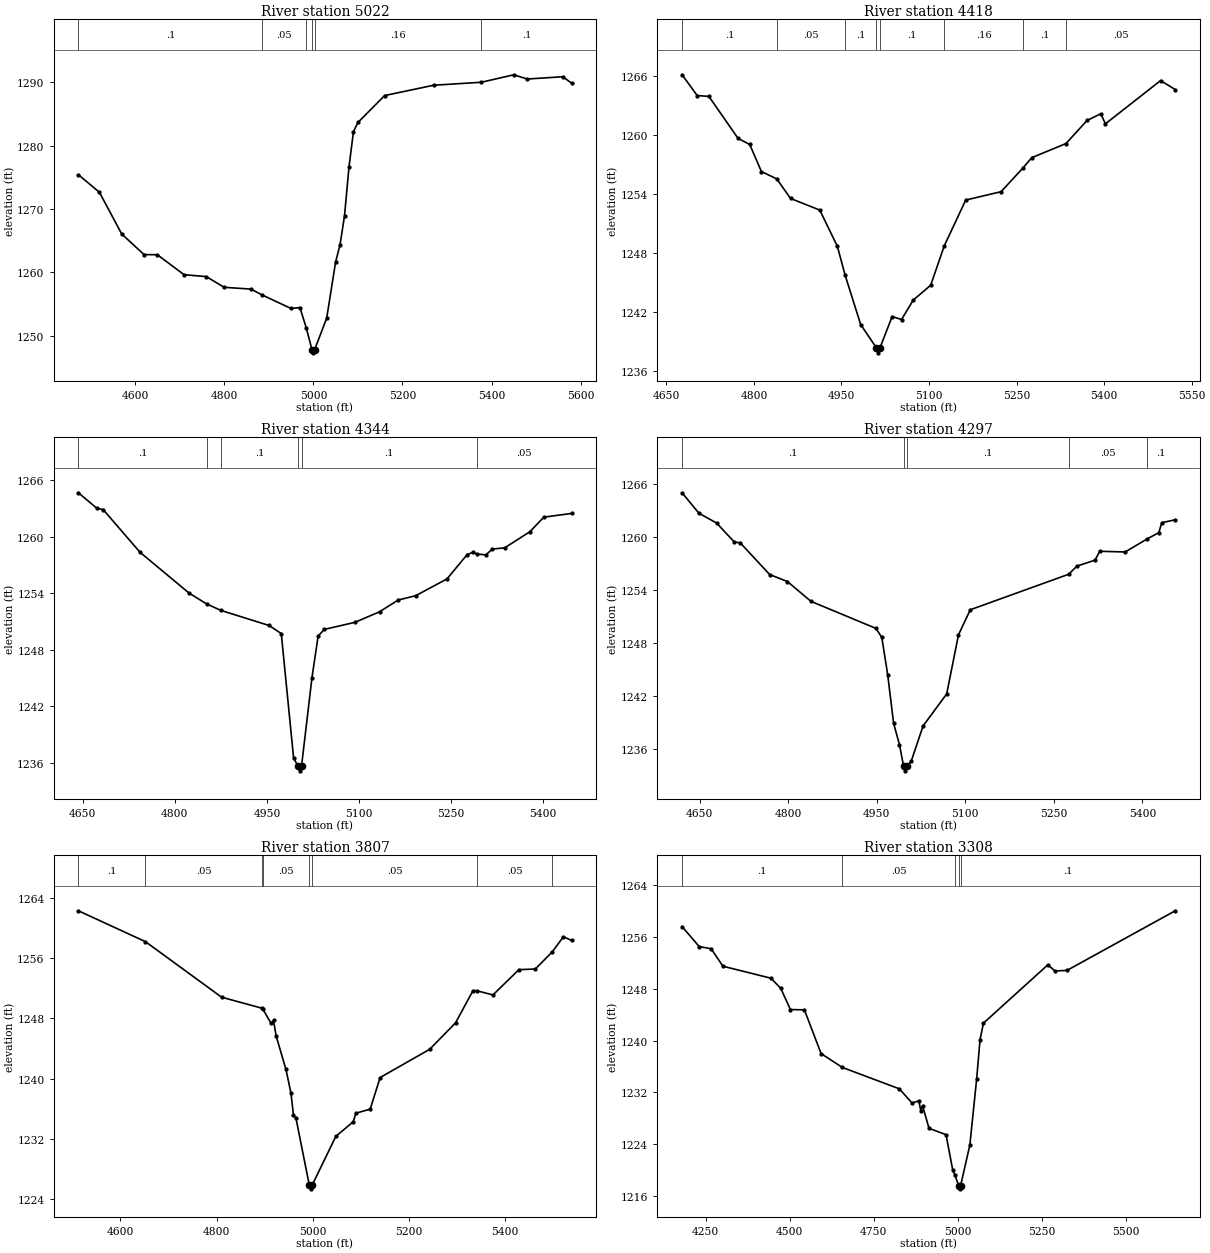
Type RM Length L Ch R = 1 ,5022    ,604,604,604
BEGIN DESCRIPTION:
MILLSEAT BRANCH 11.0
END DESCRIPTION:
XS GIS Cut Line= 2
      2918543.38     10046960.97       2918534.7      10045854.2
#Sta/Elev= 30
  4472.6 1275.41  4519.8 1272.64  4569.8 1266.06  4619.8 1262.81  4649.8 1262.78
  4709.8 1259.63  4759.8 1259.33  4799.8 1257.64  4859.8 1257.36  4885.7 1256.41
  4949.8  1254.3  4969.8 1254.44  4984.1 1251.23  4996.8  1247.8  4999.6  1247.3
  5002.8  1247.8  5029.9 1252.78  5049.9 1261.64  5059.9 1264.38  5069.9 1268.94
  5079.9 1276.61  5089.9 1282.18  5099.9 1283.65  5159.9  1287.9  5269.9 1289.53
    5377    1290  5449.9 1291.18  5479.9 1290.51  5559.9 1290.87  5579.4 1289.86
#Mann= 6 ,-1 , 0
  4472.6      .1       0  4885.7     .05       0  4984.1     .16       0
  4996.8     .07       0  5002.8     .16       0    5377      .1       0
Bank Sta=4996.8,5002.8
XS Rating Curve= 0 ,0
Exp/Cntr=0.3,0.1

Type RM Length L Ch R = 1 ,4418    ,74,74,74
BEGIN DESCRIPTION:
Mapping XS 017fcbb7
END DESCRIPTION:
XS GIS Cut Line= 3
      2919132.79      10046759.6       2919118.9      10046224.9
      2919023.43     10045929.83
#Sta/Elev= 30
  4676.9 1266.14  4702.8 1264.03  4722.8 1263.94  4772.8 1259.67  4792.8 1259.05
  4812.8  1256.3  4839.1 1255.55  4862.8 1253.56  4912.8 1252.38  4942.9  1248.7
  4956.3 1245.75  4982.9 1240.74  5009.9 1238.36  5012.6 1237.86  5015.9 1238.36
  5036.8 1241.55  5052.9 1241.25  5072.9 1243.22  5102.9 1244.74  5126.1 1248.74
  5162.9  1253.4  5223.5 1254.25  5260.6 1256.64  5276.1 1257.71  5334.8 1259.15
  5370.7 1261.49  5394.4 1262.18  5402.2 1261.15  5496.8 1265.55  5521.9 1264.64
#Mann= 8 ,-1 , 0
  4676.9      .1       0  4839.1     .05       0  4956.3      .1       0
  5009.9     .07       0  5015.9      .1       0  5126.1     .16       0
  5260.6      .1       0  5334.8     .05       0
Bank Sta=5009.9,5015.9
XS Rating Curve= 0 ,0
Exp/Cntr=0.3,0.1

Type RM Length L Ch R = 1 ,4344    ,47,47,47
BEGIN DESCRIPTION:
MILLSEAT BRANCH 10.0
END DESCRIPTION:
XS GIS Cut Line= 3
      2919188.34     10046743.98      2919174.45     10046247.47
      2919114.03     10045947.09
#Sta/Elev= 30
    4643 1264.65  4673.3 1262.99  4683.3 1262.87  4743.3 1258.34  4823.3    1254
  4851.7 1252.86  4875.3 1252.16  4953.4 1250.57  4973.4 1249.71  4993.4 1236.55
  5000.4 1235.64  5003.1 1235.14  5006.4 1235.64  5023.4 1245.03  5033.4 1249.44
  5043.4 1250.15  5093.4  1250.9  5133.4 1252.02  5163.9 1253.27  5192.4 1253.73
  5243.3 1255.51  5276.1 1258.09  5286.3 1258.35  5291.9 1258.15  5306.7 1258.06
  5316.9 1258.67  5337.3 1258.81  5378.1 1260.51  5400.9 1262.06  5446.1 1262.46
#Mann= 6 ,-1 , 0
    4643      .1       0  4851.7     .05       0  4875.3      .1       0
  5000.4     .07       0  5006.4      .1       0  5291.9     .05       0
Bank Sta=5000.4,5006.4
XS Rating Curve= 0 ,0
Exp/Cntr=0.3,0.1

Type RM Length L Ch R = 1 ,4297    ,490,490,490
BEGIN DESCRIPTION:
MILLSEAT BRANCH 9.0
END DESCRIPTION:
XS GIS Cut Line= 3
      2919217.86     10046742.22      2919219.59     10046110.32
      2919177.92     10045910.62
#Sta/Elev= 30
  4619.9 1264.99  4648.4 1262.67  4678.4 1261.56  4708.4 1259.41  4718.4 1259.32
  4768.4 1255.72  4798.4 1254.93  4838.4 1252.68  4948.4 1249.62  4958.4  1248.6
  4968.4 1244.37  4978.4 1238.86  4988.4 1236.43  4995.4 1233.97  4998.1 1233.47
  5001.4 1233.97  5008.4 1234.59  5028.4 1238.56  5068.4 1242.19  5088.4 1248.89
  5108.4 1251.73    5275 1255.75  5289.2 1256.68  5319.8 1257.35  5327.8 1258.36
  5370.9 1258.28  5408.2 1259.76  5427.9 1260.47    5433  1261.6  5455.8 1261.93
#Mann= 5 ,-1 , 0
  4619.9      .1       0  4995.4     .07       0  5001.4      .1       0
    5275     .05       0  5408.2      .1       0
Bank Sta=4995.4,5001.4
XS Rating Curve= 0 ,0
Exp/Cntr=0.3,0.1

Type RM Length L Ch R = 1 ,3807    ,499,499,499
BEGIN DESCRIPTION:
MILLSEAT BRANCH 8.0
END DESCRIPTION:
XS GIS Cut Line= 3
      2919654.49     10046774.38      2919723.93     10046461.88
      2919554.99     10045777.44
#Sta/Elev= 30
  4512.9  1262.3  4652.4 1258.19  4810.6 1250.81  4895.3 1249.33  4895.8 1249.29
  4913.4 1247.34  4918.5 1247.73  4923.8 1245.69  4944.4  1241.2  4954.7 1238.09
    4960 1235.15  4965.2 1234.71  4992.9 1225.83  4995.7 1225.33  4998.9 1225.83
  5048.1 1232.31  5084.4 1234.26  5089.6 1235.38  5119.5 1235.93  5140.1 1240.13
  5243.1 1243.88  5296.9  1247.4  5333.2 1251.69  5341.5 1251.66  5374.7 1251.11
  5428.5 1254.47  5462.7 1254.56  5497.8 1256.83  5521.2 1258.85    5538 1258.36
#Mann= 8 ,-1 , 0
  4512.9      .1       0  4652.4     .05       0  4895.3      .1       0
  4895.8     .05       0  4992.9     .07       0  4998.9     .05       0
  5341.5     .05       0  5497.8      .1       0
Bank Sta=4992.9,4998.9
XS Rating Curve= 0 ,0
Exp/Cntr=0.3,0.1

Type RM Length L Ch R = 1 ,3308    ,560,560,560
BEGIN DESCRIPTION:
MILLSEAT BRANCH 7.0
END DESCRIPTION:
XS GIS Cut Line= 4
      2919771.65     10046748.37       2920140.6     10046279.59
      2920088.52     10045936.71       2919697.9      10045589.5
#Sta/Elev= 30
    4180 1257.58  4230.9  1254.5  4266.2 1254.17  4301.5 1251.47  4444.2 1249.62
  4473.1 1248.07    4502 1244.79  4543.6 1244.74  4593.3 1237.99  4656.5 1235.86
    4826 1232.56  4863.4 1230.38  4883.6  1230.7  4889.7 1229.19  4894.7 1229.98
    4914 1226.48  4964.6 1225.49  4984.8 1219.97  4990.4 1219.35    5002 1217.64
  5004.8 1217.14    5008 1217.64  5035.4 1223.89  5055.6 1234.06  5065.7 1240.12
  5075.8 1242.69  5267.4 1251.69  5288.3 1250.74  5324.1 1250.82    5646 1260.02
#Mann= 5 ,-1 , 0
    4180      .1       0  4656.5     .05       0  4990.4      .1       0
    5002     .07       0    5008      .1       0
Bank Sta=5002,5008
XS Rating Curve= 0 ,0
Exp/Cntr=0.3,0.1

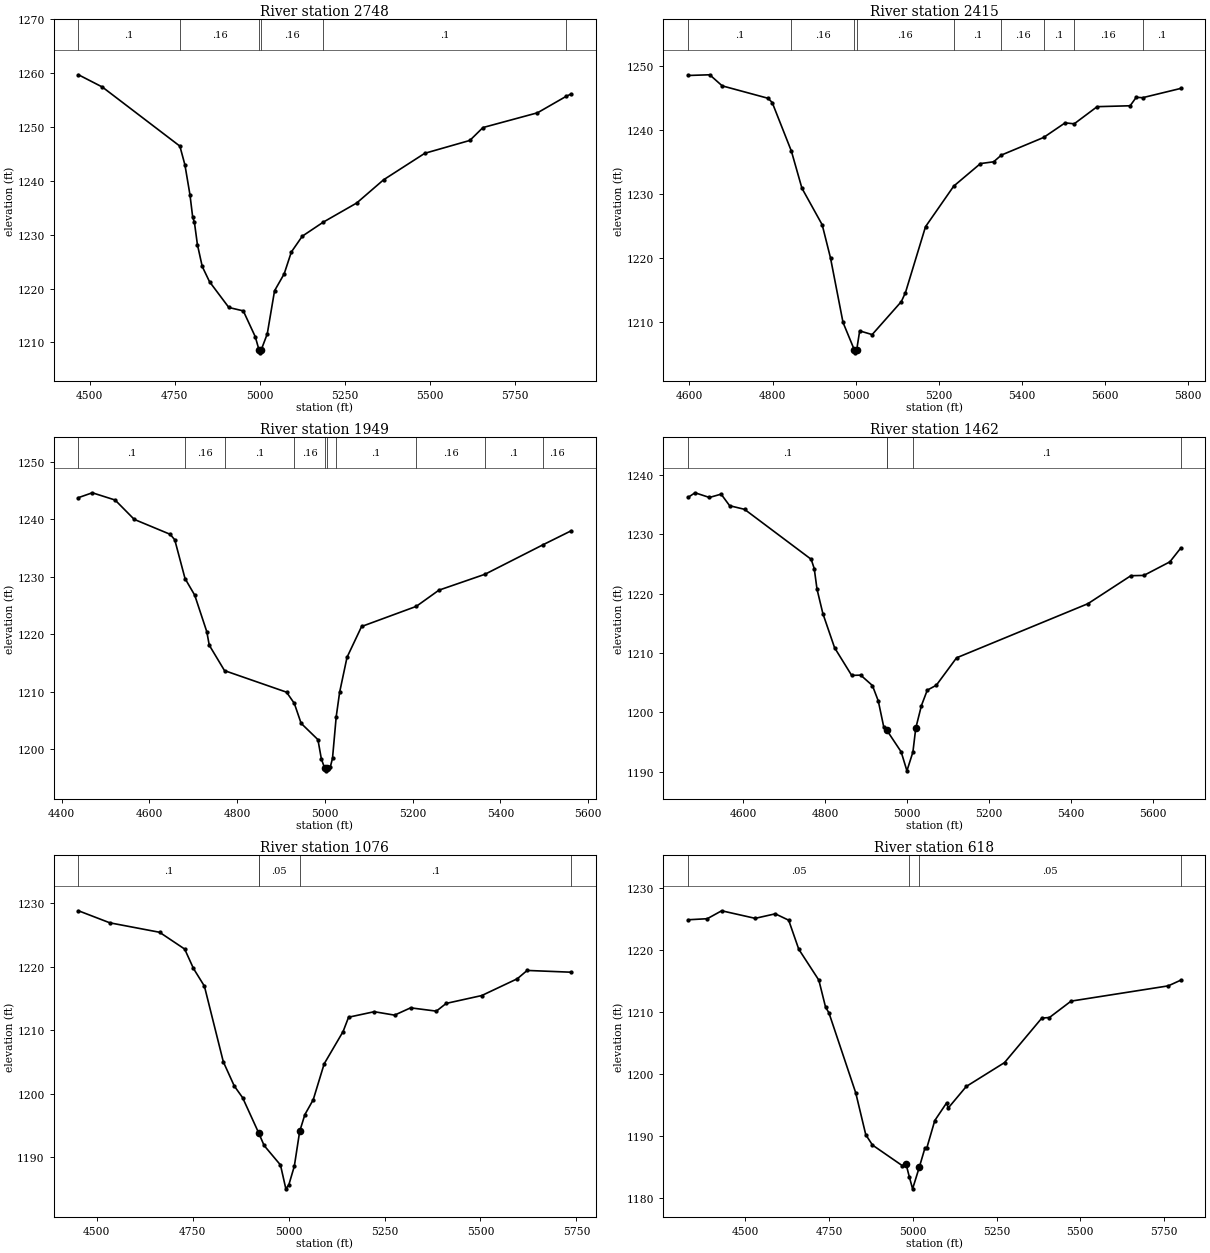
Type RM Length L Ch R = 1 ,2748    ,333,333,333
BEGIN DESCRIPTION:
MILLSEAT BRANCH 6.0
END DESCRIPTION:
XS GIS Cut Line= 4
      2921017.36     10046370.75      2920735.22     10046179.76
       2920518.2     10045945.39      2919819.41      10045580.8
#Sta/Elev= 30
  4466.9 1259.71  4536.9 1257.44  4764.9 1246.46  4779.7 1242.99  4794.6 1237.41
  4802.6 1233.24  4807.6 1232.33  4816.4 1228.19  4830.6 1224.12  4852.1 1221.28
  4908.8  1216.5  4951.3 1215.87  4986.5 1211.07  4997.7 1208.58  5000.4 1208.08
  5003.7 1208.58  5021.7 1211.59  5043.2 1219.61  5071.5 1222.75  5092.5  1226.8
  5124.7 1229.74  5186.7 1232.36  5284.6  1235.9  5363.6 1240.21  5484.7 1245.13
  5617.2 1247.52  5655.7 1249.91    5816 1252.65  5900.6 1255.72  5915.2 1256.15
#Mann= 6 ,-1 , 0
  4466.9      .1       0  4764.9     .16       0  4997.7     .07       0
  5003.7     .16       0  5186.7      .1       0  5900.6     .16       0
Bank Sta=4997.7,5003.7
XS Rating Curve= 0 ,0
Exp/Cntr=0.3,0.1

Type RM Length L Ch R = 1 ,2415    ,466,466,466
BEGIN DESCRIPTION:
MILLSEAT BRANCH 5.0
END DESCRIPTION:
XS GIS Cut Line= 3
      2921160.53      10045806.5      2920435.74     10045758.76
      2920066.79      10045485.3
#Sta/Elev= 30
  4596.6 1248.54  4648.8 1248.65  4678.8 1246.92  4789.1 1244.98  4799.1 1244.32
  4845.3 1236.72  4870.6 1230.94  4919.4 1225.22  4939.4 1220.04  4969.5 1209.97
  4996.5 1205.72  4999.3 1205.22  5002.5 1205.72  5009.6 1208.65  5039.6 1208.07
  5109.8 1213.22  5119.8 1214.64    5168 1224.92  5235.9 1231.26  5300.2 1234.78
    5332 1235.06  5350.6 1236.11  5452.2 1238.86  5503.9 1241.14  5525.8 1240.99
    5581 1243.67  5660.4 1243.81    5675 1245.13  5690.3 1245.07  5782.2 1246.52
#Mann= 9 ,-1 , 0
  4596.6      .1       0  4845.3     .16       0  4996.5     .07       0
  5002.5     .16       0  5235.9      .1       0  5350.6     .16       0
  5452.2      .1       0  5525.8     .16       0  5690.3      .1       0
Bank Sta=4996.5,5002.5
XS Rating Curve= 0 ,0
Exp/Cntr=0.3,0.1

Type RM Length L Ch R = 1 ,1949    ,487,487,487
BEGIN DESCRIPTION:
MILLSEAT BRANCH 4.0
END DESCRIPTION:
XS GIS Cut Line= 2
      2921238.65     10045493.99      2920162.92       10045173.
#Sta/Elev= 30
  4438.6  1243.8  4470.1 1244.64    4522 1243.38  4565.6 1240.01  4647.5 1237.41
  4657.9 1236.46  4681.3 1229.72  4703.4 1226.82    4731 1220.44  4736.5 1218.12
  4771.3 1213.69  4912.6 1209.94  4930.3 1207.99  4945.8 1204.52  4984.1 1201.68
  4991.9 1198.33  4999.3 1196.75  5002.1 1196.25  5005.3 1196.75  5012.1 1196.87
  5017.3 1198.42  5025.8  1205.7  5033.6 1209.95  5050.4 1216.01  5083.6 1221.37
  5208.1 1224.87  5259.7 1227.69  5364.7 1230.46  5497.6 1235.62  5561.2 1238.03
#Mann= 10 ,-1 , 0
  4438.6      .1       0  4681.3     .16       0  4771.3      .1       0
  4930.3     .16       0  4999.3     .07       0  5005.3     .16       0
  5025.8      .1       0  5208.1     .16       0  5364.7      .1       0
  5497.6     .16       0
Bank Sta=4999.3,5005.3
XS Rating Curve= 0 ,0
Exp/Cntr=0.3,0.1

Type RM Length L Ch R = 1 ,1462    ,386,386,386
BEGIN DESCRIPTION:
MILLSEAT BRANCH 3.0
END DESCRIPTION:
XS GIS Cut Line= 3
      2921364.57     10045281.34      2920826.36     10044829.94
      2920353.33     10044994.85
#Sta/Elev= 30
  4464.6 1236.22  4481.7    1237  4516.8 1236.21  4545.4 1236.77  4566.2 1234.82
  4602.6 1234.21  4765.3 1225.79  4772.8 1224.23  4779.6 1220.75  4793.9 1216.64
  4822.5 1210.88  4864.2 1206.22  4886.3 1206.26  4914.9 1204.51  4929.2 1201.92
  4942.4 1197.59    4950 1196.98  4985.1 1193.33  4999.2 1190.13  5013.8  1193.3
  5020.7  1197.3  5034.6 1201.13  5048.9 1203.73    5071 1204.56  5120.4 1209.18
  5441.1  1218.3  5546.1 1223.02  5577.8 1223.07  5641.4 1225.36    5668 1227.69
#Mann= 5 ,-1 , 0
  4464.6      .1       0    4950     .16       0    4950     .05       0
  5013.8      .1       0    5668     .16       0
Bank Sta=4950,5020.7
XS Rating Curve= 0 ,0
Exp/Cntr=0.3,0.1

Type RM Length L Ch R = 1 ,1076    ,458,458,458
BEGIN DESCRIPTION:
MILLSEAT BRANCH 2.0
END DESCRIPTION:
XS GIS Cut Line= 4
      2921447.02     10045094.66      2921403.62     10044821.26
      2921047.72     10044508.76      2920544.29     10044686.69
#Sta/Elev= 30
  4452.2 1228.83  4533.9 1226.93  4663.5 1225.44    4729 1222.79  4751.9 1219.73
  4780.4 1216.94  4829.7 1205.01  4858.2  1201.2    4880 1199.35  4922.2 1193.75
    4936 1191.81  4978.7 1188.73  4992.7 1184.97  5000.5 1185.61  5014.8 1188.54
  5028.7 1194.02  5042.3 1196.68  5064.1 1199.03  5092.6 1204.69  5141.9 1209.78
  5156.2 1212.04  5223.1 1212.91  5276.1 1212.37  5317.9 1213.52    5385    1213
  5410.7 1214.22  5503.4 1215.46  5596.1 1218.11  5621.7 1219.42  5736.6 1219.14
#Mann= 5 ,-1 , 0
  4452.2      .1       0  4922.2     .16       0  4922.2     .05       0
  5028.7      .1       0  5736.6     .16       0
Bank Sta=4922.2,5028.7
XS Rating Curve= 0 ,0
Exp/Cntr=0.3,0.1

Type RM Length L Ch R = 1 ,618     ,306,306,306
BEGIN DESCRIPTION:
Mapping XS 57ffb882
END DESCRIPTION:
XS GIS Cut Line= 4
       2921555.5      10045034.1       2921531.2     10044325.72
      2921413.14     10044294.47        2920803.      10044488.6
#Sta/Elev= 30
    4329  1224.9  4386.4 1225.07  4429.4 1226.35  4529.5 1225.13  4589.5 1225.86
  4629.5 1224.83  4659.6 1220.15  4719.6 1215.16  4739.6 1210.81  4749.6  1209.9
  4829.7 1196.99  4859.7 1190.23  4879.7 1188.57  4968.2 1185.27  4979.7 1185.56
  4989.8 1183.41  4999.5 1181.51  5019.8 1185.05  5036.3 1188.08  5041.8 1188.08
  5065.8 1192.53  5100.8 1195.35    5106 1194.55  5159.8 1198.02    5274 1201.87
  5385.2 1209.04  5408.1 1209.14  5472.6 1211.78  5762.7 1214.24  5800.2 1215.16
#Mann= 4 ,-1 , 0
    4329     .05       0  4989.8    .035       0  5019.8     .05       0
  5800.2      .1       0
Bank Sta=4979.7,5019.8
XS Rating Curve= 0 ,0
Exp/Cntr=0.3,0.1

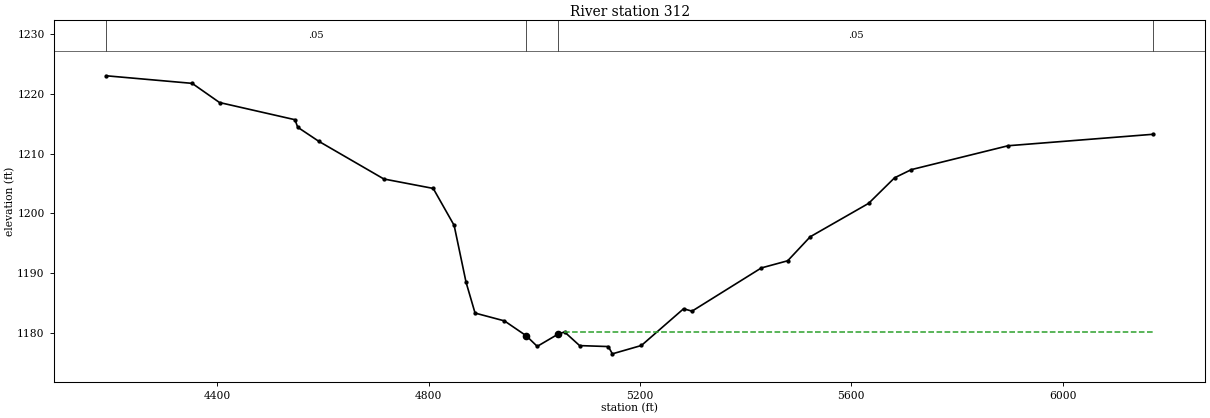
Type RM Length L Ch R = 1 ,312     ,0,0,0
BEGIN DESCRIPTION:
MILLSEAT BRANCH 1.0
END DESCRIPTION:
XS GIS Cut Line= 4
        2921618.     10045030.57      2921819.39     10044297.94
      2921767.31     10044103.49      2920808.96     10044454.19
#Sta/Elev= 30
  4189.7 1223.04  4352.4 1221.77  4404.2 1218.56    4547 1215.68  4552.2 1214.42
  4591.8 1212.08  4715.3 1205.75  4808.7 1204.17  4848.3 1197.98  4870.9 1188.44
  4887.9 1183.29  4943.5 1181.98  4984.9 1179.48  5005.6 1177.71  5045.8  1179.8
  5057.4 1180.12  5085.8 1177.84  5140.2 1177.68  5147.8 1176.46  5202.8 1177.86
  5282.6 1184.01  5298.6 1183.61  5429.8 1190.85  5479.7 1192.05  5522.3 1196.07
  5632.9 1201.67    5682 1205.95  5713.8 1207.32  5896.9 1211.32  6171.3 1213.24
#Mann= 4 ,-1 , 0
  4189.7     .05       0  4984.9    .035       0  5045.8     .05       0
  6171.3     .05       0
#XS Ineff= 2 , 0
                         5056.82         1180.14
Permanent Ineff=
       T       T
Bank Sta=4984.9,5045.8
XS Rating Curve= 0 ,0
Exp/Cntr=0.3,0.1

Chan Stop Cuts=-1
Use User Specified Reach Order=0
Composite Channel Slope=5