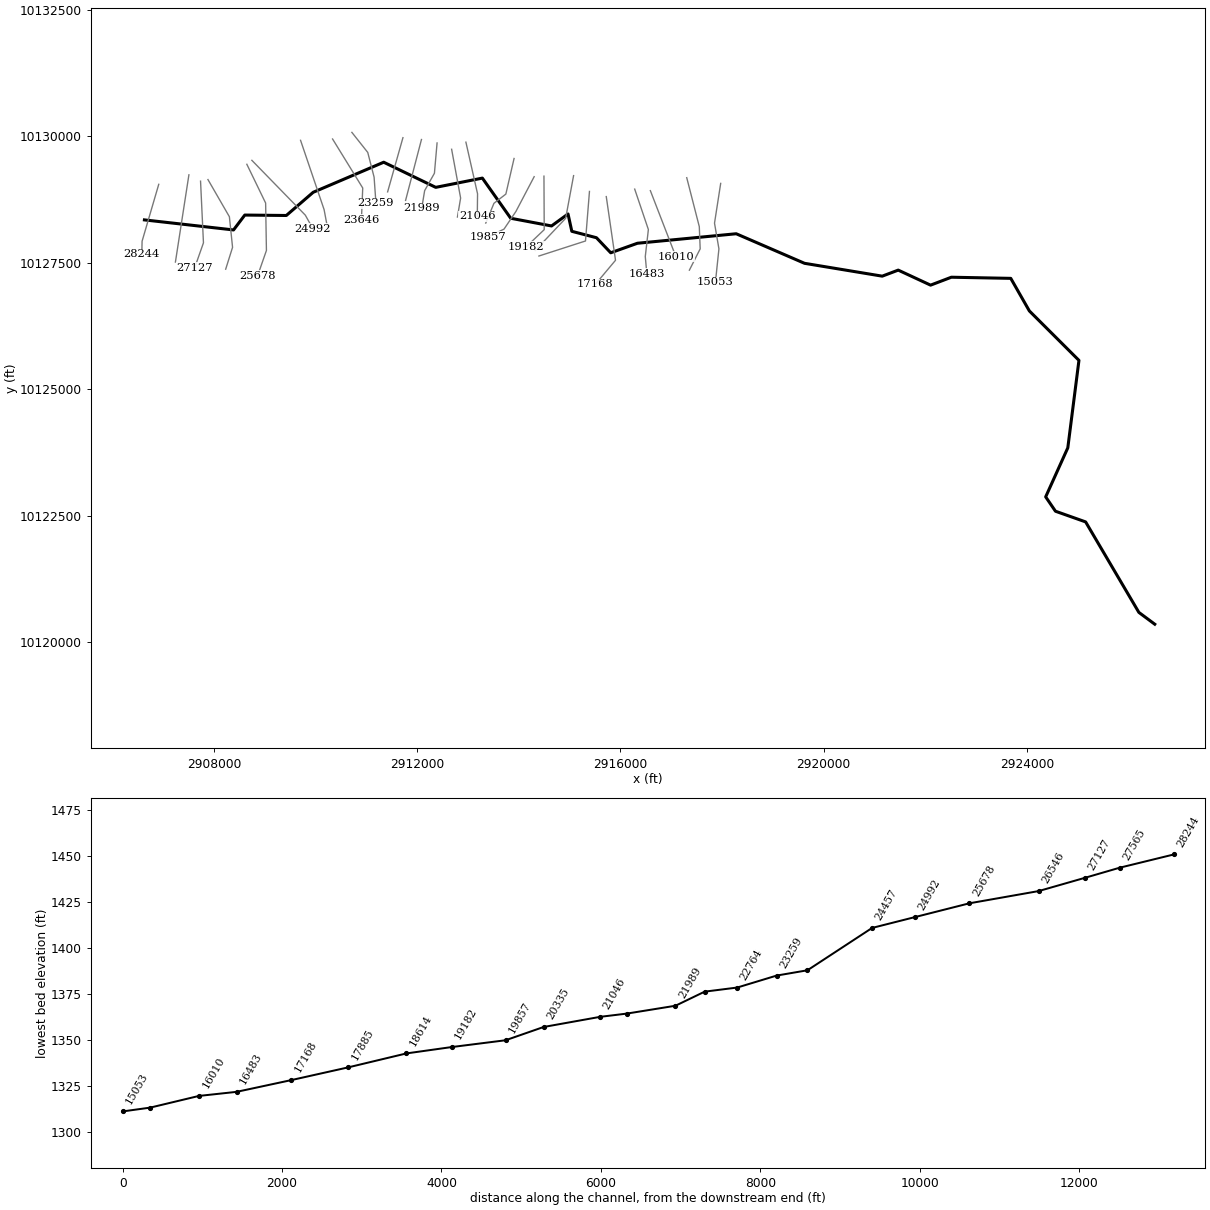
--- NORTH CYPRESS CREEK.prj (project) ---

Proj Title=NORTH CYPRESS CREEK Base Level Engineering
Current Plan=p01
Default Exp/Contr=0.3,0.1
English Units
Geom File=g01
Flow File=f01
Plan File=p01
Y Axis Title=Elevation
X Axis Title(PF)=Main Channel Distance
X Axis Title(XS)=Station
BEGIN DESCRIPTION:
NORTH CYPRESS CREEK
END DESCRIPTION:
DSS Export Rating Curves= 0
DSS Export Rating Curve Sorted= 0
DSS Export Volume Flow Curves= 0
DXF OffsetX= 0
DXF OffsetY= 0
DXF ScaleX= 1
DXF ScaleY= 10

--- NORTH CYPRESS CREEK.p01 (plan) ---

Plan Title=Multiple Run
Short Identifier=Multiple
Geom File=g01
Flow File=f01
Subcritical Flow
K Sum by GR= 0
Std Step Tol= 0.01
Critical Tol= 0.01
Num of Std Step Trials= 20
Max Error Tol= 0.3
Flow Tol Ratio= 0.001
Split Flow NTrial= 30
Split Flow Tol= 0.02
Split Flow Ratio= 0.02
Log Output Level= 0
Friction Slope Method= 1
Unsteady Friction Slope Method= 2
Unsteady Bridges Friction Slope Method= 1
Parabolic Critical Depth
Global Vel Dist=  1 , 1 , 1
Global Log Level= 0
CheckData=True
Encroach Param= -1, 0, 0, 0
BEGIN DESCRIPTION:
Multiple Run
END DESCRIPTION:

--- NORTH CYPRESS CREEK.f01 (steady flow) ---

Flow Title=Multiple
Program Version=4.10
Number of Profiles= 7
Profile Names=10-year,25-year,50-year,1pct_min,100-year,1pct_plu,500-year
River Rch & RM=NORTH CYPRESS CR,Reach-1         ,28244
    1361    2030    2627    2485    3361    4545    5526
River Rch & RM=NORTH CYPRESS CR,Reach-1         ,23646
    1637    2458    3193    3030    4098    5542    6781
River Rch & RM=NORTH CYPRESS CR,Reach-1         ,17168
    2439    3729    4904    4704    6362    8604   10766
River Rch & RM=NORTH CYPRESS CR,Reach-1         ,15053
    2609    3990    5247    5032    6805    9202   11505
River Rch & RM=NORTH CYPRESS CR,Reach-1         ,9628
    3164    4872    6436    6196    8379   11332   14280
River Rch & RM=NORTH CYPRESS CR,Reach-1         ,8753
    3164    4872    6436    6196    8379   11332   14280
River Rch & RM=NORTH CYPRESS CR,Reach-1         ,3796
    3455    5338    7068    6819    9222   12471   15780
Boundary for River Rch & Prof#=NORTH CYPRESS CR,Reach-1         , 1
Up Type= 0
Dn Type= 3
Dn Slope=0.01
Boundary for River Rch & Prof#=NORTH CYPRESS CR,Reach-1         , 2
Up Type= 0
Dn Type= 3
Dn Slope=0.01
Boundary for River Rch & Prof#=NORTH CYPRESS CR,Reach-1         , 3
Up Type= 0
Dn Type= 3
Dn Slope=0.01
Boundary for River Rch & Prof#=NORTH CYPRESS CR,Reach-1         , 4
Up Type= 0
Dn Type= 3
Dn Slope=0.01
Boundary for River Rch & Prof#=NORTH CYPRESS CR,Reach-1         , 5
Up Type= 0
Dn Type= 3
Dn Slope=0.01
Boundary for River Rch & Prof#=NORTH CYPRESS CR,Reach-1         , 6
Up Type= 0
Dn Type= 3
Dn Slope=0.01
Boundary for River Rch & Prof#=NORTH CYPRESS CR,Reach-1         , 7
Up Type= 0
Dn Type= 3
Dn Slope=0.01
DSS Import GetInterval= 0
DSS Import GetPeak= 0
DSS Import FillOption= 0

--- NORTH CYPRESS CREEK.g01 (geometry) ---

Geom Title=Existing Conditions
Program Version=4.10

River Reach=NORTH CYPRESS CR,Reach-1
Reach XY= 30
      2906628.47     10128343.73      2908382.92     10128145.17
      2908604.48      10128439.3      2909421.92     10128430.93
      2909951.09     10128889.39      2911339.18     10129483.48
      2912363.41     10128986.82      2913281.24     10129169.68
      2913839.42      10128376.1      2914643.51     10128224.04
      2914967.56     10128461.17      2915042.39     10128118.31
      2915527.56     10127991.27      2915808.47     10127693.73
      2916333.72     10127882.11      2918278.31     10128069.94
      2919623.76     10127485.78      2921153.39     10127231.92
      2921468.06     10127351.27      2922105.16     10127054.36
      2922513.98     10127210.91      2923683.81     10127188.36
      2924049.49     10126544.94      2925025.85     10125567.57
      2924806.54     10123839.67      2924370.84     10122870.15
      2924563.61     10122586.67      2925157.39     10122375.47
      2926205.51     10120587.13      2926518.47     10120353.73

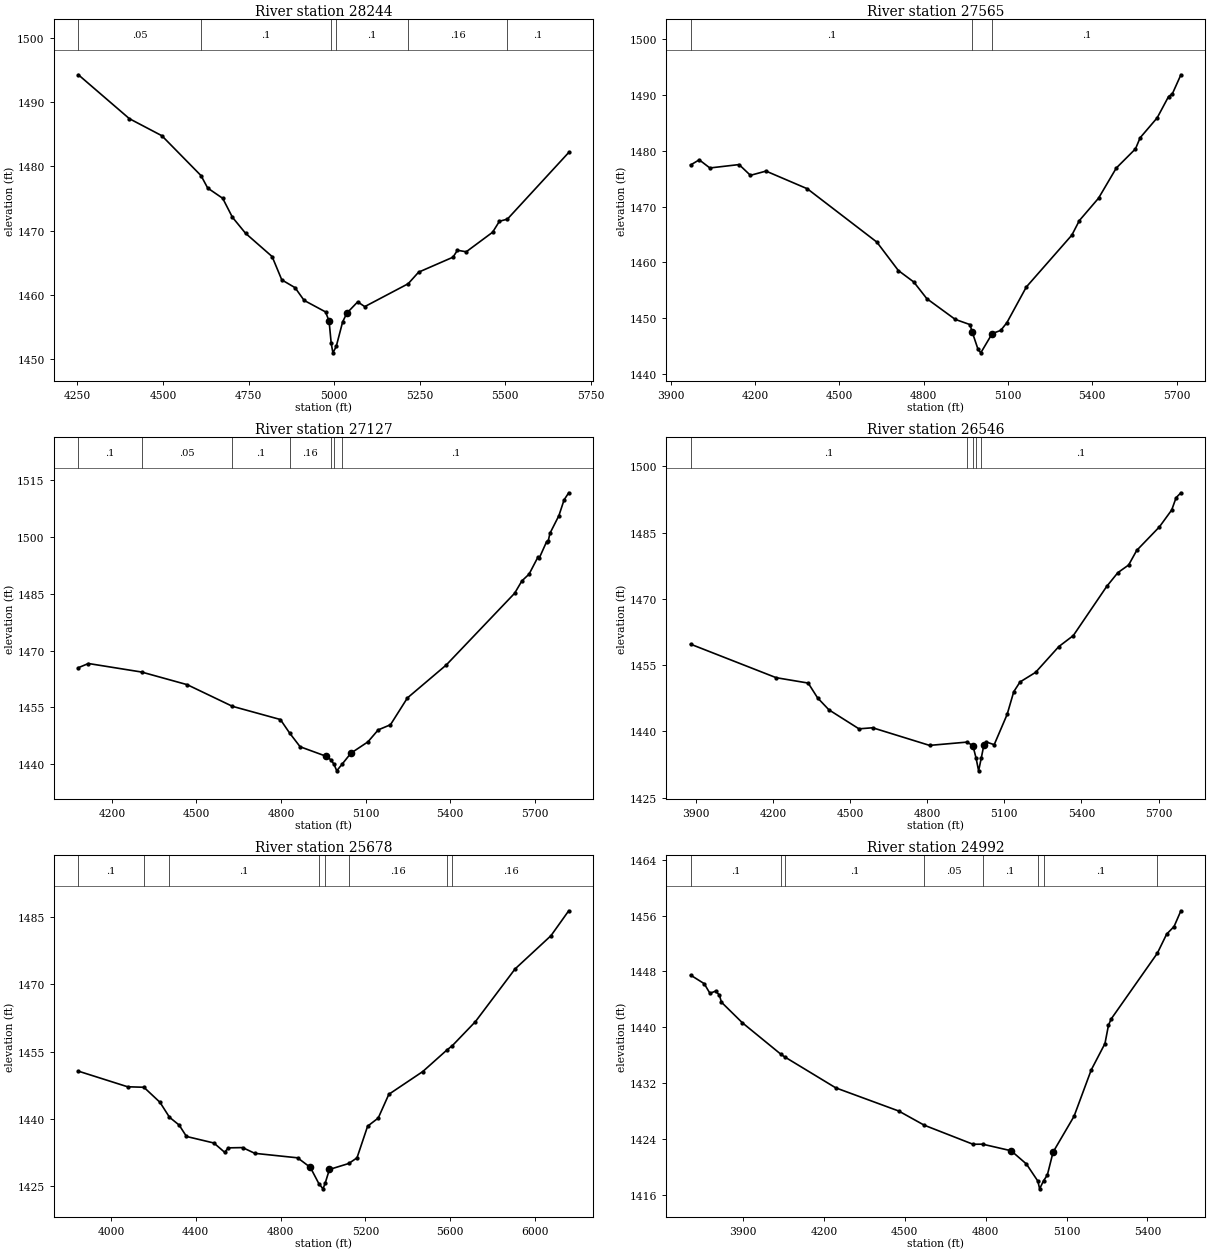
Type RM Length L Ch R = 1 ,28244   ,679,679,679
BEGIN DESCRIPTION:
NORTH CYPRESS CREEK 56.0
END DESCRIPTION:
XS GIS Cut Line= 3
      2906910.54     10129046.76      2906582.42     10127921.77
      2906577.21     10127661.39
#Sta/Elev= 30
  4252.9 1494.25  4401.9 1487.42  4496.7 1484.77  4611.2 1478.56  4630.6 1476.63
  4674.5 1475.03  4702.8 1472.09  4741.4 1469.58  4818.8 1465.97  4847.1 1462.34
  4885.8 1461.13  4912.3 1459.15  4974.8 1457.36  4985.2 1455.94  4991.4 1452.48
  4996.4 1450.99  5006.1 1451.98  5024.9 1455.82  5037.3 1457.18  5068.8 1458.92
  5089.4 1458.18  5216.2 1461.74  5246.7 1463.54  5347.1 1465.87  5360.2 1466.95
  5385.8 1466.71  5462.8 1469.75  5482.8 1471.46    5506 1471.79  5685.2 1482.16
#Mann= 6 ,-1 , 0
  4252.9     .05       0  4611.2      .1       0  4991.4     .07       0
  5006.1      .1       0  5216.2     .16       0    5506      .1       0
Bank Sta=4985.2,5037.3
XS Rating Curve= 0 ,0
Exp/Cntr=0.3,0.1

Type RM Length L Ch R = 1 ,27565   ,438,438,438
BEGIN DESCRIPTION:
NORTH CYPRESS CREEK 55.0
END DESCRIPTION:
XS GIS Cut Line= 2
       2907504.3     10129234.29      2907238.67     10127510.34
#Sta/Elev= 30
  3971.2 1477.47  4002.1  1478.4  4039.9 1476.94  4143.8 1477.55  4184.2 1475.62
  4239.6 1476.38  4386.6 1473.21  4633.9 1463.65  4710.4 1458.55  4765.4 1456.49
  4811.6 1453.51  4912.7 1449.79    4965 1448.86  4973.4 1447.49  4993.7 1444.44
  5003.6 1443.79  5044.3 1447.25  5074.6 1447.81  5096.5  1449.2  5165.7  1455.6
  5327.6  1464.9  5354.3 1467.51  5422.5 1471.52  5485.7 1476.93    5554 1480.37
  5570.4 1482.35  5631.1 1485.93  5671.6 1489.75  5685.4 1490.27  5715.5 1493.65
#Mann= 3 , 0 , 0
  3971.2      .1       0  4973.4     .07       0  5044.3      .1       0
Bank Sta=4973.4,5044.3
XS Rating Curve= 0 ,0
Exp/Cntr=0.3,0.1

Type RM Length L Ch R = 1 ,27127   ,581,581,581
BEGIN DESCRIPTION:
NORTH CYPRESS CREEK 54.0
END DESCRIPTION:
XS GIS Cut Line= 3
      2907733.46      10129109.3      2907790.75     10127890.52
      2907618.88     10127400.94
#Sta/Elev= 30
  4081.1 1465.51  4116.7 1466.61  4305.2 1464.36  4467.1 1461.02  4627.3 1455.31
  4797.5 1451.82  4830.3 1448.25  4867.5 1444.63  4957.6 1442.18  4976.1 1441.23
  4987.7 1440.01  4997.4 1438.27  5017.7 1440.15  5047.7 1442.94  5107.8 1445.91
  5144.4 1449.08  5187.9 1450.44    5248 1457.52  5385.8 1466.22  5628.4 1485.17
  5654.1 1488.43  5679.4  1490.2  5710.8 1494.69  5716.1 1494.53  5741.8  1498.8
  5747.1 1498.86  5753.5 1500.98  5785.3 1505.66  5803.7 1509.83  5820.1 1511.69
#Mann= 7 ,-1 , 0
  4081.1      .1       0  4305.2     .05       0  4627.3      .1       0
  4830.3     .16       0  4976.1      .1       0  4987.7     .07       0
  5017.7      .1       0
Bank Sta=4957.6,5047.7
XS Rating Curve= 0 ,0
Exp/Cntr=0.3,0.1

Type RM Length L Ch R = 1 ,26546   ,868,868,868
BEGIN DESCRIPTION:
NORTH CYPRESS CREEK 53.0
END DESCRIPTION:
XS GIS Cut Line= 4
       2907879.3     10129140.52      2908301.17     10128406.14
      2908363.67     10127801.98      2908228.26      10127369.7
#Sta/Elev= 30
  3879.8 1459.74  4212.8 1452.15  4337.4 1450.93  4373.9 1447.58  4418.1 1444.87
  4534.9 1440.57  4588.1 1440.81  4809.6 1436.82  4954.1 1437.56  4977.9 1436.79
  4990.5 1433.92  5000.3 1431.06  5010.6 1433.94  5020.7  1436.9  5030.7 1437.58
  5060.9 1436.98  5111.2 1443.83    5137 1448.98  5161.4 1451.18  5221.8 1453.35
  5312.2 1459.19  5368.6 1461.68  5498.4  1472.8  5541.9 1475.93  5583.8 1477.66
  5615.2 1480.96  5703.5 1486.29  5751.4 1490.12  5768.4  1492.9  5787.1 1494.01
#Mann= 5 ,-1 , 0
  3879.8      .1       0  4954.1     .16       0  4977.9      .1       0
  4990.5     .07       0  5010.6      .1       0
Bank Sta=4977.9,5020.7
XS Rating Curve= 0 ,0
Exp/Cntr=0.3,0.1

Type RM Length L Ch R = 1 ,25678   ,686,686,686
BEGIN DESCRIPTION:
NORTH CYPRESS CREEK 51.0
END DESCRIPTION:
XS GIS Cut Line= 4
       2908644.9     10129442.63      2909014.71     10128676.98
      2909030.34     10127739.48      2908858.47      10127244.7
#Sta/Elev= 30
  3846.6 1450.64  4078.7 1447.16  4155.5 1447.05  4231.3  1443.7  4276.1 1440.37
  4321.7 1438.63  4356.2 1436.09  4485.5 1434.63  4536.3 1432.56  4553.3 1433.55
  4621.1 1433.61  4678.3 1432.33  4880.2 1431.33  4940.2  1429.2  4980.2 1425.59
  4999.9 1424.42  5010.2 1425.69  5030.2 1428.74  5121.5 1430.07  5160.2 1431.33
  5210.2 1438.38  5260.2 1440.19  5310.2 1445.48  5470.2 1450.55  5584.7 1455.38
  5609.8 1456.33  5718.2 1461.66  5905.3 1473.41  6074.6 1480.82  6158.3 1486.37
#Mann= 8 ,-1 , 0
  3846.6      .1       0  4155.5     .16       0  4276.1      .1       0
  4980.2     .07       0  5010.2      .1       0  5121.5     .16       0
  5584.7      .1       0  5609.8     .16       0
Bank Sta=4940.2,5030.2
XS Rating Curve= 0 ,0
Exp/Cntr=0.3,0.1

Type RM Length L Ch R = 1 ,24992   ,535,535,535
BEGIN DESCRIPTION:
NORTH CYPRESS CREEK 49.0
END DESCRIPTION:
XS GIS Cut Line= 3
      2908743.86     10129520.75      2909795.96     10128437.39
      2909946.39     10128167.66
#Sta/Elev= 30
  3705.1 1447.48  3755.8 1446.25    3777 1444.87  3798.3 1445.19  3812.4  1444.6
  3819.4 1443.61  3897.1 1440.66  4039.9 1436.16    4054 1435.78  4243.8 1431.34
  4477.1 1428.03  4571.9    1426  4752.9 1423.27  4788.7 1423.28  4894.3 1422.34
  4950.9 1420.45  4993.4    1418  5000.1 1416.89  5014.5 1418.04  5028.6 1418.86
    5050 1422.15  5127.7 1427.27  5191.4  1433.9  5242.4 1437.68  5255.4 1440.29
  5265.3 1441.19  5436.6  1450.6  5471.3 1453.34  5498.8 1454.43  5524.1 1456.68
#Mann= 8 ,-1 , 0
  3705.1      .1       0  4039.9     .16       0    4054      .1       0
  4571.9     .05       0  4788.7      .1       0  4993.4     .07       0
  5014.5      .1       0  5436.6     .16       0
Bank Sta=4894.3,5050
XS Rating Curve= 0 ,0
Exp/Cntr=0.3,0.1

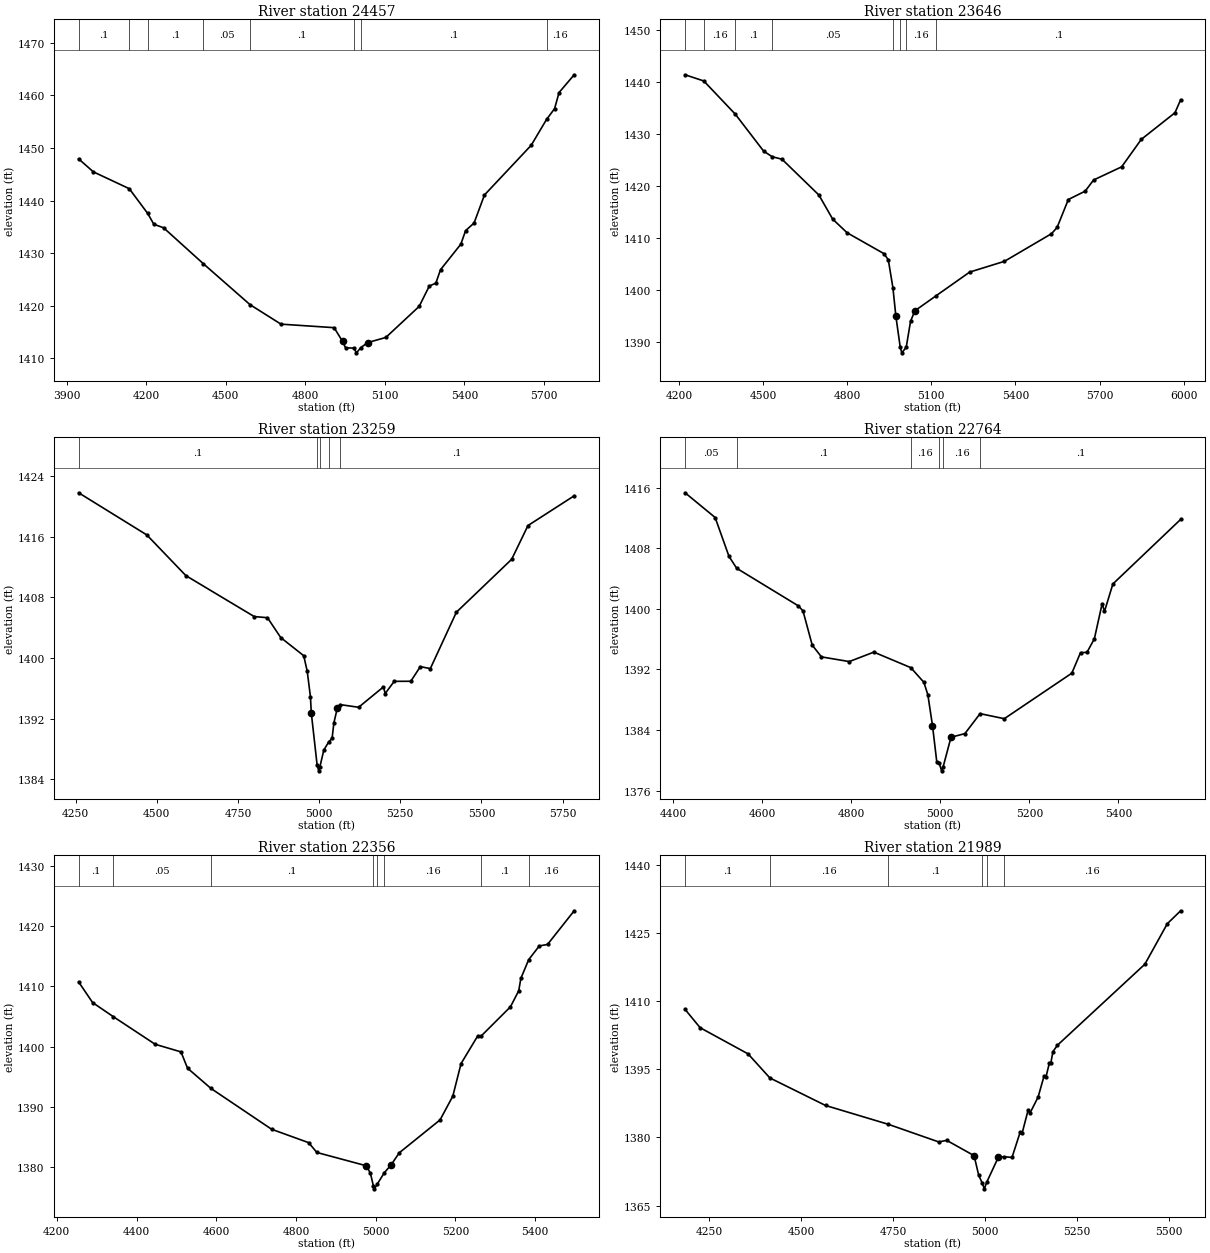
Type RM Length L Ch R = 1 ,24457   ,811,811,811
BEGIN DESCRIPTION:
NORTH CYPRESS CREEK 48.0
END DESCRIPTION:
XS GIS Cut Line= 3
      2909702.22     10129916.53      2910165.75     10128546.77
      2910243.68     10128131.17
#Sta/Elev= 30
  3945.1 1447.93  4000.8 1445.46  4136.1 1442.26  4205.6 1437.55  4228.8 1435.49
  4265.5 1434.82  4415.9 1427.96  4591.3  1420.2  4708.2 1416.48  4908.7 1415.81
  4940.4  1413.2  4951.8 1411.98  4983.2 1411.92    4993 1411.02  5009.4 1412.02
  5035.4 1412.97  5103.7 1413.95  5229.4 1419.86  5267.7 1423.74  5292.3 1424.28
  5309.9 1426.84  5386.6  1431.7  5404.4 1434.27  5436.5 1435.73  5475.6 1441.06
  5651.9 1450.52  5709.7 1455.43  5740.2  1457.5    5757 1460.56    5814 1463.94
#Mann= 8 ,-1 , 0
  3945.1      .1       0  4136.1     .16       0  4205.6      .1       0
  4415.9     .05       0  4591.3      .1       0  4983.2     .07       0
  5009.4      .1       0  5709.7     .16       0
Bank Sta=4940.4,5035.4
XS Rating Curve= 0 ,0
Exp/Cntr=0.3,0.1

Type RM Length L Ch R = 1 ,23646   ,387,387,387
BEGIN DESCRIPTION:
NORTH CYPRESS CREEK 46.0
END DESCRIPTION:
XS GIS Cut Line= 3
      2910332.43     10129942.58      2910926.17     10128973.85
      2910900.13      10128343.6
#Sta/Elev= 30
  4221.9 1441.38  4288.6 1440.19    4401 1433.81    4502 1426.72  4532.4 1425.65
  4567.4 1425.17  4698.9  1418.3  4748.3 1413.66  4799.6 1411.05    4931 1407.04
  4946.5 1405.86  4962.9 1400.51  4973.6 1394.99  4989.1 1389.04  4994.7    1388
  5010.4 1389.07  5025.8 1394.05  5041.2 1396.07    5117 1398.96  5236.6  1403.5
  5360.7 1405.57  5528.4 1410.87  5548.4 1412.07  5588.4 1417.43  5648.5 1419.04
  5678.5 1421.18  5778.6 1423.71  5848.6 1428.98  5968.7 1434.09  5988.9 1436.58
#Mann= 8 ,-1 , 0
  4221.9      .1       0  4288.6     .16       0    4401      .1       0
  4532.4     .05       0  4962.9     .16       0  4989.1     .07       0
  5010.4     .16       0    5117      .1       0
Bank Sta=4973.6,5041.2
XS Rating Curve= 0 ,0
Exp/Cntr=0.3,0.1

Type RM Length L Ch R = 1 ,23259   ,495,495,495
BEGIN DESCRIPTION:
NORTH CYPRESS CREEK 45.0
END DESCRIPTION:
XS GIS Cut Line= 4
      2910712.65     10130072.79      2911025.13     10129676.98
      2911150.13     10129187.39      2911186.59     10128671.76
#Sta/Elev= 30
  4259.3 1421.77  4469.4 1416.21  4589.6 1410.85  4800.2 1405.45    4841  1405.3
  4881.9 1402.68  4952.7 1400.29  4963.6 1398.21  4973.4 1394.86 4976.01 1392.75
    4994 1385.85    4999 1385.11  5002.3 1385.61  5014.6 1387.85  5029.2 1388.89
  5040.1  1389.4  5045.6 1391.43  5055.9 1393.34  5065.1 1393.84  5121.8 1393.49
  5198.4 1396.18  5203.6  1395.3  5231.4 1396.91  5282.6 1396.92  5311.9 1398.85
  5342.7 1398.59  5422.9 1406.02  5593.3    1413  5643.5 1417.45  5785.8 1421.37
#Mann= 5 ,-1 , 0
  4259.3      .1       0    4994     .07       0  5002.3      .1       0
  5029.2     .16       0  5065.1      .1       0
Bank Sta=4976.01,5055.9
XS Rating Curve= 0 ,0
Exp/Cntr=0.3,0.1

Type RM Length L Ch R = 1 ,22764   ,408,408,408
BEGIN DESCRIPTION:
NORTH CYPRESS CREEK 44.0
END DESCRIPTION:
XS GIS Cut Line= 2
      2911717.84     10129968.67      2911416.18     10128897.23
#Sta/Elev= 30
  4426.7 1415.35  4494.2 1412.08  4525.3 1406.94  4542.6 1405.37  4681.2  1400.4
  4691.5 1399.74  4712.3 1395.21    4733 1393.66  4795.4 1393.04  4850.7 1394.29
  4933.6 1392.24  4963.1  1390.3    4972 1388.65  4982.4 1384.59    4992  1379.8
  4997.2 1379.64    5003  1378.6  5006.2  1379.1    5024 1383.04  5055.2 1383.52
  5089.3 1386.16  5143.7 1385.49  5295.4 1391.51  5314.9 1394.22  5329.4 1394.26
    5346 1396.05  5363.5  1400.7  5368.7 1399.66  5387.6  1403.3  5539.8 1411.83
#Mann= 6 ,-1 , 0
  4426.7     .05       0  4542.6      .1       0  4933.6     .16       0
  4997.2     .07       0  5006.2     .16       0  5089.3      .1       0
Bank Sta=4982.4,5024
XS Rating Curve= 0 ,0
Exp/Cntr=0.3,0.1

Type RM Length L Ch R = 1 ,22356   ,367,367,367
BEGIN DESCRIPTION:
NORTH CYPRESS CREEK 43.0
END DESCRIPTION:
XS GIS Cut Line= 2
      2912082.42     10129932.17      2911769.93     10128729.09
#Sta/Elev= 30
  4254.8 1410.74  4289.9 1407.31    4342 1404.96  4446.9 1400.38  4511.5 1399.12
    4528 1396.41  4586.9 1393.04  4738.8 1386.27  4831.8 1384.04  4852.4 1382.41
  4976.4  1380.2  4986.7 1378.96  4994.1 1376.87  4996.8 1376.37  5004.3  1377.2
  5021.7 1379.06  5038.4 1380.33  5059.1 1382.36  5161.4 1387.82  5193.4 1391.77
    5214 1397.17  5255.4 1401.72    5265 1401.79    5338 1406.61  5358.7 1409.27
  5364.1 1411.33  5383.7 1414.44  5410.3 1416.72    5431 1416.97  5497.8 1422.56
#Mann= 8 ,-1 , 0
  4254.8      .1       0    4342     .05       0  4586.9      .1       0
  4994.1     .07       0  5004.3      .1       0  5021.7     .16       0
    5265      .1       0  5383.7     .16       0
Bank Sta=4976.4,5038.4
XS Rating Curve= 0 ,0
Exp/Cntr=0.3,0.1

Type RM Length L Ch R = 1 ,21989   ,609,609,609
BEGIN DESCRIPTION:
NORTH CYPRESS CREEK 42.0
END DESCRIPTION:
XS GIS Cut Line= 4
      2912389.71     10129864.49      2912337.63     10129265.52
      2912144.92     10128921.77      2912087.64     10128572.86
#Sta/Elev= 30
  4184.1 1408.18    4225 1404.16  4355.5  1398.4  4414.9  1393.1  4566.3 1387.05
  4737.3  1382.9  4874.5 1379.02  4896.2 1379.37  4970.8    1376    4983 1371.78
  4993.2  1369.9  4998.7  1368.7  5005.2 1370.17  5036.6 1375.62  5052.2 1375.77
    5074 1375.61  5095.9  1381.1  5101.6 1380.96  5117.6 1385.96  5123.3 1385.43
    5145 1388.89    5161 1393.47  5166.7 1393.41  5175.4 1396.29  5179.4 1396.29
  5185.4  1398.9  5197.7 1400.31  5435.6 1418.13  5496.8 1427.06    5533 1429.89
#Mann= 6 ,-1 , 0
  4184.1      .1       0  4414.9     .16       0  4737.3      .1       0
  4993.2     .07       0  5005.2      .1       0  5052.2     .16       0
Bank Sta=4970.8,5036.6
XS Rating Curve= 0 ,0
Exp/Cntr=0.3,0.1

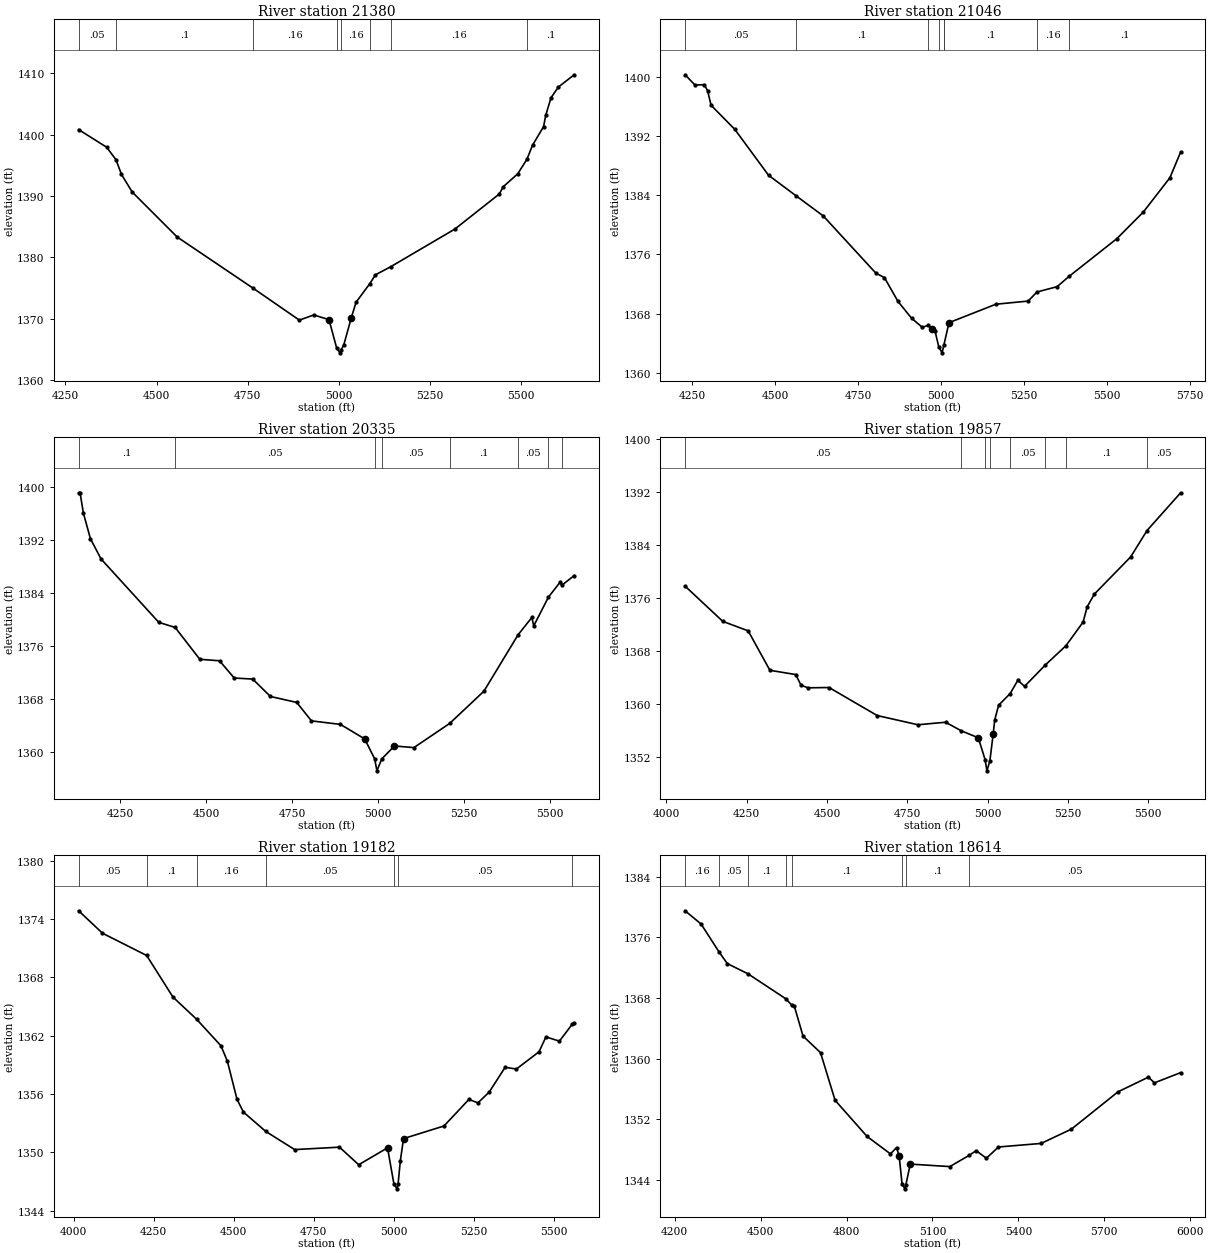
Type RM Length L Ch R = 1 ,21380   ,334,334,334
BEGIN DESCRIPTION:
NORTH CYPRESS CREEK 41.0
END DESCRIPTION:
XS GIS Cut Line= 3
      2912676.18     10129739.44      2912853.25     10128775.93
      2912790.76     10128400.95
#Sta/Elev= 30
  4286.1 1400.81  4363.1 1397.93  4388.7 1395.89  4403.7  1393.5  4433.1 1390.64
  4556.3 1383.32  4764.1    1375  4891.8 1369.77  4931.2 1370.61  4973.1 1369.85
  4994.4 1365.17  5003.4 1364.44  5006.6 1364.94  5013.8 1365.75  5034.1 1370.12
  5047.5 1372.69    5085  1375.7  5100.6 1377.15  5142.8 1378.48  5318.7 1384.61
  5440.3 1390.31  5451.2  1391.5    5491  1393.6  5516.4 1395.99  5531.6 1398.26
    5562  1401.3  5567.8 1403.12  5582.3 1405.99  5602.5 1407.74  5645.9 1409.74
#Mann= 8 ,-1 , 0
  4286.1     .05       0  4388.7      .1       0  4764.1     .16       0
  4994.4     .07       0  5006.6     .16       0    5085      .1       0
  5142.8     .16       0  5516.4      .1       0
Bank Sta=4973.1,5034.1
XS Rating Curve= 0 ,0
Exp/Cntr=0.3,0.1

Type RM Length L Ch R = 1 ,21046   ,711,711,711
BEGIN DESCRIPTION:
NORTH CYPRESS CREEK 40.0
END DESCRIPTION:
XS GIS Cut Line= 3
      2912957.42     10129880.09      2913186.59     10128859.27
      2913181.38     10128411.33
#Sta/Elev= 30
  4228.1 1400.29    4258  1398.9  4285.9 1398.95  4296.1 1398.12  4306.4 1396.17
  4378.1  1392.9  4479.7  1386.7  4563.9 1383.88  4644.6  1381.2  4803.5 1373.45
  4829.1 1372.86  4870.1 1369.63    4911 1367.36  4943.7 1366.12  4960.7 1366.41
  4972.5 1365.97  4981.9 1365.59    4993 1363.49    5003 1362.68  5008.6 1363.78
  5023.8 1366.76  5165.5 1369.26  5262.4 1369.68    5289 1370.91  5349.9 1371.63
  5386.1 1373.03  5529.9 1378.12  5609.9 1381.73  5689.9 1386.36  5722.3 1389.84
#Mann= 8 ,-1 , 0
  4228.1     .05       0  4563.9      .1       0  4960.7     .16       0
    4993     .07       0  5008.6     .16       0  5008.6      .1       0
    5289     .16       0  5386.1      .1       0
Bank Sta=4972.5,5023.8
XS Rating Curve= 0 ,0
Exp/Cntr=0.3,0.1

Type RM Length L Ch R = 1 ,20335   ,478,478,478
BEGIN DESCRIPTION:
NORTH CYPRESS CREEK 39.0
END DESCRIPTION:
XS GIS Cut Line= 4
      2913905.34     10129557.19      2913743.88     10128854.06
       2913509.5     10128671.77      2913348.06     10128281.17
#Sta/Elev= 30
  4129.5 1399.06  4133.7 1399.06  4143.3    1396  4163.8 1392.14  4194.6 1389.09
  4362.6 1379.53  4410.2 1378.76  4481.9 1373.96  4539.2 1373.74    4582 1371.14
  4635.8 1370.98  4687.1 1368.36  4763.7 1367.46  4806.6 1364.68  4890.8 1364.15
  4961.4 1361.96  4990.4 1358.95  4996.9 1357.15  5011.2 1358.96  5047.8  1360.9
  5104.4 1360.65  5208.6  1364.3    5308 1369.15  5407.2 1377.64  5447.5 1380.27
  5452.9    1379  5495.8 1383.34    5530 1385.61  5534.3 1385.11  5570.5 1386.58
#Mann= 8 ,-1 , 0
  4129.5      .1       0  4410.2     .05       0  4990.4    .035       0
  5011.2     .05       0  5208.6      .1       0  5407.2     .05       0
  5495.8      .1       0  5534.3     .05       0
Bank Sta=4961.4,5047.8
XS Rating Curve= 0 ,0
Exp/Cntr=0.3,0.1

Type RM Length L Ch R = 1 ,19857   ,675,675,675
BEGIN DESCRIPTION:
NORTH CYPRESS CREEK 38.0
END DESCRIPTION:
XS GIS Cut Line= 4
      2914301.17     10129197.82      2913941.79     10128510.31
      2913707.42     10128161.35      2913394.94     10128010.32
#Sta/Elev= 30
    4058 1377.82  4175.4  1372.5  4254.4 1371.07  4322.1 1365.11  4402.6 1364.47
    4419 1362.85  4441.1 1362.47  4506.4 1362.51  4656.2 1358.28  4783.1 1356.89
  4869.2 1357.27  4917.9 1355.98  4971.2 1354.92  4992.2 1351.62    4998 1349.93
  5007.2 1351.47 5017.63 1355.56  5022.2 1357.62  5034.4 1359.84  5070.1 1361.59
  5094.2  1363.6  5115.2 1362.69  5180.2 1365.93  5244.1 1368.83  5297.4 1372.39
  5310.1  1374.7  5332.7 1376.63  5445.7 1382.24  5496.5 1386.22  5601.2 1391.92
#Mann= 8 ,-1 , 0
    4058     .05       0  4917.9      .1       0  4992.2     .07       0
  5007.2      .1       0  5070.1     .05       0  5180.2     .16       0
  5244.1      .1       0  5496.5     .05       0
Bank Sta=4971.2,5017.63
XS Rating Curve= 0 ,0
Exp/Cntr=0.3,0.1

Type RM Length L Ch R = 1 ,19182   ,568,568,568
BEGIN DESCRIPTION:
NORTH CYPRESS CREEK 36.0
END DESCRIPTION:
XS GIS Cut Line= 3
      2914493.88     10129208.24      2914499.09     10128150.93
      2914144.89     10127812.37
#Sta/Elev= 30
  4015.5 1374.86    4090 1372.55  4227.9 1370.26    4310 1365.98  4383.7  1363.7
    4460 1360.96    4480 1359.37    4510 1355.46    4530 1354.14  4599.8 1352.15
    4690 1350.28    4830 1350.53    4890 1348.72    4980 1350.46    5000 1346.74
  5009.8 1346.24    5013 1346.74    5020 1349.13    5030 1351.41  5156.3 1352.71
    5234 1355.44  5262.3 1355.09  5297.5  1356.2  5347.2 1358.75  5382.4 1358.57
  5453.2 1360.35  5474.6 1361.88  5516.7 1361.44  5557.4 1363.21  5562.8 1363.26
#Mann= 7 ,-1 , 0
  4015.5     .05       0  4227.9      .1       0  4383.7     .16       0
  4599.8     .05       0    5000    .035       0    5013     .05       0
  5557.4      .1       0
Bank Sta=4980,5030
XS Rating Curve= 0 ,0
Exp/Cntr=0.3,0.1

Type RM Length L Ch R = 1 ,18614   ,729,729,729
BEGIN DESCRIPTION:
NORTH CYPRESS CREEK 35.0
END DESCRIPTION:
XS GIS Cut Line= 3
      2915077.21     10129218.63      2914920.96     10128374.89
      2914322.76     10127740.27
#Sta/Elev= 30
  4236.4 1379.53  4292.2 1377.78  4355.1 1374.08  4383.8 1372.55  4455.9  1371.2
  4587.6 1367.91  4608.6 1367.08  4617.7 1366.93  4648.2 1362.97  4709.2 1360.78
  4760.1 1354.48  4871.9  1349.7  4953.3  1347.4  4974.8 1348.23  4983.8 1347.12
    4994 1343.41  5003.9 1342.78  5007.1 1343.28  5022.6 1346.05  5160.8 1345.72
  5228.8 1347.22  5252.7 1347.83  5288.3 1346.82  5330.3 1348.31  5479.2 1348.78
  5585.2 1350.67  5747.9  1355.6  5853.9 1357.54  5875.3 1356.79  5966.6 1358.14
#Mann= 8 ,-1 , 0
  4236.4     .16       0  4355.1     .05       0  4455.9      .1       0
  4587.6     .16       0  4608.6      .1       0    4994     .07       0
  5007.1      .1       0  5228.8     .05       0
Bank Sta=4983.8,5022.6
XS Rating Curve= 0 ,0
Exp/Cntr=0.3,0.1

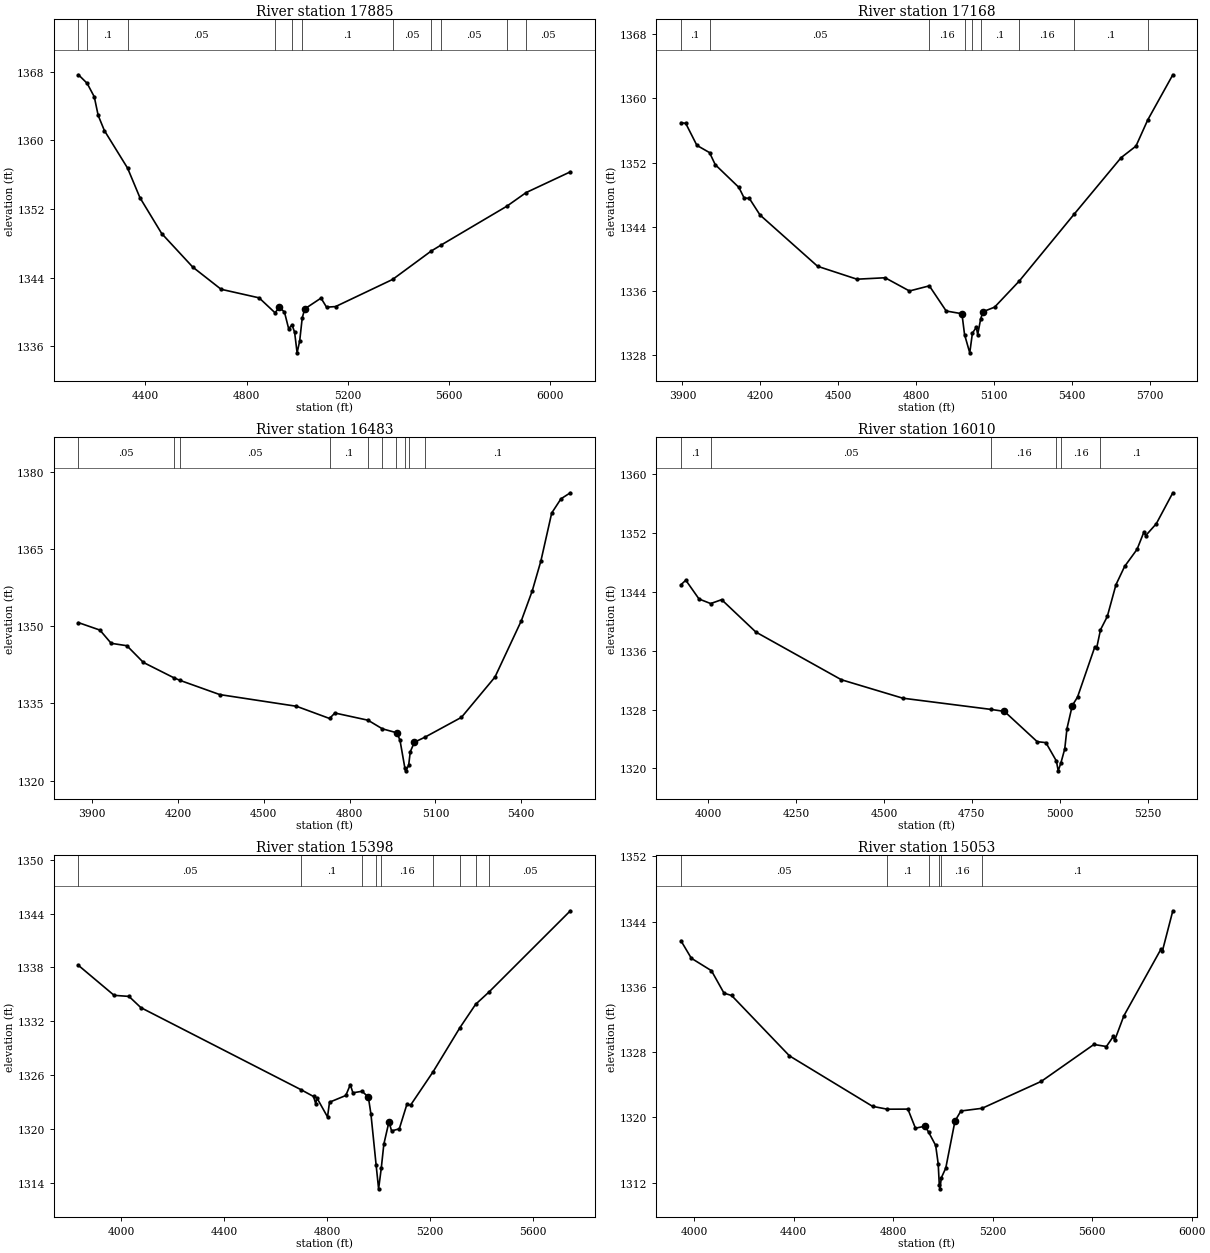
Type RM Length L Ch R = 1 ,17885   ,717,717,717
BEGIN DESCRIPTION:
NORTH CYPRESS CREEK 33.0
END DESCRIPTION:
XS GIS Cut Line= 3
      2915389.71      10128906.1      2915311.59     10127926.98
      2914394.89     10127630.09
#Sta/Elev= 30
    4135 1367.67  4169.2 1366.68  4197.6  1365.1    4213 1362.93  4237.7 1361.15
  4329.4 1356.77  4378.1 1353.33  4464.2 1349.14  4587.2 1345.22  4699.2 1342.63
  4849.6 1341.63  4912.5 1339.89  4929.9 1340.52  4949.9 1339.97  4966.4 1338.04
    4980 1338.47  4990.1 1337.61  4999.9 1335.21  5010.1 1336.59  5020.2 1339.29
  5030.2 1340.34  5094.5  1341.6  5116.4 1340.54    5152 1340.61  5377.8 1343.78
  5530.2 1347.09  5567.7 1347.76  5829.2 1352.32  5905.9 1353.92  6080.8 1356.34
#Mann= 11 ,-1 , 0
    4135     .05       0  4169.2      .1       0  4329.4     .05       0
  4912.5      .1       0    4980     .07       0  5020.2      .1       0
  5377.8     .05       0  5530.2      .1       0  5567.7     .05       0
  5829.2      .1       0  5905.9     .05       0
Bank Sta=4929.9,5030.2
XS Rating Curve= 0 ,0
Exp/Cntr=0.3,0.1

Type RM Length L Ch R = 1 ,17168   ,685,685,685
BEGIN DESCRIPTION:
NORTH CYPRESS CREEK 32.0
END DESCRIPTION:
XS GIS Cut Line= 3
      2915720.44     10128804.55      2915902.73      10127545.9
      2915503.55     10127068.61
#Sta/Elev= 30
  3894.3 1356.98  3912.8  1356.9  3955.8 1354.15  4004.4 1353.25  4026.5 1351.74
  4117.4 1348.91  4137.6 1347.59  4157.8 1347.53  4198.9 1345.46  4420.6 1339.06
  4572.1 1337.45  4680.5 1337.63  4774.2 1335.98  4850.8 1336.62  4915.7 1333.48
  4976.3 1333.14  4986.4 1330.54  5006.4 1328.26  5016.7 1330.73  5031.8 1331.45
  5036.9 1330.53  5048.2 1332.45  5057.1 1333.39    5102 1333.96  5197.3 1337.23
  5409.5 1345.61  5589.2 1352.62  5646.4 1354.06  5691.6 1357.32  5788.3 1362.96
#Mann= 9 ,-1 , 0
  3894.3      .1       0  4004.4     .05       0  4850.8     .16       0
  4986.4     .07       0  5016.7     .16       0  5048.2      .1       0
  5197.3     .16       0  5409.5      .1       0  5691.6     .05       0
Bank Sta=4976.3,5057.1
XS Rating Curve= 0 ,0
Exp/Cntr=0.3,0.1

Type RM Length L Ch R = 1 ,16483   ,473,473,473
BEGIN DESCRIPTION:
NORTH CYPRESS CREEK 31.0
END DESCRIPTION:
XS GIS Cut Line= 4
      2916280.33     10128952.17      2916549.43     10128153.54
      2916488.67     10127619.68      2916519.06      10127281.1
#Sta/Elev= 30
  3851.7 1350.69  3926.7 1349.24  3966.1 1346.67  4021.1  1346.2  4078.8 1342.95
  4184.6 1339.99  4207.6 1339.45    4346  1336.7  4614.1 1334.43  4729.6 1332.06
  4748.4 1333.12  4864.2 1331.72  4914.3 1330.05  4963.7 1329.29    4966 1329.21
  4976.1  1327.8  4993.2 1322.38  4995.9 1321.88  5006.3 1322.94  5011.9 1325.58
  5026.4 1327.44  5063.1 1328.42  5190.9 1332.28    5308  1340.1  5400.3 1351.06
  5438.5 1356.87  5468.7 1362.68  5506.5    1372  5538.9 1374.76  5571.7 1375.93
#Mann= 10 ,-1 , 0
  3851.7     .05       0  4184.6      .1       0  4207.6     .05       0
  4729.6      .1       0  4864.2     .16       0  4914.3      .1       0
  4963.7     .16       0  4993.2     .07       0  5006.3     .16       0
  5063.1      .1       0
Bank Sta=4966,5026.4
XS Rating Curve= 0 ,0
Exp/Cntr=0.3,0.1

Type RM Length L Ch R = 1 ,16010   ,612,612,612
BEGIN DESCRIPTION:
NORTH CYPRESS CREEK 30.0
END DESCRIPTION:
XS GIS Cut Line= 2
      2916588.48     10128921.81      2917091.31     10127617.05
#Sta/Elev= 30
    3923 1344.99  3936.9 1345.61  3974.5 1343.05  4007.6 1342.43  4038.8 1342.96
  4136.1 1338.55  4379.1 1332.06  4553.6 1329.55  4804.7 1328.02  4842.6 1327.75
  4935.8 1323.63  4960.5  1323.5  4990.4 1320.99  4995.5 1319.66  5003.3 1320.76
  5014.1 1322.65  5020.4 1325.42  5035.5 1328.55  5050.4  1329.7  5099.6 1336.54
    5105 1336.43  5115.7 1338.86    5135 1340.67  5159.6 1344.99  5184.2 1347.48
  5219.6 1349.81  5238.8 1352.13  5244.2 1351.68  5274.2 1353.29  5321.3 1357.51
#Mann= 6 ,-1 , 0
    3923      .1       0  4007.6     .05       0  4804.7     .16       0
  4990.4     .07       0  5003.3     .16       0  5115.7      .1       0
Bank Sta=4842.6,5035.5
XS Rating Curve= 0 ,0
Exp/Cntr=0.3,0.1

Type RM Length L Ch R = 1 ,15398   ,345,345,345
BEGIN DESCRIPTION:
NORTH CYPRESS CREEK 29.0
END DESCRIPTION:
XS GIS Cut Line= 4
      2917304.64     10129177.83      2917552.04     10128209.96
       2917569.4     10127771.59      2917356.71     10127350.56
#Sta/Elev= 30
  3834.9 1338.22  3973.3 1334.88  4031.1 1334.76  4077.1 1333.51  4699.2 1324.35
  4747.4  1323.6  4755.7 1322.81  4760.9 1323.42  4801.7 1321.32  4809.4 1322.96
  4872.6 1323.71  4890.2 1324.92  4900.2 1324.01  4935.9 1324.18  4960.2 1323.53
  4970.2 1321.65  4990.2    1316    5000  1313.3  5010.3 1315.59  5020.3 1318.28
  5040.3 1320.79  5050.3 1319.76  5080.3 1319.99  5110.3 1322.77    5124 1322.63
  5211.8 1326.37  5315.5 1331.27  5376.6 1333.88  5428.1 1335.24  5744.3 1344.31
#Mann= 9 ,-1 , 0
  3834.9     .05       0  4699.2      .1       0  4935.9     .16       0
  4990.2     .07       0  5010.3     .16       0  5211.8      .1       0
  5315.5     .05       0  5376.6      .1       0  5428.1     .05       0
Bank Sta=4960.2,5040.3
XS Rating Curve= 0 ,0
Exp/Cntr=0.3,0.1

Type RM Length L Ch R = 1 ,15053   ,524,524,524
BEGIN DESCRIPTION:
NORTH CYPRESS CREEK 28.0
END DESCRIPTION:
XS GIS Cut Line= 4
      2917973.05     10129065.02      2917851.52     10128279.41
      2917938.32     10127771.59      2917868.94     10127108.15
#Sta/Elev= 30
  3947.1 1341.67  3988.9 1339.52  4069.8 1337.99  4120.4 1335.23  4150.8 1334.95
  4383.5 1327.54  4717.4 1321.35  4776.4    1321  4859.4 1321.01  4889.8 1318.67
  4928.5 1318.92  4943.1 1318.16    4971 1316.56  4981.2 1314.31  4985.6 1311.73
  4988.4 1311.23  4993.7 1312.58  5011.6 1313.77  5048.7 1319.55  5072.5 1320.78
  5157.6 1321.11  5395.4 1324.41    5607 1328.94  5657.3 1328.69  5685.5 1329.94
  5690.5 1329.44  5727.6 1332.46  5877.1 1340.66  5882.2 1340.38  5924.3 1345.34
#Mann= 6 ,-1 , 0
  3947.1     .05       0  4776.4      .1       0  4943.1     .16       0
  4985.6     .07       0  4993.7     .16       0  5157.6      .1       0
Bank Sta=4928.5,5048.7
XS Rating Curve= 0 ,0
Exp/Cntr=0.3,0.1