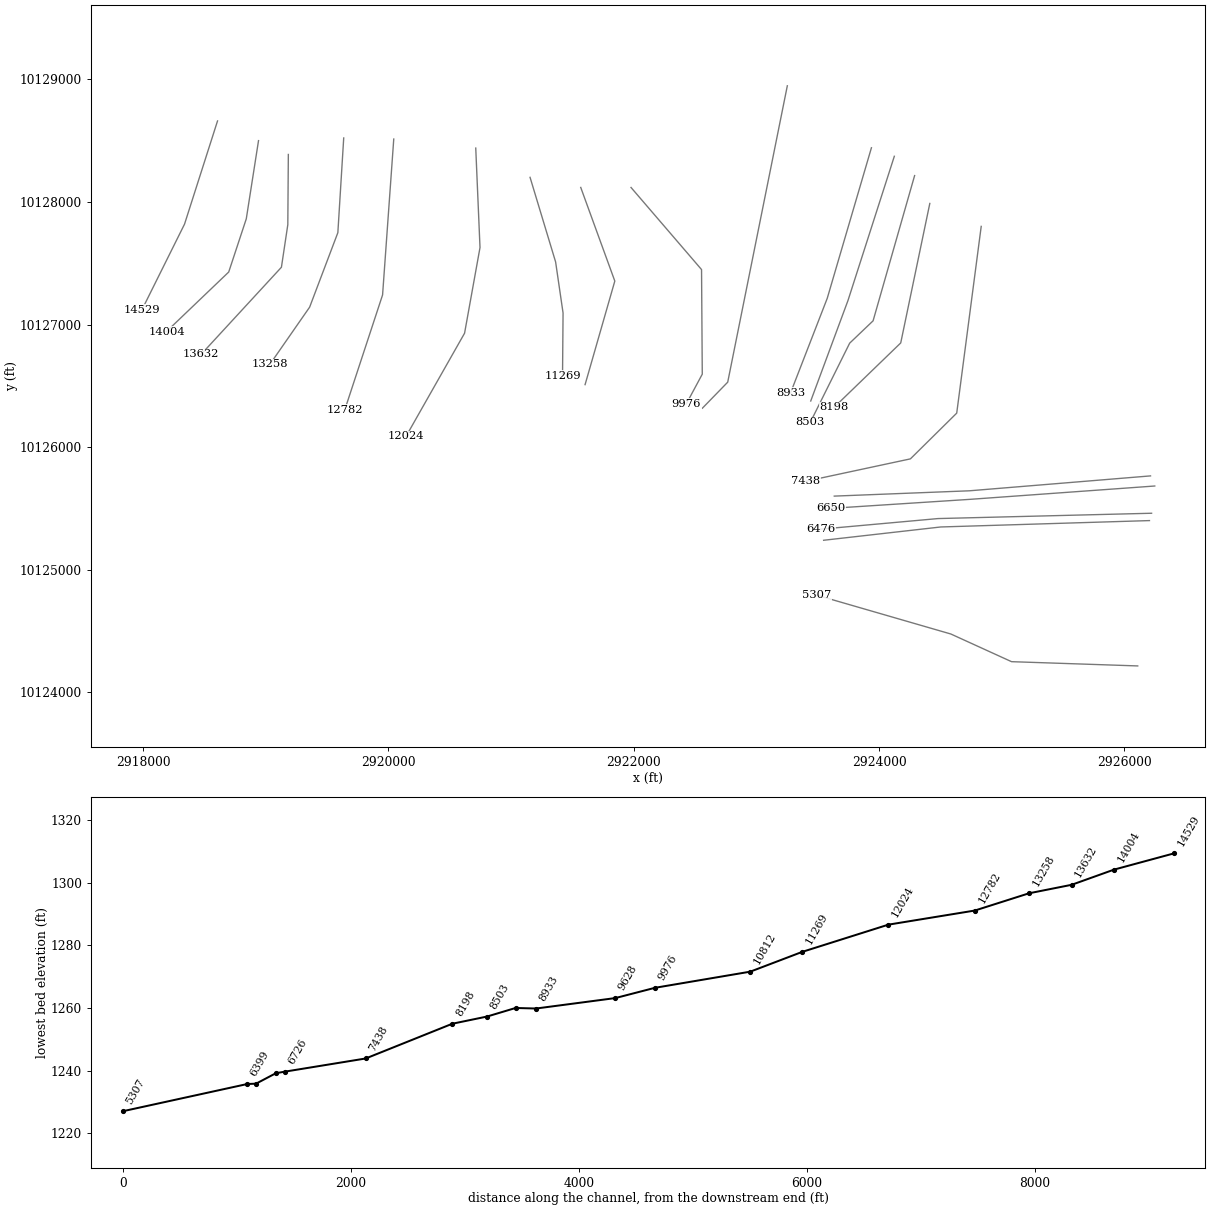
HEC-RAS study NORTH CYPRESS CREEK.prj: NORTH CYPRESS CREEK Base Level Engineering

--- NORTH CYPRESS CREEK.g01 (geometry) --- (continued)

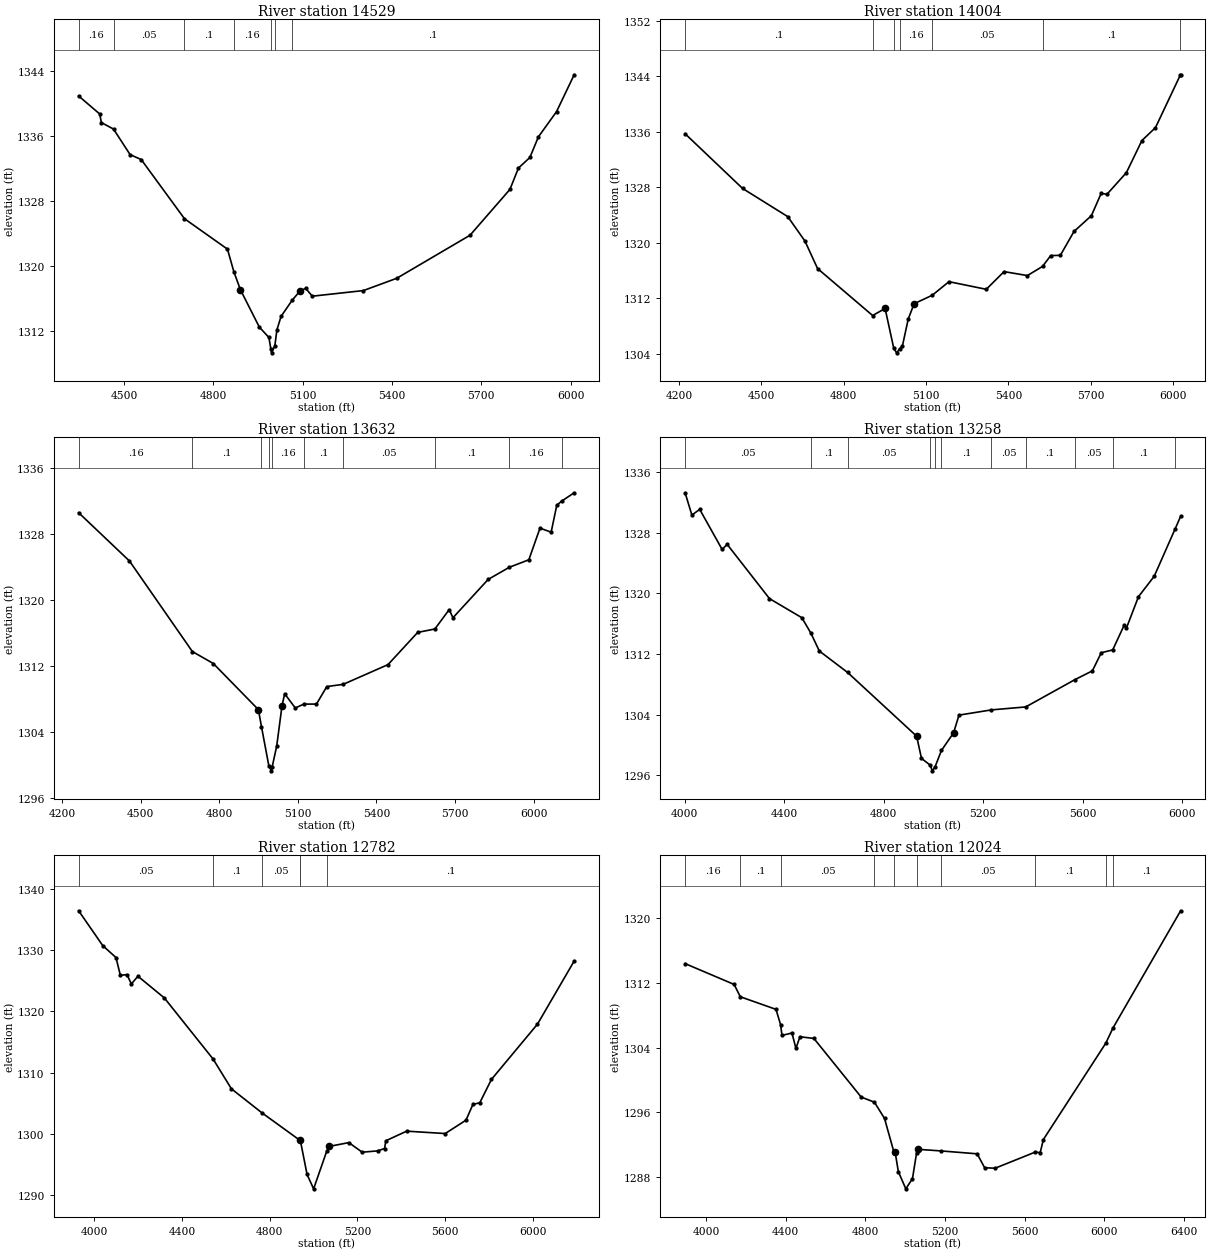
Type RM Length L Ch R = 1 ,14529   ,525,525,525
BEGIN DESCRIPTION:
NORTH CYPRESS CREEK 27.0
END DESCRIPTION:
XS GIS Cut Line= 3
      2918606.72     10128661.33      2918337.63     10127819.34
      2917990.42     10127120.59
#Sta/Elev= 30
  4347.8  1340.9  4418.8 1338.68  4424.1 1337.63    4465 1336.83  4520.6 1333.69
    4558 1333.08  4703.3  1325.8  4847.6 1322.06  4869.2 1319.27  4891.2 1317.06
  4954.6 1312.47  4986.8 1311.19  4993.2  1309.8  4995.9  1309.3  5006.7 1310.16
  5013.7 1312.12  5027.7 1313.79  5065.1 1315.78  5090.7 1316.88  5110.2 1317.24
  5132.6 1316.27    5304 1316.96    5416 1318.47  5662.3 1323.77  5796.3 1329.41
  5824.8 1332.03  5863.3 1333.34    5892 1335.88  5952.7 1338.97    6012 1343.51
#Mann= 7 ,-1 , 0
  4347.8     .16       0    4465     .05       0  4703.3      .1       0
  4869.2     .16       0  4993.2     .07       0  5006.7     .16       0
  5065.1      .1       0
Bank Sta=4891.2,5090.7
XS Rating Curve= 0 ,0
Exp/Cntr=0.3,0.1

Type RM Length L Ch R = 1 ,14004   ,372,372,372
BEGIN DESCRIPTION:
NORTH CYPRESS CREEK 26.0
END DESCRIPTION:
XS GIS Cut Line= 4
      2918940.92     10128500.73       2918841.1     10127862.74
      2918697.87     10127428.71      2918190.04     10126942.58
#Sta/Elev= 30
  4221.9 1335.72  4431.4 1327.83    4596 1323.77  4658.7 1320.24  4704.7 1316.28
  4905.3 1309.51  4950.7 1310.53  4982.4 1304.76  4992.7 1304.13  5003.5 1304.69
    5014 1305.15  5035.1 1309.02  5056.5 1311.21  5122.4 1312.43  5183.5 1314.39
  5319.4 1313.29  5384.3 1315.84  5469.3 1315.27  5524.4 1316.59  5554.2 1318.15
  5589.4 1318.19  5639.1 1321.63  5702.6 1323.91  5738.1 1327.12  5759.2 1326.99
    5830 1330.11  5886.6 1334.74    5936  1336.6    6027 1344.22  6027.7 1344.22
#Mann= 7 ,-1 , 0
  4221.9      .1       0  4905.3     .16       0  4982.4     .07       0
  5003.5     .16       0  5122.4     .05       0  5524.4      .1       0
    6027     .05       0
Bank Sta=4950.7,5056.5
XS Rating Curve= 0 ,0
Exp/Cntr=0.3,0.1

Type RM Length L Ch R = 1 ,13632   ,374,374,374
BEGIN DESCRIPTION:
NORTH CYPRESS CREEK 25.0
END DESCRIPTION:
XS GIS Cut Line= 4
      2919183.98     10128387.87      2919179.64       10127815.
      2919127.56     10127467.77      2918472.16     10126755.95
#Sta/Elev= 30
    4263 1330.53  4457.1 1324.68  4697.2 1313.72  4777.2 1312.27  4949.2 1306.69
  4960.9 1304.64  4988.8 1299.92  4998.7 1299.28    5002 1299.78  5019.2  1302.3
  5039.4 1307.17  5049.5 1308.61    5090 1306.89  5122.6 1307.36  5170.9 1307.36
  5210.3 1309.48  5272.9 1309.75    5444 1312.14  5557.4 1316.04  5622.9 1316.45
  5677.6  1318.8  5691.8 1317.81  5826.2 1322.45    5907 1323.92  5981.6 1324.83
  6024.1 1328.66  6066.7 1328.17  6088.2 1331.43  6107.4 1331.94  6154.6 1332.94
#Mann= 10 ,-1 , 0
    4263     .16       0  4697.2      .1       0  4960.9     .16       0
  4988.8     .07       0    5002     .16       0  5122.6      .1       0
  5272.9     .05       0  5622.9      .1       0    5907     .16       0
  6107.4      .1       0
Bank Sta=4949.2,5039.4
XS Rating Curve= 0 ,0
Exp/Cntr=0.3,0.1

Type RM Length L Ch R = 1 ,13258   ,476,476,476
BEGIN DESCRIPTION:
NORTH CYPRESS CREEK 24.0
END DESCRIPTION:
XS GIS Cut Line= 4
      2919635.37     10128522.46      2919587.63     10127749.89
      2919357.59     10127142.25      2919032.79     10126674.54
#Sta/Elev= 30
  4001.2 1333.25  4028.5 1330.31    4060 1331.06  4150.2 1325.77  4170.3 1326.45
  4340.6 1319.29  4470.8 1316.77  4507.4 1314.72    4541 1312.38  4654.8 1309.55
  4932.5 1301.14    4952 1298.21  4987.5 1297.31  4995.4 1296.57  5006.4 1297.08
  5032.3 1299.26  5081.2 1301.59  5102.8 1303.92  5233.4 1304.61  5371.2    1305
    5568 1308.58  5639.4 1309.76  5675.2 1312.15  5721.1 1312.52  5767.7 1315.81
  5776.2 1315.39  5824.9 1319.55    5888 1322.23  5972.7 1328.52  5994.4 1330.14
#Mann= 11 ,-1 , 0
  4001.2     .05       0  4507.4      .1       0  4654.8     .05       0
  4987.5    .035       0  5006.4     .05       0  5032.3      .1       0
  5233.4     .05       0  5371.2      .1       0    5568     .05       0
  5721.1      .1       0  5972.7     .16       0
Bank Sta=4932.5,5081.2
XS Rating Curve= 0 ,0
Exp/Cntr=0.3,0.1

Type RM Length L Ch R = 1 ,12782   ,758,758,758
BEGIN DESCRIPTION:
NORTH CYPRESS CREEK 23.0
END DESCRIPTION:
XS GIS Cut Line= 3
      2920043.36     10128513.77      2919952.21     10127242.08
      2919644.05     10126304.58
#Sta/Elev= 30
  3927.8 1336.42  4038.1 1330.73  4098.3 1328.79  4118.3 1325.88  4148.4 1326.01
  4168.5 1324.49  4198.5 1325.74  4318.8 1322.21  4541.4 1312.24  4625.1 1307.38
  4762.6 1303.51  4938.8 1298.95  4940.4 1298.84  4970.5  1293.4  5000.3 1291.06
  5060.7 1297.25  5070.8 1297.98    5161  1298.6  5222.1 1297.04  5292.6 1297.25
  5324.4 1297.64  5329.7  1298.9  5425.1 1300.47    5601 1300.08  5695.8 1302.26
  5727.3 1304.82  5758.9 1305.11    5812 1308.91  6022.1 1317.93  6189.6 1328.22
#Mann= 6 ,-1 , 0
  3927.8     .05       0  4541.4      .1       0  4762.6     .05       0
  4938.8      .1       0  4940.4     .07       0  5060.7      .1       0
Bank Sta=4938.8,5070.8
XS Rating Curve= 0 ,0
Exp/Cntr=0.3,0.1

Type RM Length L Ch R = 1 ,12024   ,755,755,755
BEGIN DESCRIPTION:
NORTH CYPRESS CREEK 21.0
END DESCRIPTION:
XS GIS Cut Line= 4
      2920711.76     10128440.01      2920746.48     10127628.36
      2920620.61     10126929.58      2920143.66     10126088.41
#Sta/Elev= 30
  3894.1 1314.41  4140.6 1311.83  4171.3 1310.31  4350.8 1308.75    4374 1306.84
  4380.8 1305.53  4430.9 1305.83  4450.9 1303.92  4470.9 1305.36    4541 1305.16
  4778.6 1297.91  4845.3 1297.27    4896 1295.26  4944.5 1290.99  4949.6 1291.06
  4965.2  1288.7  5002.9 1286.56  5036.3 1287.82  5056.7 1290.95  5061.9 1291.45
  5178.9 1291.25  5361.5 1290.89  5398.7 1289.17  5451.6 1289.11  5650.6 1291.08
  5678.1 1291.05    5694 1292.66  6007.5 1304.57  6043.4 1306.44  6383.5 1320.94
#Mann= 10 ,-1 , 0
  3894.1     .16       0  4171.3      .1       0    4374     .05       0
  4845.3      .1       0  4944.5     .07       0  5056.7      .1       0
  5178.9     .05       0  5650.6      .1       0  6007.5     .05       0
  6043.4      .1       0
Bank Sta=4949.6,5061.9
XS Rating Curve= 0 ,0
Exp/Cntr=0.3,0.1

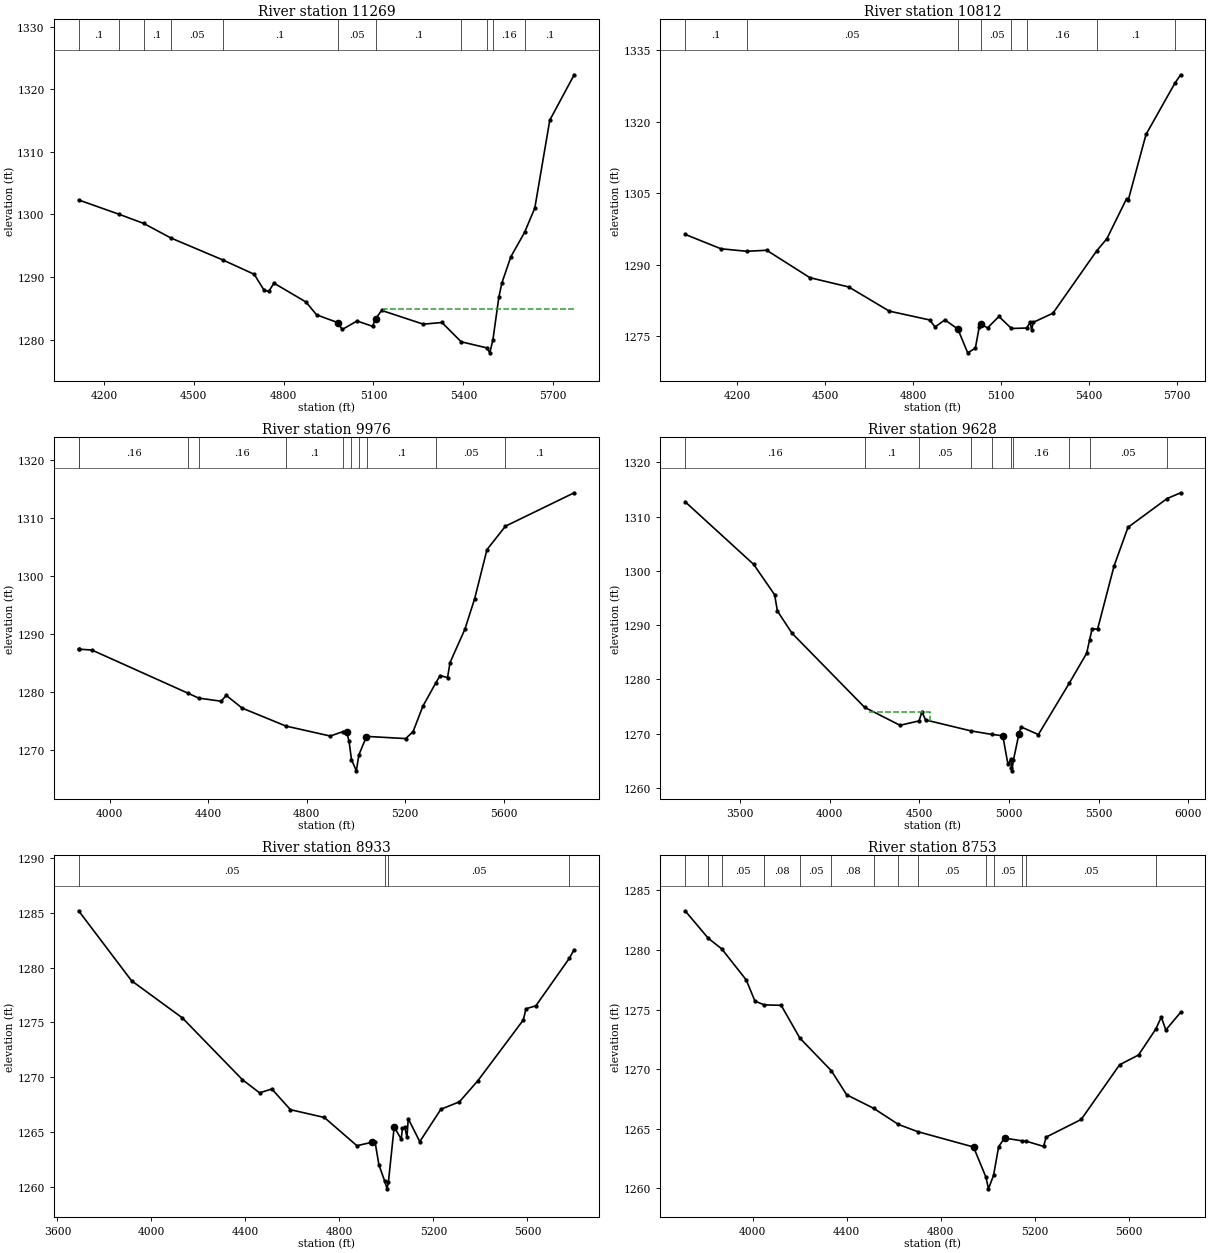
Type RM Length L Ch R = 1 ,11269   ,457,457,457
BEGIN DESCRIPTION:
NORTH CYPRESS CREEK 20.0
END DESCRIPTION:
XS GIS Cut Line= 4
      2921154.48     10128201.24       2921362.8     10127511.18
      2921423.57     10127094.51      2921419.22     10126582.33
#Sta/Elev= 30
  4115.8 1302.31  4249.1 1300.05  4332.4 1298.57  4423.4 1296.24  4596.3 1292.74
  4701.9 1290.43  4734.9 1287.88  4750.4  1287.7  4767.9 1289.01  4874.5 1286.01
  4910.2 1283.95  4980.2 1282.72  4995.7 1281.61  5045.2 1282.97  5096.8 1282.12
  5106.9  1283.3  5127.1 1284.66  5266.4 1282.46  5328.5 1282.73  5392.6 1279.65
  5478.5 1278.67  5488.2 1277.88  5498.5 1279.91  5518.5 1286.78  5528.5 1289.03
  5558.5 1293.23  5604.2 1297.11  5638.5 1301.02  5688.5 1315.06  5769.9 1322.31
#Mann= 11 ,-1 , 0
  4115.8      .1       0  4249.1     .05       0  4332.4      .1       0
  4423.4     .05       0  4596.3      .1       0  4980.2     .05       0
  5106.9      .1       0  5392.6     .16       0  5478.5     .04       0
  5498.5     .16       0  5604.2      .1       0
#XS Ineff= 2 , 0
       0                 5135.52       0 1284.94
Permanent Ineff=
       F       T
Bank Sta=4980.2,5106.9
XS Rating Curve= 0 ,0
Exp/Cntr=0.3,0.1

Type RM Length L Ch R = 1 ,10812   ,836,836,836
BEGIN DESCRIPTION:
NORTH CYPRESS CREEK 19.0
END DESCRIPTION:
XS GIS Cut Line= 3
      2921567.67      10128118.8      2921845.44     10127354.93
      2921603.08     10126510.12
#Sta/Elev= 30
  4022.1 1296.37  4144.5 1293.35    4233 1292.82  4300.6 1293.04  4448.3 1287.29
  4580.8 1285.35  4719.1 1280.29    4857 1278.44  4875.4 1276.97    4909 1278.45
  4953.3 1276.53  4986.8 1271.55    5013 1272.53    5026 1276.87  5033.8 1277.51
  5054.5 1276.77  5093.5 1279.17  5136.2 1276.65  5188.2 1276.75  5199.9 1277.94
  5205.1 1276.34  5210.7 1277.94  5277.8 1279.85    5427  1292.9  5462.1 1295.47
  5529.5 1303.87  5534.7 1303.48  5595.6  1317.3  5693.8    1328  5713.8  1329.8
#Mann= 8 ,-1 , 0
  4022.1      .1       0    4233     .05       0  4953.3     .04       0
  5033.8     .05       0  5136.2      .1       0  5188.2     .16       0
    5427      .1       0  5693.8     .05       0
Bank Sta=4953.3,5033.8
XS Rating Curve= 0 ,0
Exp/Cntr=0.3,0.1

Type RM Length L Ch R = 1 ,9976    ,348,348,348
BEGIN DESCRIPTION:
NORTH CYPRESS CREEK 17.0
END DESCRIPTION:
XS GIS Cut Line= 4
      2921977.67     10128118.51      2922552.51     10127448.85
      2922558.44     10126595.47      2922428.06     10126352.49
#Sta/Elev= 30
  3874.6 1287.41  3874.8 1287.41  3928.3 1287.26  4320.3 1279.77  4361.8 1278.96
  4452.9 1278.42    4474 1279.42  4538.5 1277.23  4716.3 1274.13    4896 1272.41
  4948.3 1273.18  4962.3  1273.1  4972.3 1271.54  4982.3 1268.33    5002  1266.4
  5012.3 1269.16  5042.3 1272.25  5046.6 1272.34  5202.3 1271.97  5232.3 1273.17
  5272.3 1277.58  5324.4 1281.57  5342.3 1282.85  5372.3  1282.5  5382.3 1285.09
  5442.3 1290.81  5482.3 1296.12  5532.3 1304.59  5607.3 1308.64  5886.3 1314.41
#Mann= 11 ,-1 , 0
  3874.6      .1       0  3874.8     .16       0  4320.3     .05       0
  4361.8     .16       0  4716.3      .1       0  4948.3     .16       0
  4982.3     .07       0  5012.3     .16       0  5046.6      .1       0
  5324.4     .05       0  5607.3      .1       0
Bank Sta=4962.3,5042.3
XS Rating Curve= 0 ,0
Exp/Cntr=0.3,0.1

Type RM Length L Ch R = 1 ,9628    ,695,695,695
BEGIN DESCRIPTION:
NORTH CYPRESS CREEK 16.0
END DESCRIPTION:
XS GIS Cut Line= 3
      2923251.81     10128948.22      2922765.86     10126530.28
       2922559.3     10126317.83
#Sta/Elev= 30
  3194.3 1312.73  3576.3 1301.19  3693.5 1295.57  3708.9 1292.58  3790.1  1288.5
    4195 1274.83  4392.3 1271.52  4498.4 1272.32  4514.7 1273.98  4535.1  1272.5
  4788.4 1270.48    4903 1269.84  4965.4 1269.59  4994.1 1264.33  5011.2 1265.28
  5013.3 1263.62    5016 1263.12  5024.7 1265.11  5055.3 1269.91  5067.1 1271.22
  5163.8 1269.81  5336.4  1279.3  5432.7 1284.78  5449.6 1287.27  5463.3 1289.31
  5493.9 1289.25  5585.7 1300.88  5663.4 1308.01  5881.2 1313.31  5956.9 1314.38
#Mann= 10 ,-1 , 0
  3194.3     .16       0    4195      .1       0  4498.4     .05       0
  4788.4      .1       0    4903     .16       0  5013.3     .07       0
  5024.7     .16       0  5336.4      .1       0  5449.6     .05       0
  5881.2      .1       0
#XS Ineff= 1 ,-1
 4218.91 4561.06 1274.05
Permanent Ineff=
       F
Bank Sta=4965.4,5055.3
XS Rating Curve= 0 ,0
Exp/Cntr=0.3,0.1

Type RM Length L Ch R = 1 ,8933    ,180,180,180
BEGIN DESCRIPTION:
NORTH CYPRESS CREEK 14.0
END DESCRIPTION:
XS GIS Cut Line= 3
      2923937.45     10128442.58      2923577.21      10127214.3
      2923277.73     10126441.73
#Sta/Elev= 30
  3690.1 1285.19  3915.2  1278.8  4131.2 1275.41  4387.1 1269.76  4460.1 1268.56
  4512.2 1268.91  4591.4 1267.02  4735.5 1266.31  4874.3 1263.73  4939.4 1264.05
  4951.5 1264.06  4967.8 1261.99  4992.2 1260.51  5002.6 1259.79  5008.2  1260.4
  5032.8 1265.44  5062.7 1264.33    5068 1265.34    5078 1265.41  5087.2 1264.49
  5092.6  1266.2  5141.7  1264.1  5231.5 1267.06  5310.5 1267.74    5389 1269.67
  5582.1 1275.21  5593.7 1276.24  5635.7 1276.51  5777.7 1280.84  5798.7 1281.64
#Mann= 4 ,-1 , 0
  3690.1     .05       0  4992.2     .04       0  5008.2     .05       0
  5777.7     .08       0
Bank Sta=4939.4,5032.8
XS Rating Curve= 0 ,0
Exp/Cntr=0.3,0.1

Type RM Length L Ch R = 1 ,8753    ,250,250,250
BEGIN DESCRIPTION:
NORTH CYPRESS CREEK 13.0
END DESCRIPTION:
XS GIS Cut Line= 3
      2924124.07     10128373.11      2923746.48     10127196.94
      2923442.65     10126376.59
#Sta/Elev= 30
  3711.8 1283.29  3810.6 1280.98  3867.6  1280.1    3972 1277.49  4009.3 1275.71
  4049.4 1275.39  4120.8 1275.36  4200.4 1272.61  4334.4 1269.87  4399.9 1267.85
  4514.4 1266.72  4619.5 1265.37    4702 1264.76    4940 1263.47  4993.2 1260.92
  5003.6 1259.96  5025.2 1261.09    5047  1263.5  5072.1 1264.22  5145.9 1263.99
  5163.8 1263.96  5238.4 1263.52  5249.1  1264.3  5398.4 1265.78  5562.1 1270.37
  5642.6 1271.19  5715.9 1273.36  5739.6 1274.37  5758.8 1273.29  5821.9 1274.77
#Mann= 14 ,-1 , 0
  3711.8     .05       0  3810.6     .08       0  3867.6     .05       0
  4049.4     .08       0  4200.4     .05       0  4334.4     .08       0
  4514.4     .05       0  4619.5     .08       0    4702     .05       0
  4993.2     .04       0  5025.2     .05       0  5145.9      .1       0
  5163.8     .05       0  5715.9     .08       0
Bank Sta=4940,5072.1
XS Rating Curve= 0 ,0
Exp/Cntr=0.3,0.1

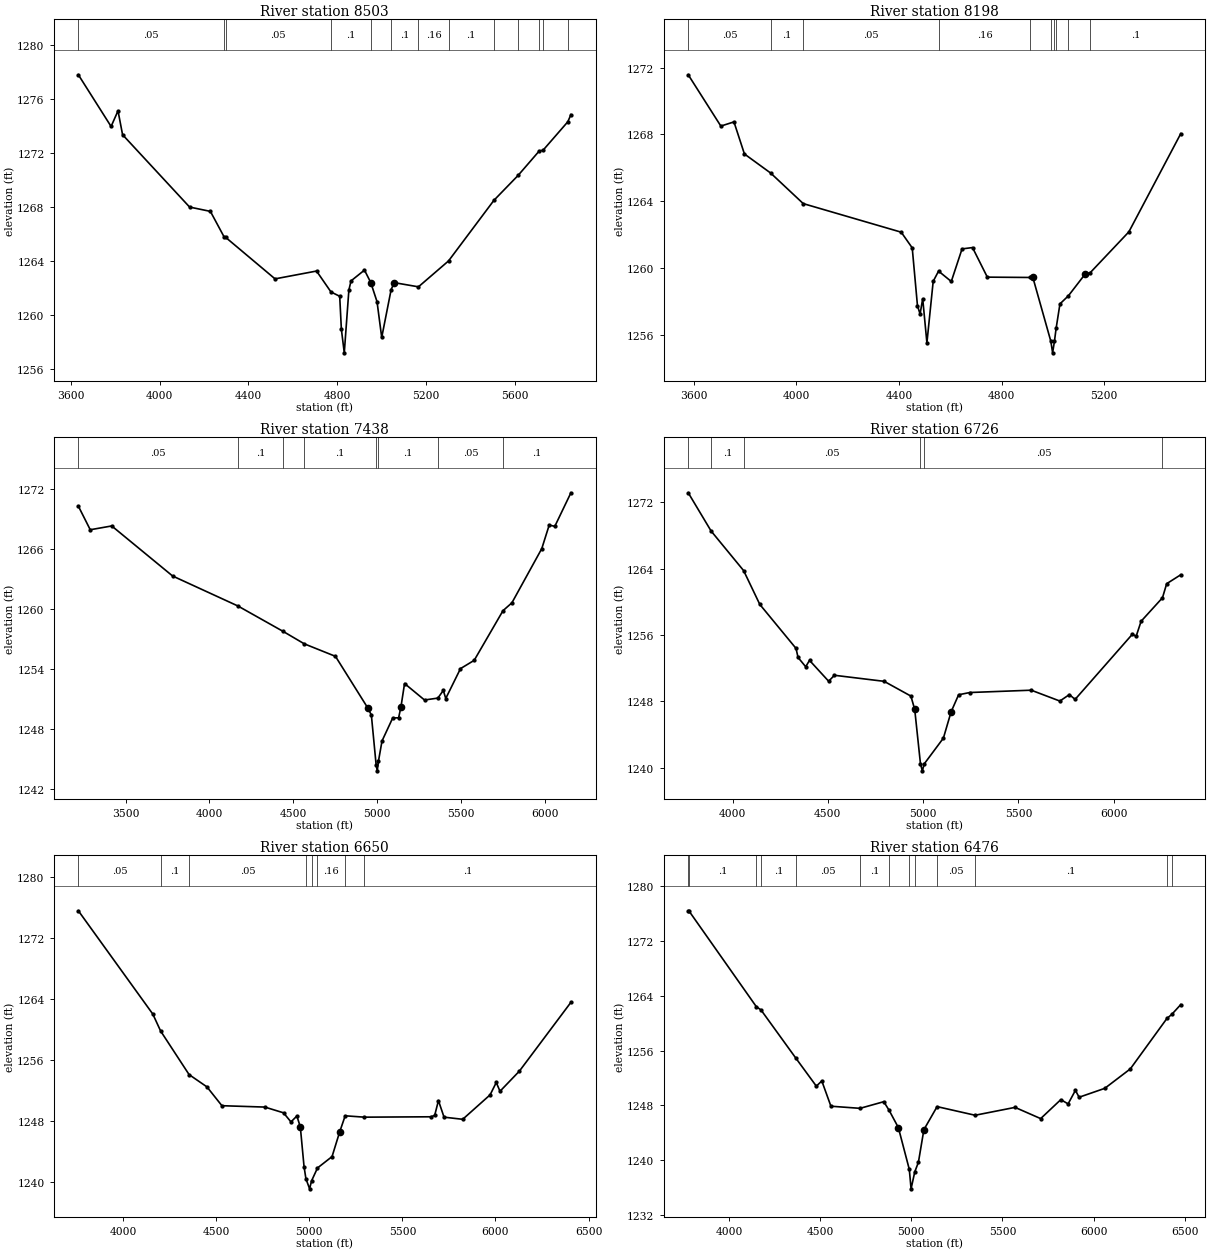
Type RM Length L Ch R = 1 ,8503    ,305,305,305
BEGIN DESCRIPTION:
Mapping XS 6e731e01
END DESCRIPTION:
XS GIS Cut Line= 4
      2924289.49     10128215.47      2923950.96     10127030.63
      2923759.99     10126848.33      2923438.82     10126201.67
#Sta/Elev= 30
  3634.1 1277.83  3781.5    1274  3812.7 1275.16  3833.2 1273.39  4135.1 1268.03
  4228.7 1267.71  4291.1  1265.8  4297.8 1265.78  4519.9 1262.71  4706.8 1263.29
  4771.8 1261.74  4811.1 1261.42  4818.6 1258.98  4831.7 1257.23  4852.4 1261.88
  4862.1 1262.56  4922.6 1263.36  4950.9 1262.44  4979.2 1261.02  5000.3 1258.37
  5042.8 1261.92  5056.9 1262.43  5165.7 1262.12  5301.3 1264.04  5505.7 1268.53
  5614.3 1270.37    5710 1272.19  5726.4 1272.23  5838.5 1274.35  5852.4 1274.88
#Mann= 13 ,-1 , 0
  3634.1     .05       0  4291.1      .1       0  4297.8     .05       0
  4771.8      .1       0  4950.9     .07       0  5042.8      .1       0
  5165.7     .16       0  5301.3      .1       0  5505.7     .05       0
  5614.3      .1       0    5710     .08       0  5726.4     .05       0
  5838.5      .1       0
Bank Sta=4950.9,5056.9
XS Rating Curve= 0 ,0
Exp/Cntr=0.3,0.1

Type RM Length L Ch R = 1 ,8198    ,760,760,760
BEGIN DESCRIPTION:
NORTH CYPRESS CREEK 15.0
END DESCRIPTION:
XS GIS Cut Line= 3
      2924413.36     10127988.18       2924176.3      10126850.3
       2923632.3     10126324.04
#Sta/Elev= 30
  3578.9 1271.57    3706  1268.5  3757.1 1268.75  3797.9 1266.83    3900 1265.69
  4027.1 1263.86  4408.8 1262.15  4451.7 1261.21  4472.1 1257.75  4482.3 1257.25
  4492.5 1258.17  4508.9 1255.53  4533.4 1259.21  4554.3 1259.82  4603.9  1259.2
  4645.8 1261.15  4686.6 1261.23  4744.3 1259.46  4912.1 1259.44    4921 1259.48
  4991.8 1255.62  4998.7 1254.93  5005.9 1255.63  5012.3 1256.39  5027.3 1257.86
    5060 1258.34  5126.3 1259.66  5144.2 1259.71  5295.8 1262.17  5498.1 1268.05
#Mann= 10 ,-1 , 0
  3578.9     .05       0    3900      .1       0  4027.1     .05       0
  4554.3     .16       0  4912.1     .05       0  4991.8    .035       0
  5005.9     .05       0  5012.3      .1       0    5060     .05       0
  5144.2      .1       0
Bank Sta=4921,5126.3
XS Rating Curve= 0 ,0
Exp/Cntr=0.3,0.1

Type RM Length L Ch R = 1 ,7438    ,712,712,712
BEGIN DESCRIPTION:
NORTH CYPRESS CREEK 12.0
END DESCRIPTION:
XS GIS Cut Line= 4
      2924832.42     10127801.09      2924632.77     10126277.67
      2924255.16     10125904.41      2923404.47     10125722.11
#Sta/Elev= 30
  3218.1 1270.33    3289 1267.97  3417.1 1268.35  3780.2 1263.34  4169.6 1260.34
  4439.8 1257.79  4565.6 1256.55  4751.3  1255.3  4944.2 1250.13  4965.4 1249.43
  4993.7 1244.47  5000.5 1243.84  5007.9 1244.82    5029 1246.83  5092.7 1249.13
    5128 1249.15  5142.2 1250.27  5163.4 1252.58  5282.4 1250.93    5362 1251.12
  5394.6 1251.89    5409 1251.08  5496.9 1254.07  5578.7  1254.9  5750.5 1259.87
  5803.7 1260.66  5981.7 1266.08    6026 1268.44  6059.4 1268.31  6155.5 1271.67
#Mann= 8 ,-1 , 0
  3218.1     .05       0  4169.6      .1       0  4439.8     .05       0
  4565.6      .1       0  4993.7     .07       0  5007.9      .1       0
    5362     .05       0  5750.5      .1       0
Bank Sta=4944.2,5142.2
XS Rating Curve= 0 ,0
Exp/Cntr=0.3,0.1

Type RM Length L Ch R = 1 ,6726    ,76,76,76
BEGIN DESCRIPTION:
Mapping XS 64452675
END DESCRIPTION:
XS GIS Cut Line= 3
      2926212.66     10125765.52      2924736.93     10125643.99
      2923634.51     10125600.59
#Sta/Elev= 30
  3767.5 1273.17  3887.7 1268.55  4058.1 1263.78    4143  1259.7  4333.1 1254.39
  4343.6  1253.3  4383.8 1252.18  4403.8 1252.95  4504.2 1250.43  4534.3 1251.15
  4795.2 1250.42  4935.6 1248.64  4955.7 1247.03  4985.8 1240.48  4995.6 1239.62
  5005.9 1240.47  5106.2 1243.57  5146.4 1246.73    5186  1248.8  5244.9 1249.07
  5566.9 1249.35  5717.1 1248.04  5767.1 1248.82  5797.1 1248.24  6097.4  1256.1
  6117.4 1255.86  6143.4 1257.67  6255.4  1260.5  6277.5  1262.2  6351.5 1263.28
#Mann= 6 ,-1 , 0
  3767.5     .16       0  3887.7      .1       0  4058.1     .05       0
  4985.8     .04       0  5005.9     .05       0  6255.4     .08       0
Bank Sta=4955.7,5146.4
XS Rating Curve= 0 ,0
Exp/Cntr=0.3,0.1

Type RM Length L Ch R = 1 ,6650    ,174,174,174
BEGIN DESCRIPTION:
NORTH CYPRESS CREEK 11.0
END DESCRIPTION:
XS GIS Cut Line= 3
      2926247.34     10125683.05      2924745.61     10125574.54
      2923608.45     10125500.76
#Sta/Elev= 30
  3759.9 1275.53  4159.8 1262.01  4201.8 1259.79  4354.6 1254.09  4450.6 1252.48
  4530.8 1250.02  4761.4 1249.84  4861.6 1249.09  4901.7  1247.9  4933.4 1248.67
  4951.9 1247.25  4971.9 1242.05    4982 1240.46  5001.8 1239.14    5012 1240.17
  5044.1 1241.87  5122.3 1243.36  5162.4 1246.53  5192.8  1248.7    5296 1248.52
  5653.5 1248.57  5673.5 1248.75  5693.6 1250.69  5723.7 1248.52  5823.9 1248.24
  5971.1 1251.44  6004.2 1253.06  6024.3 1251.91  6128.5 1254.55  6405.1 1263.55
#Mann= 8 ,-1 , 0
  3759.9     .05       0  4201.8      .1       0  4354.6     .05       0
    4982     .04       0    5012     .05       0  5044.1     .16       0
  5192.8     .05       0    5296      .1       0
Bank Sta=4951.9,5162.4
XS Rating Curve= 0 ,0
Exp/Cntr=0.3,0.1

Type RM Length L Ch R = 1 ,6476    ,77,77,77
BEGIN DESCRIPTION:
NORTH CYPRESS CREEK 10.0
END DESCRIPTION:
XS GIS Cut Line= 3
      2926221.35     10125460.83      2924480.86     10125417.43
      2923522.61     10125330.71
#Sta/Elev= 30
  3775.4 1276.42  3778.8 1276.42  4148.9 1262.42  4175.2 1261.92    4365 1254.93
  4478.5  1250.8  4508.5 1251.56  4558.5 1247.87  4718.3 1247.56  4848.6 1248.53
  4877.5 1247.29  4928.6 1244.75  4988.7 1238.64  4998.4  1235.8  5018.7 1238.28
  5038.7 1239.68  5068.7 1244.44  5141.2 1247.81  5349.8 1246.55    5569  1247.7
  5709.6 1246.06  5820.1 1248.83  5860.2 1248.21  5900.4 1250.19  5920.5 1249.18
  6061.4 1250.48  6201.6 1253.32  6402.8  1260.7  6428.6 1261.27  6478.6 1262.72
#Mann= 13 ,-1 , 0
  3775.4     .16       0  3778.8      .1       0  4148.9     .16       0
  4175.2      .1       0    4365     .05       0  4718.3      .1       0
  4877.5     .16       0  4988.7     .07       0  5018.7     .16       0
  5141.2     .05       0  5349.8      .1       0  6402.8     .16       0
  6428.6      .1       0
Bank Sta=4928.6,5068.7
XS Rating Curve= 0 ,0
Exp/Cntr=0.3,0.1

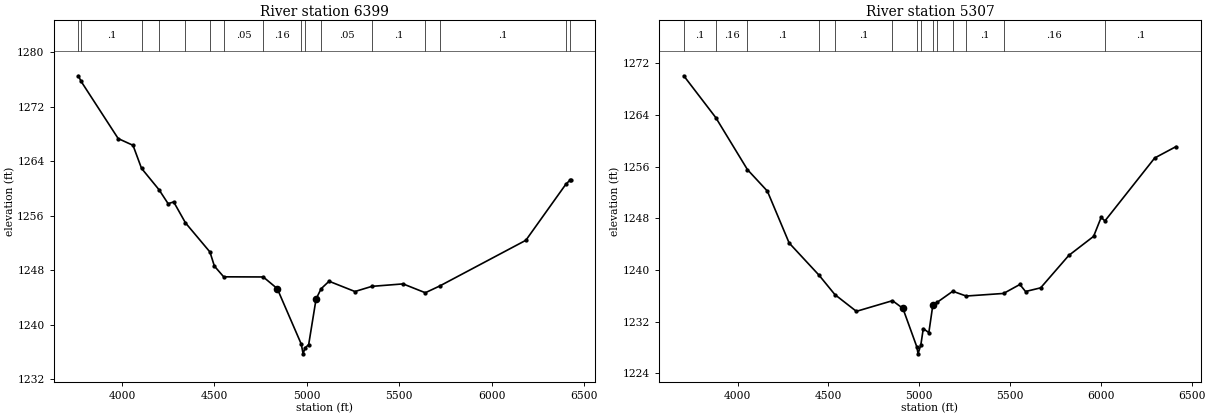
Type RM Length L Ch R = 1 ,6399    ,1092,1092,1092
BEGIN DESCRIPTION:
Mapping XS 8372c964
END DESCRIPTION:
XS GIS Cut Line= 3
      2926203.99     10125400.93      2924502.56     10125348.85
      2923547.73     10125240.35
#Sta/Elev= 30
    3764 1276.56  3779.1 1275.73  3979.6 1267.33  4059.7 1266.34  4105.7 1262.96
  4200.5 1259.81  4249.7 1257.76  4279.8 1258.02  4343.6 1254.94  4475.9 1250.66
  4499.9 1248.59  4550.3 1247.01  4764.3 1246.99    4840 1245.28  4970.1 1237.11
  4979.8 1235.69  4990.1 1236.54  5010.1 1237.06  5050.1 1243.76  5077.4 1245.26
  5120.2 1246.36  5260.2 1244.85  5352.3 1245.61  5520.7 1245.97  5640.9 1244.67
  5718.7 1245.66  6184.9 1252.38  6401.8 1260.64  6424.8 1261.24  6427.2 1261.24
#Mann= 16 ,-1 , 0
    3764     .16       0  3779.1      .1       0  4105.7     .16       0
  4200.5      .1       0  4343.6     .05       0  4475.9      .1       0
  4550.3     .05       0  4764.3     .16       0  4970.1     .07       0
  4990.1     .16       0  5077.4     .05       0  5352.3      .1       0
  5640.9     .16       0  5718.7      .1       0  6401.8     .16       0
  6424.8      .1       0
Bank Sta=4840,5050.1
XS Rating Curve= 0 ,0
Exp/Cntr=0.3,0.1

Type RM Length L Ch R = 1 ,5307    ,627,627,627
BEGIN DESCRIPTION:
NORTH CYPRESS CREEK 8.0
END DESCRIPTION:
XS GIS Cut Line= 4
      2926108.43     10124215.17      2925079.82     10124249.89
      2924585.02     10124475.59      2923492.38     10124792.11
#Sta/Elev= 30
  3703.7 1270.05  3879.6 1263.59  4054.4 1255.52  4163.9  1252.2    4284 1244.16
  4448.7 1239.17  4535.9 1236.17  4654.2 1233.58    4853 1235.23  4910.2 1234.04
  4987.2 1228.06  4993.7    1227  5009.2 1228.41  5022.5 1230.91  5053.1 1230.28
  5074.3  1234.4  5075.1 1234.59    5098 1234.96  5184.9 1236.69  5258.5 1235.95
  5464.5 1236.35  5554.3 1237.74  5585.5 1236.65  5668.8 1237.22  5823.4 1242.23
  5960.3 1245.19  6001.8 1248.12  6022.7 1247.58  6296.5 1257.32  6414.3 1259.09
#Mann= 14 ,-1 , 0
  3703.7      .1       0  3879.6     .16       0  4054.4      .1       0
  4448.7     .16       0  4535.9      .1       0    4853     .16       0
  4987.2     .07       0  5009.2     .16       0  5074.3     .05       0
    5098      .1       0  5184.9     .05       0  5258.5      .1       0
  5464.5     .16       0  6022.7      .1       0
Bank Sta=4910.2,5075.1
XS Rating Curve= 0 ,0
Exp/Cntr=0.3,0.1