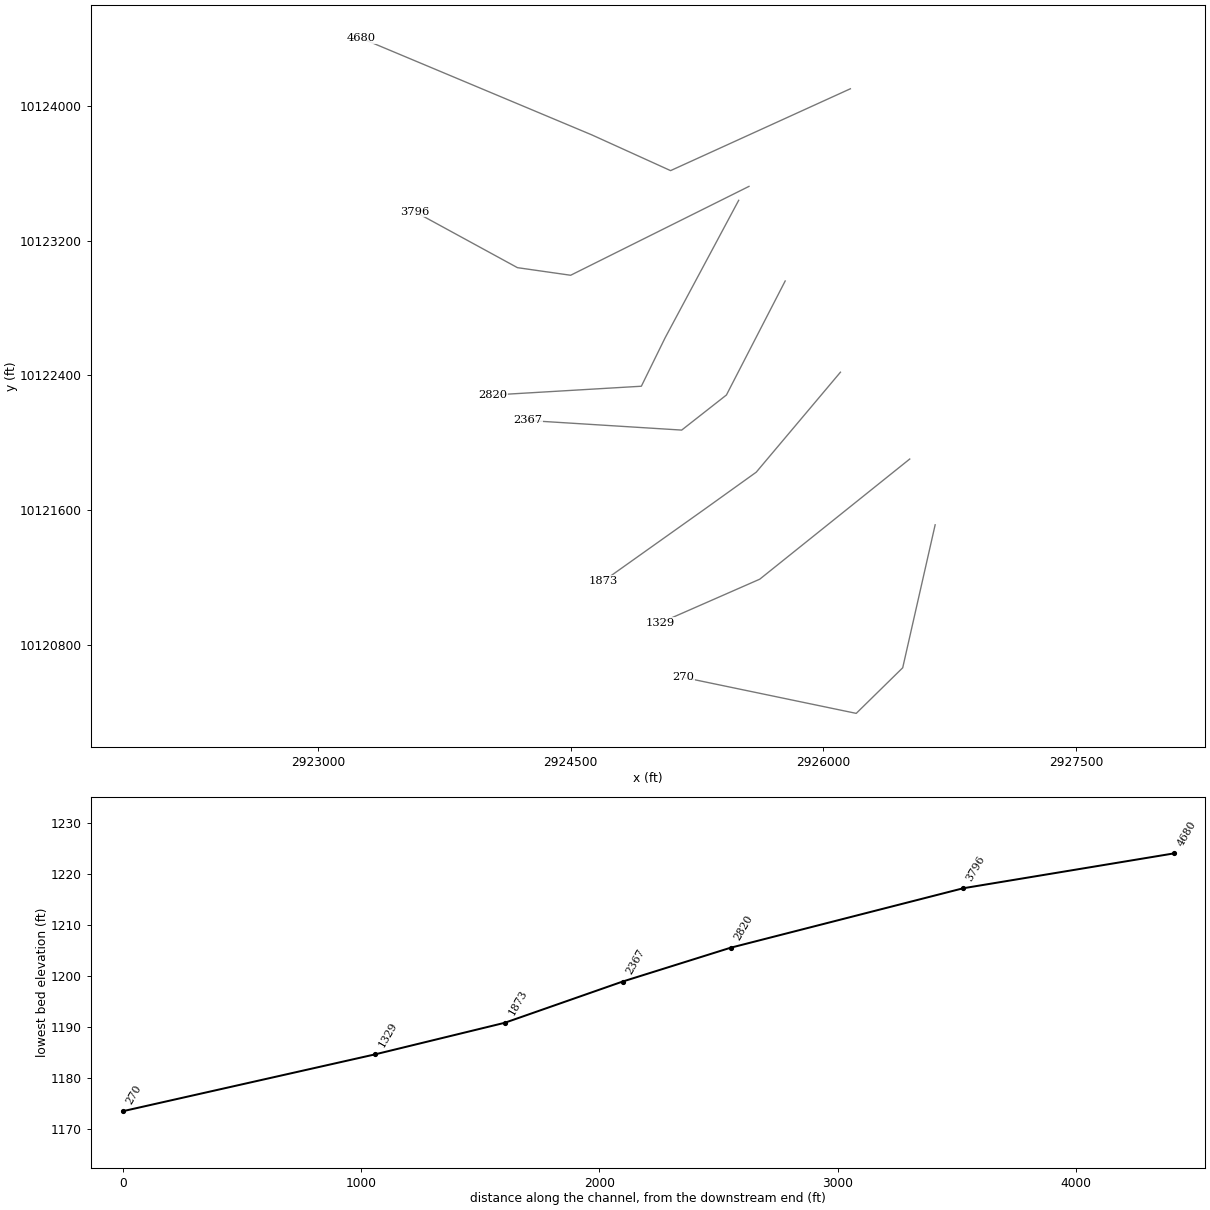
HEC-RAS study NORTH CYPRESS CREEK.prj: NORTH CYPRESS CREEK Base Level Engineering

--- NORTH CYPRESS CREEK.g01 (geometry) --- (continued)

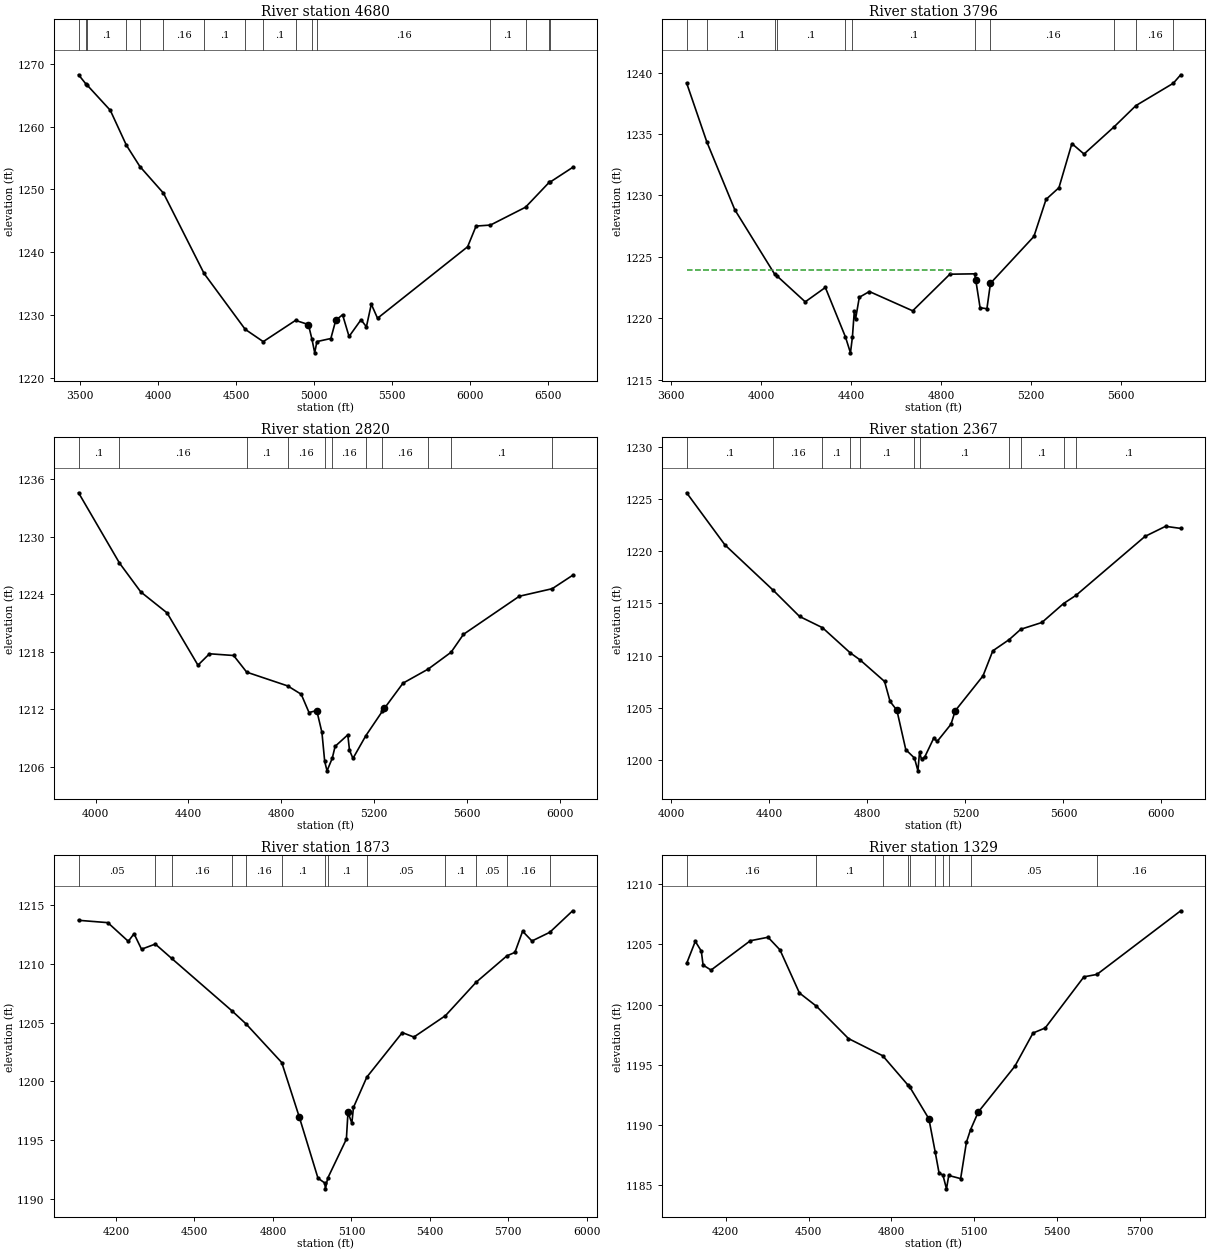
Type RM Length L Ch R = 1 ,4680    ,884,884,884
BEGIN DESCRIPTION:
NORTH CYPRESS CREEK 7.0
END DESCRIPTION:
XS GIS Cut Line= 4
      2926160.51     10124102.31      2925092.84     10123616.21
      2924624.09     10123828.89      2923256.93     10124401.79
#Sta/Elev= 30
  3489.2 1268.23  3535.8 1266.79  3543.5 1266.61  3692.8 1262.58    3796 1257.03
  3882.8 1253.64  4033.8 1249.41  4294.6 1236.63  4558.3 1227.75  4674.2 1225.79
  4881.4 1229.17    4964 1228.51  4987.1 1226.14  5004.4 1224.01  5018.5  1225.8
    5108 1226.29  5139.3 1229.18  5183.2 1230.07  5224.8 1226.61  5301.5 1229.27
  5336.1 1228.15  5367.5 1231.75  5407.5 1229.51  5985.5 1240.88  6039.7 1244.17
  6131.9 1244.33  6357.1 1247.17  6509.8 1251.15  6515.8 1251.18  6659.4  1253.5
#Mann= 16 ,-1 , 0
  3489.2      .1       0  3535.8     .16       0  3543.5      .1       0
    3796     .16       0  3882.8      .1       0  4033.8     .16       0
  4294.6      .1       0  4558.3     .16       0  4674.2      .1       0
  4881.4     .16       0  4987.1     .07       0  5018.5     .16       0
  6131.9      .1       0  6357.1     .16       0  6509.8      .1       0
  6515.8     .16       0
Bank Sta=4964,5139.3
XS Rating Curve= 0 ,0
Exp/Cntr=0.3,0.1

Type RM Length L Ch R = 1 ,3796    ,976,976,976
BEGIN DESCRIPTION:
Mapping XS ba972597
END DESCRIPTION:
XS GIS Cut Line= 4
      2925558.46     10123522.64      2924499.39     10122994.84
      2924183.42     10123039.98      2923572.91     10123372.98
#Sta/Elev= 30
    3668 1239.15  3757.6 1234.37  3882.2 1228.84    4059 1223.61  4070.4 1223.44
  4195.6 1221.34  4285.1 1222.51  4374.6 1218.48  4396.8 1217.19  4405.4 1218.45
  4413.8 1220.56  4419.4 1219.93  4436.2 1221.71  4480.9 1222.18  4673.6 1220.61
  4839.1 1223.59  4948.9 1223.62  4953.9 1223.15  4973.5 1220.86  5003.8 1220.78
  5019.6 1222.85  5212.8 1226.66  5266.9 1229.68  5324.2 1230.63  5381.8 1234.22
  5435.9 1233.37  5571.1 1235.61  5666.5 1237.31  5832.9 1239.13  5865.9 1239.82
#Mann= 11 ,-1 , 0
    3668     .16       0  3757.6      .1       0    4059     .16       0
  4070.4      .1       0  4374.6     .07       0  4405.4      .1       0
  4948.9     .05       0  5019.6     .16       0  5571.1      .1       0
  5666.5     .16       0  5832.9      .1       0
#XS Ineff= 2 , 0
         4844.36  1223.9
Permanent Ineff=
       F       F
Bank Sta=4953.9,5019.6
XS Rating Curve= 0 ,0
Exp/Cntr=0.3,0.1

Type RM Length L Ch R = 1 ,2820    ,453,453,453
BEGIN DESCRIPTION:
NORTH CYPRESS CREEK 5.0
END DESCRIPTION:
XS GIS Cut Line= 4
      2925497.33     10123439.96      2925059.85     10122622.29
      2924919.23     10122335.83      2924039.03     10122283.75
#Sta/Elev= 30
  3926.8  1234.6    4103 1227.26  4194.9 1224.24  4308.1 1222.05  4441.1 1216.59
  4490.7 1217.78  4594.7  1217.6    4651 1215.86  4827.8 1214.42  4885.9 1213.55
  4919.5 1211.64  4952.8 1211.85  4975.1 1209.56    4987 1206.53  4997.1 1205.55
  5019.6 1206.87  5031.9 1208.11  5086.5 1209.31  5093.8  1207.7  5108.8 1206.85
  5163.9 1209.21  5235.5 1211.78  5244.2 1212.08  5324.3 1214.71  5432.7 1216.18
  5531.4 1217.94  5584.7 1219.81  5825.2 1223.79  5967.1 1224.58    6055 1225.98
#Mann= 11 ,-1 , 0
  3926.8      .1       0    4103     .16       0    4651      .1       0
  4827.8     .16       0    4987     .07       0  5019.6     .16       0
  5163.9      .1       0  5235.5     .16       0  5432.7     .05       0
  5531.4      .1       0  5967.1     .05       0
Bank Sta=4952.8,5244.2
XS Rating Curve= 0 ,0
Exp/Cntr=0.3,0.1

Type RM Length L Ch R = 1 ,2367    ,494,494,494
BEGIN DESCRIPTION:
NORTH CYPRESS CREEK 4.0
END DESCRIPTION:
XS GIS Cut Line= 4
      2925773.41     10122960.87      2925424.43     10122283.75
      2925158.81     10122075.41      2924242.84     10122132.66
#Sta/Elev= 30
  4061.8 1225.62  4218.1 1220.62  4415.9 1216.25  4522.8 1213.75  4616.4 1212.67
  4729.5 1210.26  4769.3 1209.59  4869.9 1207.51  4892.4 1205.59  4920.1 1204.75
  4956.6 1200.96  4991.9 1200.16  5006.1 1198.93  5012.7 1200.73  5020.8 1200.03
  5034.5 1200.29  5070.5 1202.06    5085 1201.76    5141  1203.4  5158.5  1204.7
  5271.7 1208.04  5311.8 1210.45  5378.8 1211.53  5426.1 1212.52  5512.2 1213.17
  5600.7 1214.99  5651.6 1215.78    5933 1221.43    6017  1222.4  6078.9  1222.2
#Mann= 11 ,-1 , 0
  4061.8      .1       0  4415.9     .16       0  4616.4      .1       0
  4729.5     .16       0  4769.3      .1       0  4991.9     .07       0
  5012.7      .1       0  5378.8     .16       0  5426.1      .1       0
  5600.7     .05       0  5651.6      .1       0
Bank Sta=4920.1,5158.5
XS Rating Curve= 0 ,0
Exp/Cntr=0.3,0.1

Type RM Length L Ch R = 1 ,1873    ,544,544,544
BEGIN DESCRIPTION:
NORTH CYPRESS CREEK 3.0
END DESCRIPTION:
XS GIS Cut Line= 4
      2926101.54     10122419.19      2925601.52     10121825.41
      2925289.02     10121601.45      2924695.26     10121179.58
#Sta/Elev= 30
  4056.9 1213.71  4168.9 1213.51  4247.1 1211.92    4269 1212.57  4297.6 1211.25
  4350.3 1211.69  4412.3 1210.48  4643.4 1206.01  4697.2  1204.9  4833.8 1201.61
  4900.4 1197.01  4972.3 1191.78  4998.1 1191.37  5000.8 1190.87  5009.2 1191.76
  5080.9  1195.1    5087 1197.39  5101.8 1196.45  5107.9 1197.79    5159 1200.37
  5294.7 1204.16    5339 1203.78  5459.7  1205.6  5577.3 1208.45  5694.8 1210.69
  5725.2 1210.98  5754.7 1212.78  5790.4 1211.95  5858.6 1212.69    5946 1214.52
#Mann= 13 ,-1 , 0
  4056.9     .05       0  4350.3      .1       0  4412.3     .16       0
  4643.4      .1       0  4697.2     .16       0  4833.8      .1       0
  4998.1     .07       0  5009.2      .1       0    5159     .05       0
  5459.7      .1       0  5577.3     .05       0  5694.8     .16       0
  5858.6      .1       0
Bank Sta=4900.4,5087
XS Rating Curve= 0 ,0
Exp/Cntr=0.3,0.1

Type RM Length L Ch R = 1 ,1329    ,1059,1059,1059
BEGIN DESCRIPTION:
NORTH CYPRESS CREEK 2.0
END DESCRIPTION:
XS GIS Cut Line= 3
      2926513.01     10121903.56      2925622.35       10121190.
       2925028.6     10120929.58
#Sta/Elev= 30
  4058.3 1203.42  4089.7 1205.26  4111.5 1204.45  4117.9 1203.29  4146.7 1202.87
  4289.1 1205.31  4353.2  1205.6  4396.4 1204.55  4466.8 1200.97  4528.4 1199.87
  4644.5 1197.18  4768.6 1195.75  4860.5  1193.3  4866.1 1193.17  4935.8 1190.51
  4958.6 1187.76  4972.6 1186.01  4986.7 1185.83  4999.5 1184.69  5007.8  1185.8
  5050.8 1185.54  5071.8 1188.57  5086.6  1189.6  5114.8 1191.08  5247.2 1194.88
    5313 1197.64  5357.1 1198.06  5497.3 1202.31  5544.4 1202.51  5847.9  1207.8
#Mann= 10 ,-1 , 0
  4058.3     .16       0  4528.4      .1       0  4768.6     .16       0
  4860.5      .1       0  4866.1     .16       0  4958.6      .1       0
  4986.7     .07       0  5007.8      .1       0  5086.6     .05       0
  5544.4     .16       0
Bank Sta=4935.8,5114.8
XS Rating Curve= 0 ,0
Exp/Cntr=0.3,0.1

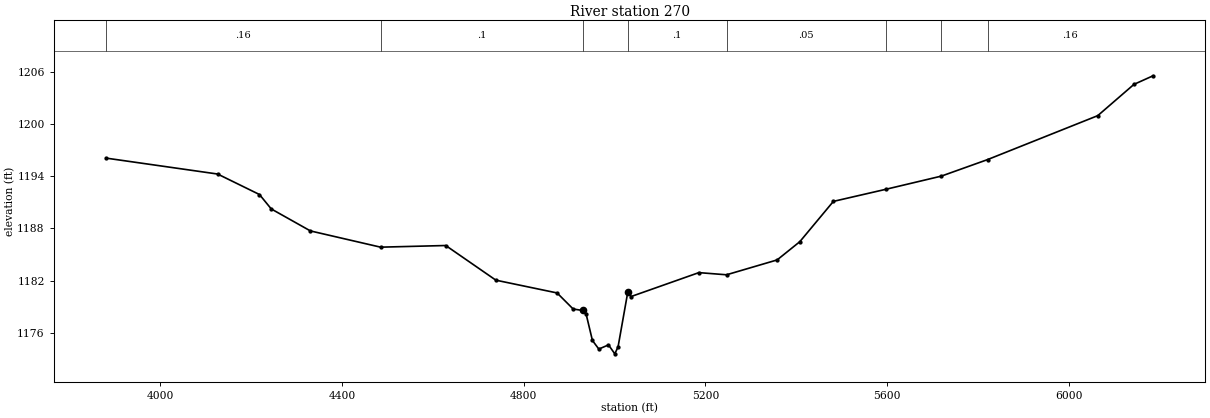
Type RM Length L Ch R = 1 ,270     ,0,0,0
BEGIN DESCRIPTION:
NORTH CYPRESS CREEK 1.0
END DESCRIPTION:
XS GIS Cut Line= 4
      2926664.01      10121512.9      2926471.31     10120663.95
      2926195.27     10120393.12      2925169.21     10120606.67
#Sta/Elev= 30
  3880.5 1196.09  4125.8 1194.26    4218  1191.9    4244 1190.24  4330.2 1187.71
  4484.7 1185.84  4628.2 1186.03  4738.6 1182.04  4873.4 1180.57  4908.8 1178.72
    4930 1178.55  4937.1 1178.19  4951.2  1175.1  4965.3 1174.11  4986.6 1174.59
  5000.5 1173.56  5007.7 1174.37    5029 1180.65    5036 1180.15  5185.6 1182.91
  5246.5 1182.66  5357.9 1184.37  5407.9 1186.47  5481.8 1191.11    5598 1192.51
  5719.6 1194.02  5821.3 1195.92    6064 1200.98  6143.7 1204.58  6185.8 1205.57
#Mann= 8 ,-1 , 0
  3880.5     .16       0  4484.7      .1       0    4930     .07       0
    5029      .1       0  5246.5     .05       0    5598      .1       0
  5719.6     .05       0  5821.3     .16       0
Bank Sta=4930,5029
XS Rating Curve= 0 ,0
Exp/Cntr=0.3,0.1

Chan Stop Cuts=-1
Use User Specified Reach Order=0
Composite Channel Slope=5