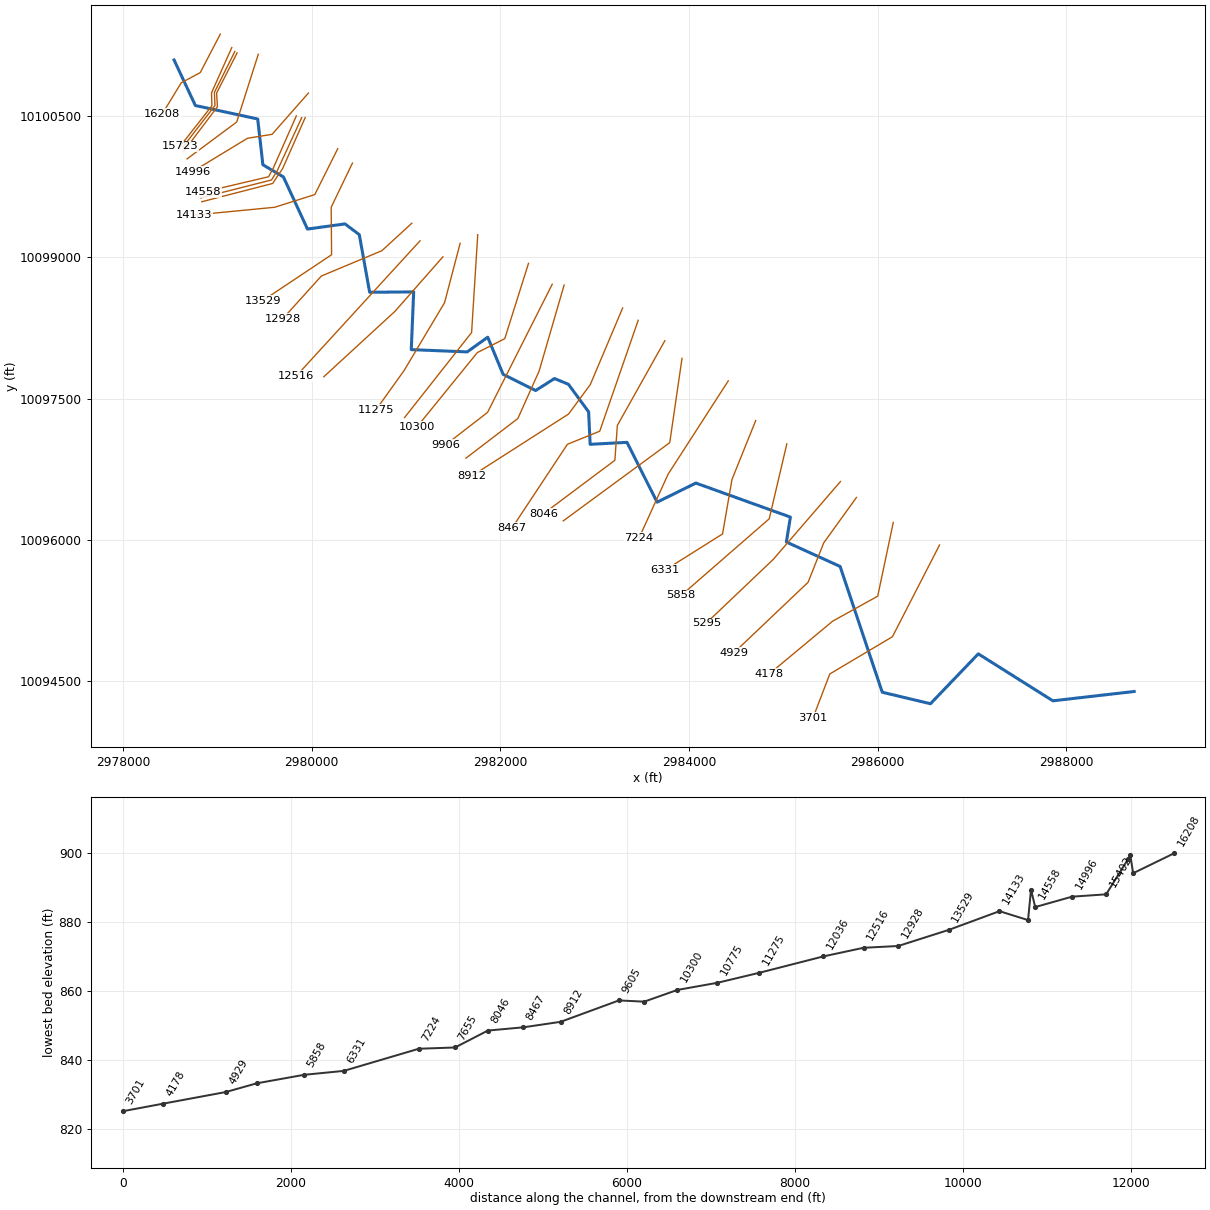
--- PEDERNALES TRIB 1.prj (project) ---

Proj Title=PEDERNALES TRIB 1 Base Level Engineering
Current Plan=p01
Default Exp/Contr=0.3,0.1
English Units
Geom File=g01
Flow File=f01
Plan File=p01
BEGIN DESCRIPTION:
PEDERNALES TRIB 1
END DESCRIPTION:

--- PEDERNALES TRIB 1.p01 (plan) ---

Plan Title=Multiple Run
Short Identifier=Multiple
Geom File=g01
Flow File=f01
Subcritical Flow
K Sum by GR= 0
Std Step Tol= 0.01
Critical Tol= 0.01
Num of Std Step Trials= 20
Max Error Tol= 0.3
Flow Tol Ratio= 0.001
Split Flow NTrial= 30
Split Flow Tol= 0.02
Split Flow Ratio= 0.02
Log Output Level= 0
Friction Slope Method= 1
Unsteady Friction Slope Method= 2
Unsteady Bridges Friction Slope Method= 1
Parabolic Critical Depth
Global Vel Dist=  1 , 1 , 1
Global Log Level= 0
CheckData=True
Encroach Param= -1, 0, 0, 0
BEGIN DESCRIPTION:
Multiple Run
END DESCRIPTION:

--- PEDERNALES TRIB 1.f01 (steady flow) ---

Flow Title=Multiple
Number of Profiles=7
Profile Names=10-year,25-year,50-year,1pct_min,100-year,1pct_plu,500-year
River Rch & RM= PEDERNALES TRIB ,Reach-1,16208
     627     879    1089     989    1337    1808    2020
River Rch & RM= PEDERNALES TRIB ,Reach-1,13529
     948    1353    1699    1558    2108    2850    3256
River Rch & RM= PEDERNALES TRIB ,Reach-1,7655
    1343    1970    2519    2353    3182    4303    5097
Boundary for River Rch & Prof#=PEDERNALES TRIB ,Reach-1,1
Up Type=0
Dn Type=3
Dn Slope=0.005
Boundary for River Rch & Prof#=PEDERNALES TRIB ,Reach-1,2
Up Type=0
Dn Type=3
Dn Slope=0.005
Boundary for River Rch & Prof#=PEDERNALES TRIB ,Reach-1,3
Up Type=0
Dn Type=3
Dn Slope=0.005
Boundary for River Rch & Prof#=PEDERNALES TRIB ,Reach-1,4
Up Type=0
Dn Type=3
Dn Slope=0.005
Boundary for River Rch & Prof#=PEDERNALES TRIB ,Reach-1,5
Up Type=0
Dn Type=3
Dn Slope=0.005
Boundary for River Rch & Prof#=PEDERNALES TRIB ,Reach-1,6
Up Type=0
Dn Type=3
Dn Slope=0.005
Boundary for River Rch & Prof#=PEDERNALES TRIB ,Reach-1,7
Up Type=0
Dn Type=3
Dn Slope=0.005

--- PEDERNALES TRIB 1.g01 (geometry) ---

Geom Title=Existing Conditions

River Reach=PEDERNALES TRIB ,Reach-1
Reach XY= 30
      2978541.20     10101089.18      2978766.68     10100606.54
      2979427.70     10100463.65      2979482.69     10099978.40
      2979699.96     10099849.64      2979955.45     10099296.79
      2980352.99     10099351.28      2980504.81     10099237.45
      2980614.53     10098626.70      2981081.26     10098630.35
      2981055.71     10098018.43      2981648.80     10097994.44
      2981866.35     10098150.34      2982029.56     10097756.47
      2982374.49     10097584.88      2982574.23     10097711.85
      2982722.27     10097650.80      2982936.30     10097358.57
      2982952.19     10097014.52      2983342.96     10097035.32
      2983662.08     10096401.04      2984073.15     10096603.52
      2985075.46     10096242.99      2985032.57     10095978.87
      2985602.44     10095719.58      2986049.26     10094386.08
      2986560.29     10094264.20      2987067.49     10094793.01
      2987857.96     10094295.17      2988720.23     10094394.08

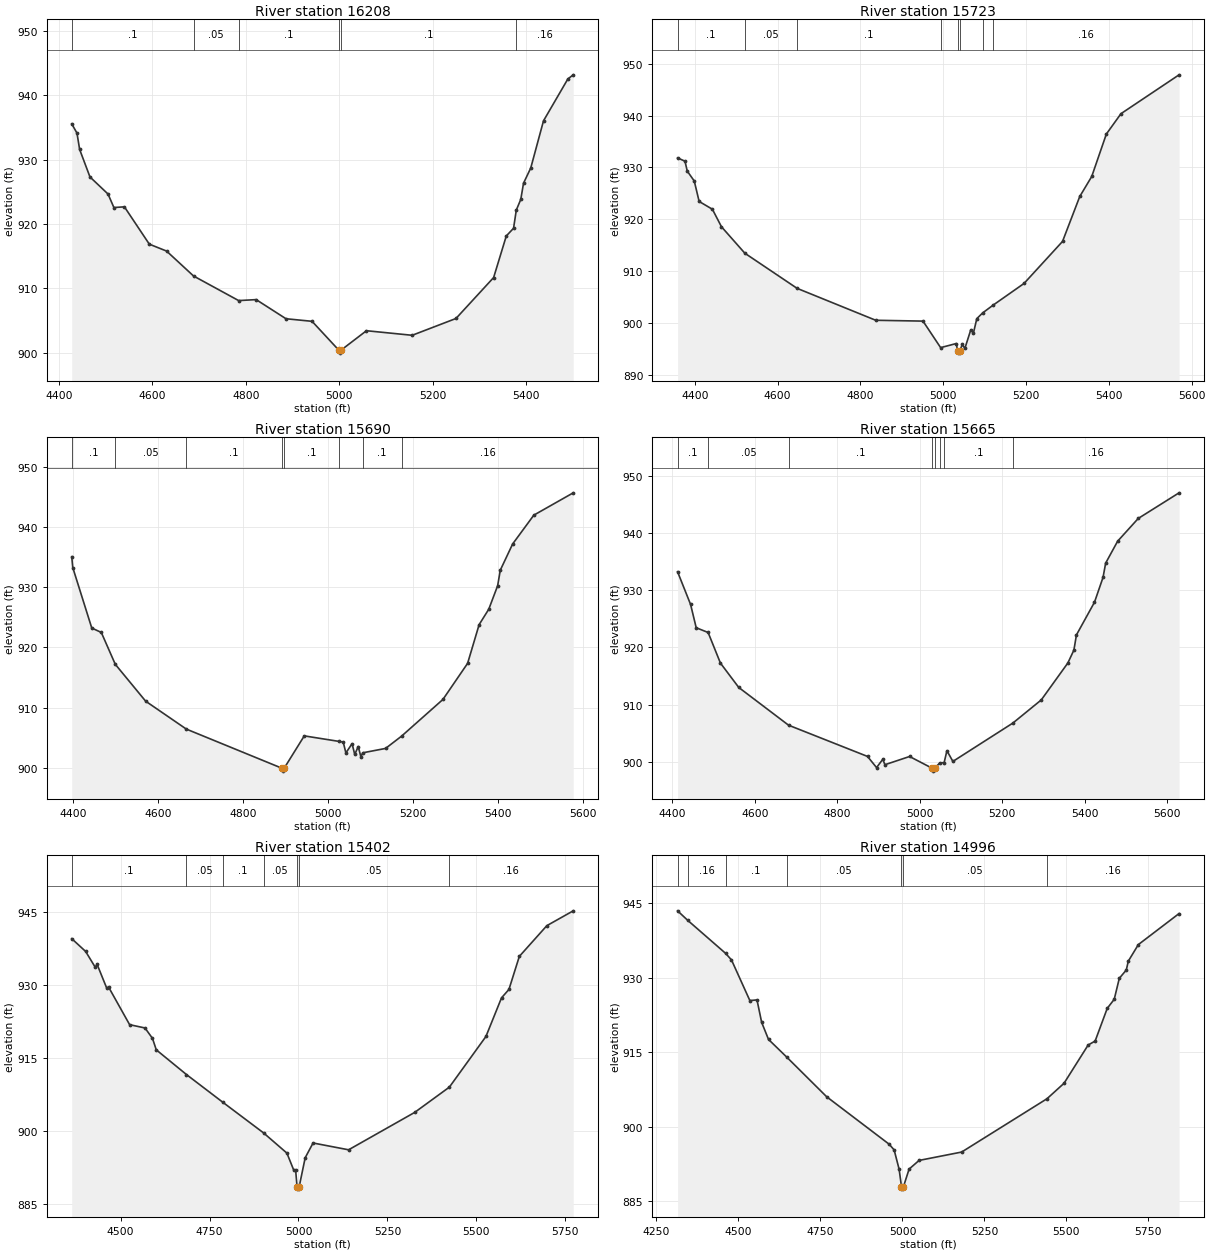
Type RM Length L Ch R = 1,16208,485,485,485
BEGIN DESCRIPTION:
PEDERNALES TRIB 1 35.0
END DESCRIPTION:
XS GIS Cut Line= 4
      2979031.33     10101363.68      2978818.65     10100955.67
      2978616.82     10100847.16      2978417.16     10100519.46
#Sta/Elev= 30
  4427.4  935.54  4438.6  934.10  4444.3  931.56  4466.4  927.29  4505.0  924.64
  4517.6  922.54  4540.1  922.65  4593.4  916.85  4630.3  915.78  4688.0  911.91
  4784.5  908.09  4822.0  908.24  4885.8  905.27  4941.6  904.87  4998.3  900.43
  5001.0  899.93  5004.3  900.43  5058.0  903.41  5155.8  902.70  5249.5  905.31
  5330.1  911.67  5357.2  918.13  5372.7  919.32  5378.6  922.15  5388.2  923.81
  5394.0  926.31  5409.5  928.68  5436.8  936.01  5488.9  942.51  5500.4  943.15
#Mann=6,-1,0
  4427.4     0.1       0  4688.0    0.05       0  4784.5     0.1       0
  4998.3    0.07       0  5004.3     0.1       0  5378.6    0.16       0
Bank Sta=4998.3,5004.3
Exp/Cntr=0.3,0.1

Type RM Length L Ch R = 1,15723,33,33,33
BEGIN DESCRIPTION:
Mapping XS 7b7ec91e
END DESCRIPTION:
XS GIS Cut Line= 4
      2979152.87     10101220.47      2978938.00     10100740.83
      2978942.34     10100604.11      2978603.80     10100172.25
#Sta/Elev= 30
  4358.6  931.85  4376.5  931.21  4382.0  929.30  4398.9  927.39  4410.7  923.44
  4442.7  921.94  4464.6  918.56  4521.1  913.45  4647.3  906.67  4837.2  900.51
  4951.3  900.35  4993.9  895.23  5031.6  896.02  5034.9  894.67  5037.7  894.17
  5040.9  894.67  5046.0  895.85  5052.4  895.08  5066.8  898.68  5073.2  898.08
  5081.3  900.83  5095.8  901.96  5120.8  903.44  5195.2  907.61  5288.3  915.73
  5329.9  924.40  5358.8  928.26  5394.1  936.45  5429.4  940.38  5569.7  947.88
#Mann=8,-1,0
  4358.6     0.1       0  4521.1    0.05       0  4647.3     0.1       0
  4993.9    0.16       0  5034.9    0.07       0  5040.9    0.16       0
  5095.8     0.1       0  5120.8    0.16       0
Bank Sta=5034.9,5040.9
Exp/Cntr=0.3,0.1

Type RM Length L Ch R = 1,15690,25,25,25
BEGIN DESCRIPTION:
Mapping XS 2fb03ffe
END DESCRIPTION:
XS GIS Cut Line= 4
      2979185.40     10101179.19      2978968.39     10100745.17
      2978974.90     10100606.28      2978635.36     10100167.25
#Sta/Elev= 30
  4396.9  935.12  4399.3  933.32  4444.0  923.24  4466.4  922.51  4499.3  917.20
  4570.7  911.06  4666.4  906.41  4890.6  899.91  4893.4  899.41  4896.6  899.91
  4943.7  905.28  5025.5  904.36  5035.3  904.25  5041.6  902.44  5056.1  903.98
  5062.4  902.19  5070.6  903.51  5076.9  901.78  5081.1  902.46  5134.9  903.19
  5172.4  905.23  5269.8  911.35  5327.8  917.36  5354.9  923.81  5377.6  926.38
  5398.4  930.28  5404.7  932.88  5433.7  937.24  5483.5  942.04  5576.2  945.76
#Mann=8,-1,0
  4396.9     0.1       0  4499.3    0.05       0  4666.4     0.1       0
  4890.6    0.07       0  4896.6     0.1       0  5025.5    0.16       0
  5081.1     0.1       0  5172.4    0.16       0
Bank Sta=4890.6,4896.6
Exp/Cntr=0.3,0.1

Type RM Length L Ch R = 1,15665,263,263,263
BEGIN DESCRIPTION:
Mapping XS f558a8ca
END DESCRIPTION:
XS GIS Cut Line= 4
      2979209.29     10101164.04      2978992.26     10100738.66
      2979000.94     10100593.26      2978643.18     10100120.59
#Sta/Elev= 30
  4412.9  933.25  4444.5  927.52  4458.1  923.45  4487.0  922.62  4516.8  917.27
  4561.3  913.00  4682.0  906.40  4873.5  900.93  4895.4  898.98  4910.6  900.44
  4915.6  899.48  4975.5  900.92  5030.4  898.86  5033.1  898.36  5036.4  898.86
  5048.4  899.78  5059.3  899.86  5066.0  901.93  5080.5  900.06  5225.9  906.77
  5294.8  910.82  5359.3  917.29  5373.9  919.54  5380.1  922.20  5423.8  927.91
  5444.6  932.27  5450.9  934.76  5480.0  938.60  5530.0  942.58  5628.9  947.06
#Mann=8,-1,0
  4412.9     0.1       0  4487.0    0.05       0  4682.0     0.1       0
  5030.4    0.07       0  5036.4     0.1       0  5048.4    0.16       0
  5059.3     0.1       0  5225.9    0.16       0
Bank Sta=5030.4,5036.4
Exp/Cntr=0.3,0.1

Type RM Length L Ch R = 1,15402,406,406,406
BEGIN DESCRIPTION:
Mapping XS 486a8e22
END DESCRIPTION:
XS GIS Cut Line= 3
      2979434.08     10101149.95      2979204.91     10100431.17
      2978678.90     10100040.57
#Sta/Elev= 30
  4362.7  939.51  4401.8  936.88  4428.8  933.63  4434.0  934.23  4461.0  929.35
  4466.2  929.57  4525.4  921.84  4568.6  921.16  4589.6  919.03  4600.3  916.67
  4685.2  911.59  4786.6  905.94  4901.9  899.60  4967.5  895.45  4986.7  891.95
  4992.0  891.99  4996.0  888.55  4998.7  888.05  5002.0  888.55  5018.9  894.50
  5041.0  897.53  5140.9  896.13  5326.6  903.81  5424.2  909.01  5526.9  919.41
  5570.7  927.35  5591.6  929.08  5620.8  935.87  5698.1  942.18  5772.3  945.23
#Mann=7,-1,0
  4362.7     0.1       0  4685.2    0.05       0  4786.6     0.1       0
  4901.9    0.05       0  4996.0   0.035       0  5002.0    0.05       0
  5424.2    0.16       0
Bank Sta=4996,5002
Exp/Cntr=0.3,0.1

Type RM Length L Ch R = 1,14996,438,438,438
BEGIN DESCRIPTION:
PEDERNALES TRIB 1 34.0
END DESCRIPTION:
XS GIS Cut Line= 4
      2979965.30     10100738.44      2979579.91     10100300.96
      2979319.49     10100259.29      2978736.14     10099905.12
#Sta/Elev= 30
  4314.3  943.51  4345.3  941.59  4460.8  934.93  4478.7  933.61  4534.7  925.41
  4556.5  925.54  4570.7  921.01  4591.6  917.57  4646.6  914.04  4769.0  906.00
  4959.5  896.43  4974.7  895.28  4989.9  891.38  4997.1  887.87  4999.8  887.37
  5003.1  887.87  5020.3  891.41  5050.7  893.16  5180.6  894.85  5440.7  905.60
  5492.7  908.72  5566.3  916.44  5587.6  917.24  5624.5  923.84  5645.8  925.66
  5661.3  929.90  5682.6  931.57  5688.7  933.36  5719.4  936.70  5843.5  942.96
#Mann=7,-1,0
  4314.3     0.1       0  4345.3    0.16       0  4460.8     0.1       0
  4646.6    0.05       0  4997.1   0.035       0  5003.1    0.05       0
  5440.7    0.16       0
Bank Sta=4997.1,5003.1
Exp/Cntr=0.3,0.1

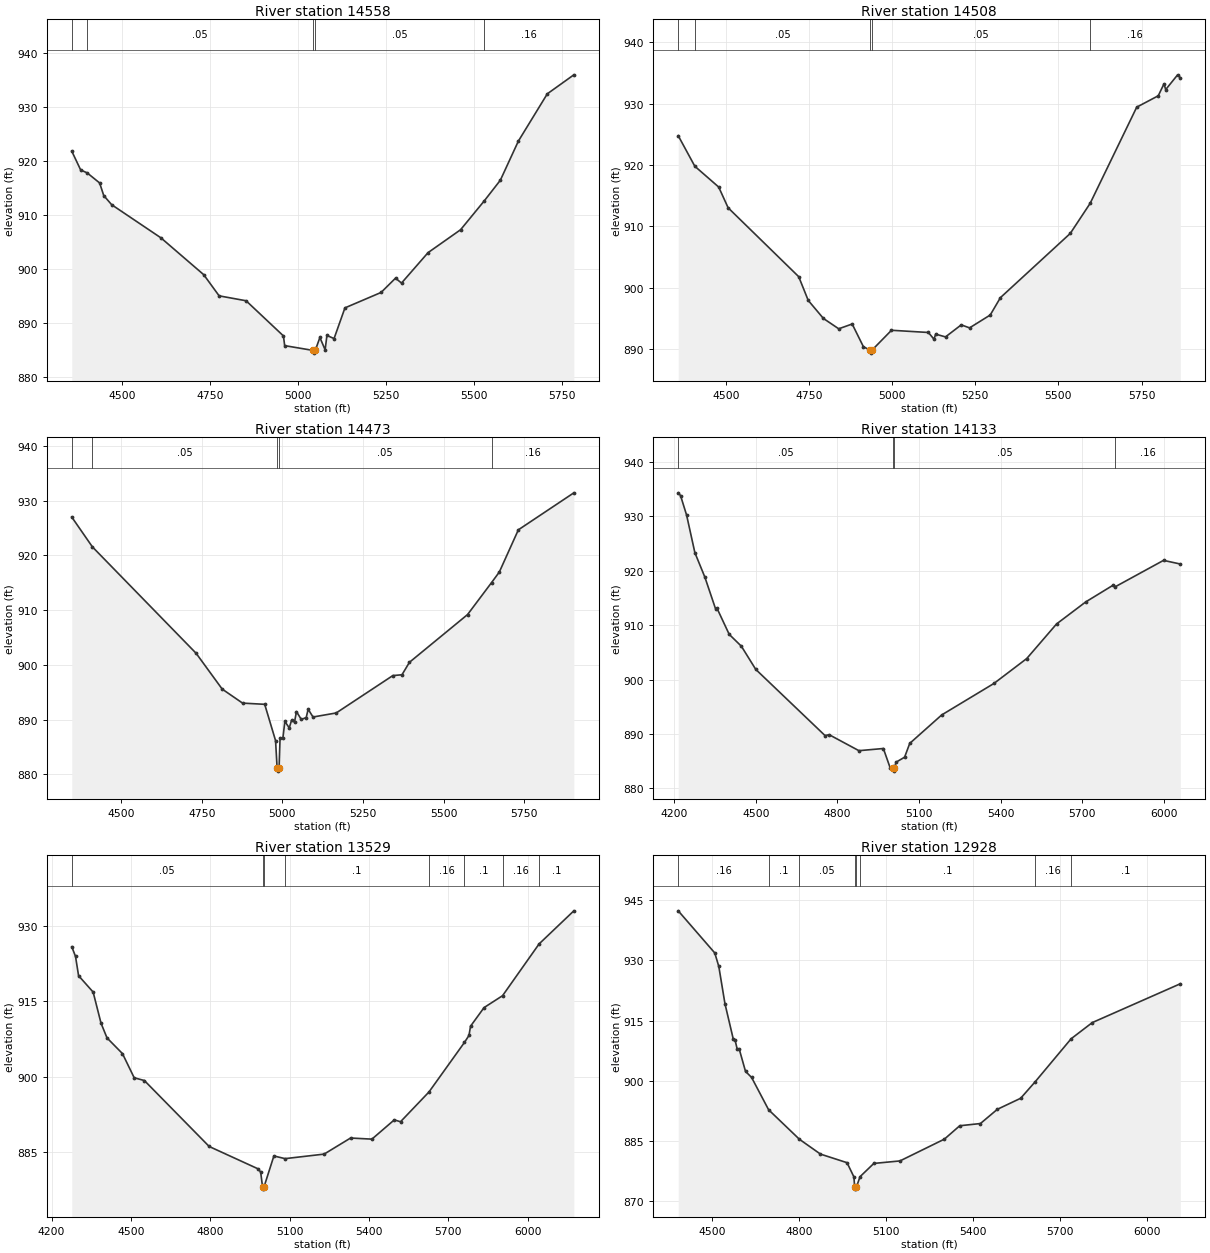
Type RM Length L Ch R = 1,14558,50,50,50
BEGIN DESCRIPTION:
PEDERNALES TRIB 1 33.0
END DESCRIPTION:
XS GIS Cut Line= 4
      2979837.32     10100496.92      2979592.52     10099942.22
      2979543.04     10099851.07      2978845.10     10099687.00
#Sta/Elev= 30
  4356.3  921.80  4381.6  918.31  4400.1  917.77  4435.5  915.90  4447.2  913.56
  4469.7  911.87  4609.6  905.73  4731.4  898.89  4775.1  894.97  4851.7  894.06
  4957.9  887.54  4961.4  885.74  5042.4  884.85  5045.1  884.35  5048.4  884.85
  5061.5  887.25  5076.4  884.96  5081.5  887.63  5101.8  887.05  5132.7  892.74
  5235.4  895.60  5276.5  898.25  5293.5  897.34  5368.9  902.98  5461.4  907.23
  5528.7  912.58  5574.4  916.41  5625.7  923.67  5707.9  932.43  5783.3  935.95
#Mann=5,-1,0
  4356.3     0.1       0  4400.1    0.05       0  5042.4   0.035       0
  5048.4    0.05       0  5528.7    0.16       0
Bank Sta=5042.4,5048.4
Exp/Cntr=0.3,0.1

Type RM Length L Ch R = 1,14508,35,35,35
BEGIN DESCRIPTION:
PEDERNALES TRIB 1 32.0
END DESCRIPTION:
XS GIS Cut Line= 4
      2979894.58     10100478.64      2979634.18     10099913.57
      2979574.29     10099817.22      2978824.24     10099627.10
#Sta/Elev= 30
  4357.0  924.77  4406.9  919.80  4478.6  916.42  4507.0  913.04  4719.2  901.83
  4747.8  897.97  4793.5  895.03  4839.5  893.35  4879.9  894.13  4913.8  890.42
  4933.8  889.89  4936.5  889.39  4939.8  889.89  4998.1  893.11  5109.0  892.75
  5125.8  891.66  5131.0  892.48  5160.5  892.03  5207.8  893.99  5232.8  893.50
  5294.9  895.59  5325.6  898.42  5535.6  908.87  5595.3  913.76  5735.4  929.42
  5800.1  931.27  5817.3  933.21  5822.5  932.28  5858.3  934.68  5866.4  934.22
#Mann=5,-1,0
  4357.0     0.1       0  4406.9    0.05       0  4933.8   0.035       0
  4939.8    0.05       0  5595.3    0.16       0
Bank Sta=4933.8,4939.8
Exp/Cntr=0.3,0.1

Type RM Length L Ch R = 1,14473,340,340,340
BEGIN DESCRIPTION:
PEDERNALES TRIB 1 31.0
END DESCRIPTION:
XS GIS Cut Line= 5
      2979931.05     10100478.22      2979690.17     10099933.97
      2979644.60     10099868.86      2979587.31     10099780.32
      2978834.71     10099586.31
#Sta/Elev= 30
  4346.9  927.00  4410.9  921.55  4732.7  902.10  4813.5  895.56  4876.7  893.00
  4945.3  892.78  4979.0  886.15  4983.9  881.07  4986.6  880.57  4989.9  881.07
  4993.0  886.67  5001.7  886.57  5007.8  889.66  5021.5  888.47  5028.6  889.86
  5037.8  889.54  5043.8  891.45  5058.9  890.01  5074.1  890.37  5080.1  891.88
  5095.2  890.46  5167.1  891.20  5342.7  898.03  5371.1  898.18  5394.3  900.46
  5574.5  909.18  5648.9  915.02  5673.1  916.96  5732.1  924.67  5904.2  931.43
#Mann=5,-1,0
  4346.9     0.1       0  4410.9    0.05       0  4983.9   0.035       0
  4989.9    0.05       0  5648.9    0.16       0
Bank Sta=4983.9,4989.9
Exp/Cntr=0.3,0.1

Type RM Length L Ch R = 1,14133,604,604,604
BEGIN DESCRIPTION:
PEDERNALES TRIB 1 30.0
END DESCRIPTION:
XS GIS Cut Line= 4
      2980276.12     10100148.39      2980033.06     10099662.27
      2979607.71     10099527.72      2978757.02     10099445.25
#Sta/Elev= 30
  4215.4  934.33  4223.8  933.83  4246.1  930.24  4276.5  923.33  4313.2  918.83
  4352.3  913.03  4357.9  913.09  4402.6  908.31  4447.4  906.12  4500.1  901.87
  4754.8  889.69  4769.8  889.86  4879.1  886.92  4968.9  887.32  4994.5  883.68
  5003.5  883.66  5006.2  883.16  5009.5  883.66  5015.4  884.80  5046.9  885.72
  5065.8  888.26  5183.2  893.49  5375.1  899.28  5495.6  903.86  5605.1  910.22
  5712.2  914.27  5814.2  917.39  5821.5  917.08  5998.0  921.91  6059.7  921.24
#Mann=4,-1,0
  4215.4    0.05       0  5003.5   0.035       0  5009.5    0.05       0
  5821.5    0.16       0
Bank Sta=5003.5,5009.5
Exp/Cntr=0.3,0.1

Type RM Length L Ch R = 1,13529,601,601,601
BEGIN DESCRIPTION:
PEDERNALES TRIB 1 29.0
END DESCRIPTION:
XS GIS Cut Line= 4
      2980432.37     10099996.49      2980206.67     10099527.72
      2980211.01     10099024.25      2979483.11     10098538.98
#Sta/Elev= 30
  4276.3  925.82  4290.5  923.89  4302.0  920.07  4357.1  916.82  4386.9  910.65
  4409.5  907.73  4468.0  904.61  4512.4  899.81  4550.8  899.27  4796.0  886.18
  4980.6  881.75  4990.6  881.11  4997.6  878.22  5000.3  877.72  5003.6  878.22
  5040.6  884.30  5083.0  883.77  5230.6  884.67  5330.6  887.86  5411.3  887.64
  5495.9  891.46  5519.5  891.09  5627.1  897.00  5761.1  906.82  5778.3  908.21
  5784.3  910.05  5835.4  913.74  5905.3  916.10  6043.6  926.38  6174.9  932.94
#Mann=8,-1,0
  4276.3    0.05       0  4997.6   0.035       0  5003.6    0.05       0
  5083.0     0.1       0  5627.1    0.16       0  5761.1     0.1       0
  5905.3    0.16       0  6043.6     0.1       0
Bank Sta=4997.6,5003.6
Exp/Cntr=0.3,0.1

Type RM Length L Ch R = 1,12928,412,412,412
BEGIN DESCRIPTION:
PEDERNALES TRIB 1 28.0
END DESCRIPTION:
XS GIS Cut Line= 4
      2981061.72     10099358.46      2980744.86     10099067.65
      2980102.50     10098798.55      2979695.23     10098347.96
#Sta/Elev= 30
  4382.2  942.34  4508.4  931.85  4522.3  928.49  4543.6  919.20  4572.0  910.49
  4578.7  910.07  4586.1  907.83  4592.9  907.90  4614.5  902.37  4635.5  900.86
  4694.3  892.81  4800.7  885.46  4873.4  881.77  4965.2  879.63  4989.0  876.07
  4991.4  873.55  4994.1  873.05  4997.4  873.55  5010.1  876.15  5057.7  879.45
  5147.9  880.07  5301.4  885.50  5354.4  888.83  5425.8  889.38  5484.2  892.92
  5564.7  895.67  5614.2  899.72  5739.1  910.49  5812.0  914.51  6116.1  924.18
#Mann=8,-1,0
  4382.2    0.16       0  4694.3     0.1       0  4800.7    0.05       0
  4991.4   0.035       0  4997.4    0.05       0  5010.1     0.1       0
  5614.2    0.16       0  5739.1     0.1       0
Bank Sta=4991.4,4997.4
Exp/Cntr=0.3,0.1

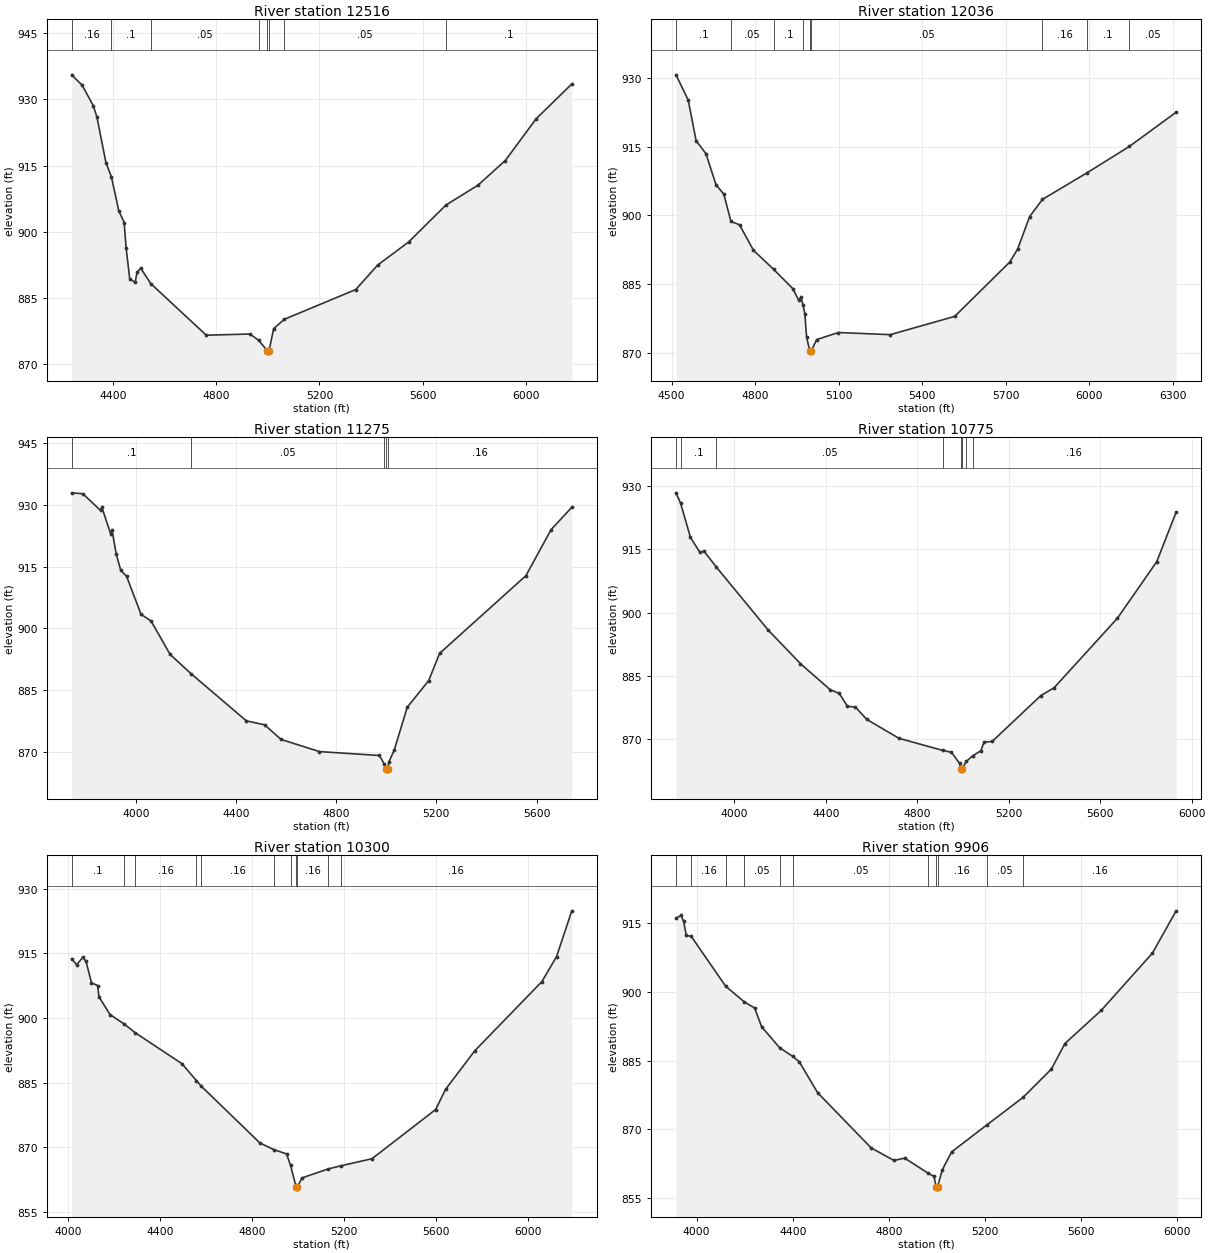
Type RM Length L Ch R = 1,12516,480,480,480
BEGIN DESCRIPTION:
PEDERNALES TRIB 1 27.0
END DESCRIPTION:
XS GIS Cut Line= 2
      2981148.53     10099171.84      2979837.73     10097739.51
#Sta/Elev= 30
  4238.0  935.55  4279.0  933.17  4321.6  928.59  4335.7  926.07  4371.0  915.67
  4392.2  912.46  4420.8  904.78  4441.8  902.11  4449.2  896.44  4463.4  889.32
  4484.4  888.55  4491.8  890.81  4506.0  891.78  4545.0  888.27  4760.6  876.59
  4930.2  876.86  4964.2  875.42  4998.1  873.03  5000.9  872.53  5004.1  873.03
  5022.1  878.07  5063.4  880.19  5340.9  886.93  5426.0  892.47  5546.3  897.70
  5690.7  906.05  5815.1  910.55  5921.2  916.13  6041.4  925.61  6179.6  933.48
#Mann=8,-1,0
  4238.0    0.16       0  4392.2     0.1       0  4545.0    0.05       0
  4964.2     0.1       0  4998.1    0.07       0  5004.1     0.1       0
  5063.4    0.05       0  5690.7     0.1       0
Bank Sta=4998.1,5004.1
Exp/Cntr=0.3,0.1

Type RM Length L Ch R = 1,12036,761,761,761
BEGIN DESCRIPTION:
PEDERNALES TRIB 1 26.0
END DESCRIPTION:
XS GIS Cut Line= 3
      2981391.57     10099002.55      2980883.75     10098425.29
      2980128.54     10097730.84
#Sta/Elev= 30
  4516.1  930.64  4559.9  925.15  4588.3  916.29  4623.5  913.48  4659.5  906.74
  4687.7  904.64  4713.3  898.70  4744.0  897.98  4794.2  892.41  4866.1  888.29
  4935.6  884.05  4956.5  881.53  4964.1  882.21  4972.6  880.43  4978.3  878.64
  4984.9  873.47  4996.2  870.52  4998.9  870.02  5002.2  870.52  5020.6  872.96
  5098.8  874.51  5284.9  874.04  5516.2  878.02  5714.2  889.87  5742.5  892.72
  5785.1  899.75  5831.1  903.51  5990.5  909.27  6142.8  915.03  6310.9  922.49
#Mann=9,-1,0
  4516.1     0.1       0  4713.3    0.05       0  4866.1     0.1       0
  4972.6    0.05       0  4996.2   0.035       0  5002.2    0.05       0
  5831.1    0.16       0  5990.5     0.1       0  6142.8    0.05       0
Bank Sta=4996.2,5002.2
Exp/Cntr=0.3,0.1

Type RM Length L Ch R = 1,11275,500,500,500
BEGIN DESCRIPTION:
PEDERNALES TRIB 1 24.0
END DESCRIPTION:
XS GIS Cut Line= 4
      2981573.85     10099145.76      2981408.92     10098516.43
      2980979.24     10097795.95      2980684.12     10097383.65
#Sta/Elev= 30
  3744.2  932.93  3789.0  932.70  3859.5  928.64  3864.6  929.42  3899.9  922.97
  3905.0  923.97  3922.0  918.07  3940.2  914.08  3963.4  912.63  4021.0  903.41
  4061.4  901.75  4137.1  893.65  4220.6  888.96  4441.6  877.49  4514.4  876.53
  4579.8  872.98  4733.5  870.02  4972.9  869.07  4992.9  866.91  5000.4  865.77
  5003.1  865.27  5006.4  865.77  5009.9  867.43  5031.3  870.29  5083.9  880.81
  5169.5  887.29  5213.0  893.90  5557.6  912.79  5658.3  924.01  5740.7  929.41
#Mann=5,-1,0
  3744.2     0.1       0  4220.6    0.05       0  4992.9    0.16       0
  5000.4    0.07       0  5006.4    0.16       0
Bank Sta=5000.4,5006.4
Exp/Cntr=0.3,0.1

Type RM Length L Ch R = 1,10775,475,475,475
BEGIN DESCRIPTION:
PEDERNALES TRIB 1 23.0
END DESCRIPTION:
XS GIS Cut Line= 3
      2981760.49     10099236.92      2981695.38     10098199.59
      2980984.32     10097297.76
#Sta/Elev= 30
  3744.3  928.46  3764.5  925.99  3807.6  917.86  3847.7  914.43  3867.7  914.54
  3920.2  910.87  4148.3  895.82  4288.6  887.89  4418.8  881.70  4458.9  880.80
  4494.5  877.74  4529.0  877.58  4579.1  874.64  4719.4  870.16  4911.9  867.27
  4949.3  866.84  4984.5  864.22  4989.6  862.86  4992.4  862.36  4995.6  862.86
  5014.0  864.67  5041.4  865.96  5077.6  867.19  5092.0  869.26  5127.3  869.40
  5340.5  880.31  5398.3  882.16  5675.6  898.70  5847.2  912.10  5932.1  923.86
#Mann=8,-1,0
  3744.3    0.05       0  3764.5     0.1       0  3920.2    0.05       0
  4911.9    0.16       0  4989.6    0.07       0  4995.6    0.16       0
  5014.0    0.05       0  5041.4    0.16       0
Bank Sta=4989.6,4995.6
Exp/Cntr=0.3,0.1

Type RM Length L Ch R = 1,10300,394,394,394
BEGIN DESCRIPTION:
PEDERNALES TRIB 1 22.0
END DESCRIPTION:
XS GIS Cut Line= 4
      2982298.69     10098933.12      2982046.95     10098134.49
      2981756.15     10097986.92      2981118.13     10097201.33
#Sta/Elev= 30
  4016.6  913.70  4038.1  912.33  4065.2  914.03  4078.9  913.14  4102.8  908.15
  4129.9  907.49  4135.1  904.90  4183.7  900.76  4245.5  898.57  4291.8  896.60
  4496.3  889.38  4559.0  885.47  4581.1  884.12  4835.7  870.98  4895.9  869.46
  4951.3  868.45  4968.5  865.85  4992.9  860.79  4995.6  860.29  4998.9  860.79
  5018.1  862.89  5132.9  864.98  5187.1  865.69  5323.3  867.35  5599.8  878.75
  5642.9  883.43  5770.8  892.42  6061.7  908.40  6125.6  914.19  6192.1  924.83
#Mann=11,-1,0
  4016.6     0.1       0  4245.5    0.05       0  4291.8    0.16       0
  4559.0    0.05       0  4581.1    0.16       0  4895.9    0.05       0
  4968.5    0.16       0  4992.9    0.07       0  4998.9    0.16       0
  5132.9    0.05       0  5187.1    0.16       0
Bank Sta=4992.9,4998.9
Exp/Cntr=0.3,0.1

Type RM Length L Ch R = 1,9906,301,301,301
BEGIN DESCRIPTION:
PEDERNALES TRIB 1 21.0
END DESCRIPTION:
XS GIS Cut Line= 3
      2982550.43     10098711.77      2981864.65     10097353.24
      2981422.71     10097010.95
#Sta/Elev= 30
  3914.2  916.13  3934.8  916.77  3945.6  915.51  3957.1  912.38  3977.5  912.18
  4120.4  901.30  4198.4  897.84  4241.4  896.51  4270.5  892.40  4345.5  887.81
  4400.5  885.90  4427.3  884.73  4503.4  877.99  4726.3  865.90  4821.1  863.17
  4865.7  863.67  4962.6  860.39  4987.4  859.69  4996.5  857.39  4999.3  856.89
  5002.5  857.39  5021.8  861.08  5060.8  865.02  5208.6  870.98  5358.4  876.96
  5475.7  883.13  5532.4  888.74  5683.1  895.97  5896.7  908.53  5995.0  917.76
#Mann=11,-1,0
  3914.2     0.1       0  3977.5    0.16       0  4120.4     0.1       0
  4198.4    0.05       0  4345.5     0.1       0  4400.5    0.05       0
  4962.6    0.16       0  4996.5    0.07       0  5002.5    0.16       0
  5208.6    0.05       0  5358.4    0.16       0
Bank Sta=4996.5,5002.5
Exp/Cntr=0.3,0.1

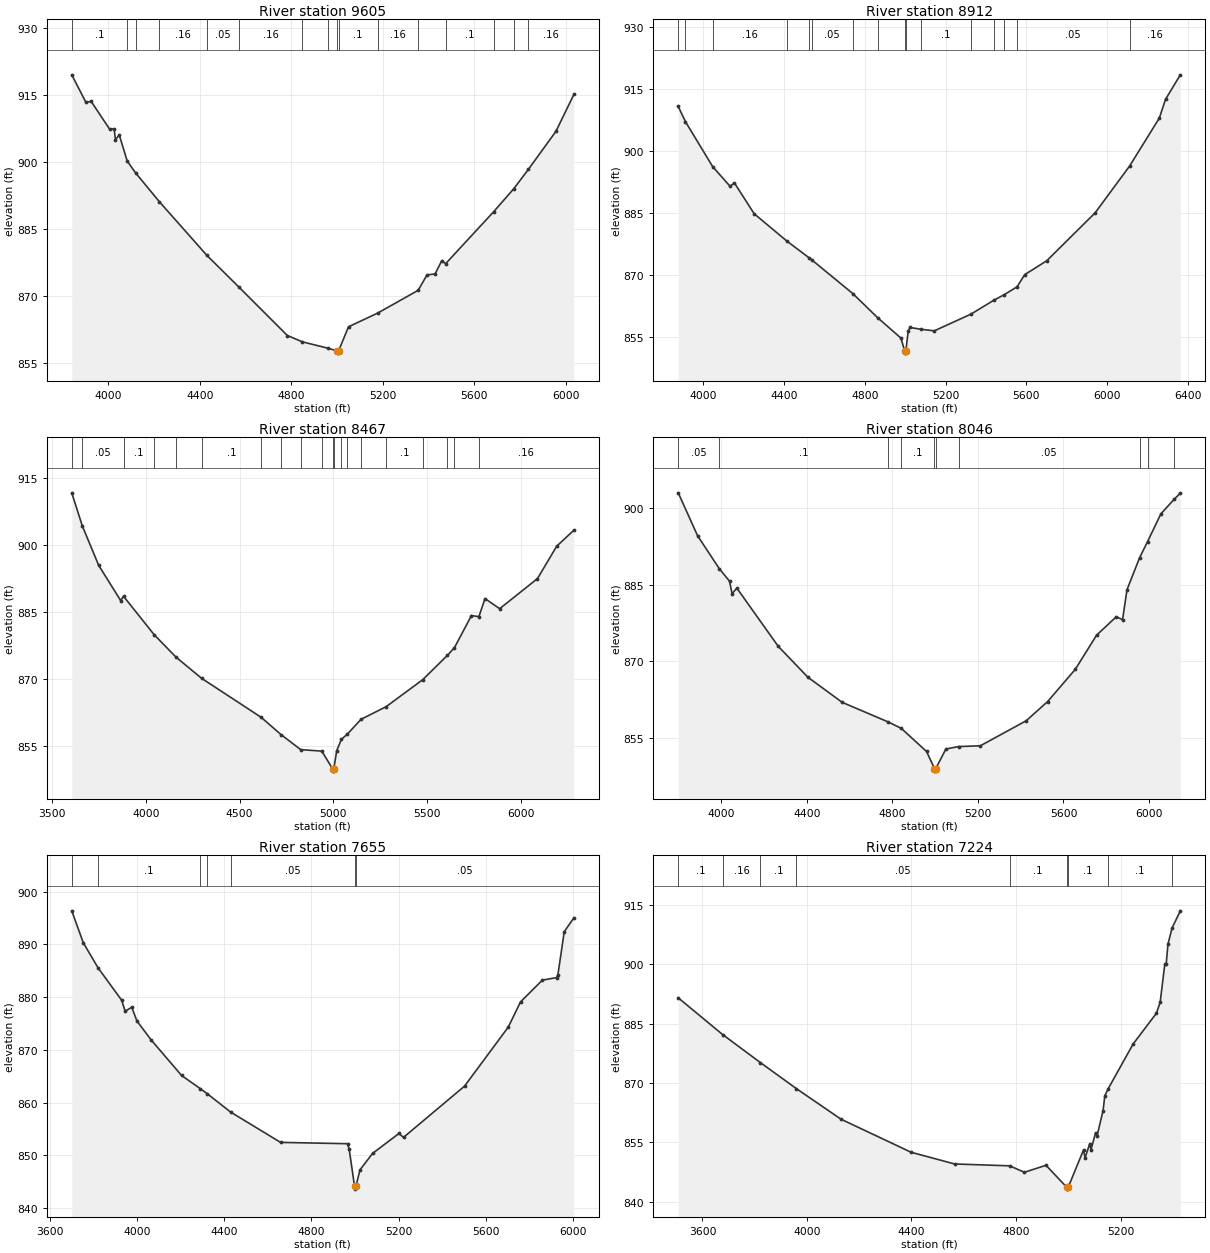
Type RM Length L Ch R = 1,9605,693,693,693
BEGIN DESCRIPTION:
PEDERNALES TRIB 1 20.0
END DESCRIPTION:
XS GIS Cut Line= 4
      2982676.28     10098703.05      2982411.53     10097791.61
      2982185.83     10097288.14      2981635.70     10096867.96
#Sta/Elev= 30
  3841.2  919.50  3903.0  913.34  3926.0  913.55  4007.1  907.30  4026.6  907.42
  4031.8  904.99  4048.8  906.04  4083.4  900.21  4120.0  897.57  4223.6  891.13
  4431.0  879.14  4570.5  872.06  4783.1  861.18  4848.9  859.77  4958.8  858.37
  5000.6  857.75  5003.4  857.25  5006.6  857.75  5050.0  863.14  5178.4  866.23
  5354.2  871.30  5392.9  874.74  5428.3  874.97  5457.3  877.93  5474.5  877.27
  5684.3  888.89  5772.5  894.06  5835.4  898.33  5956.1  906.86  6034.3  915.10
#Mann=16,-1,0
  3841.2     0.1       0  4083.4    0.16       0  4120.0     0.1       0
  4223.6    0.16       0  4431.0    0.05       0  4570.5    0.16       0
  4848.9    0.05       0  4958.8     0.1       0  5000.6    0.07       0
  5006.6     0.1       0  5178.4    0.16       0  5354.2    0.05       0
  5474.5     0.1       0  5684.3    0.16       0  5772.5     0.1       0
  5835.4    0.16       0
Bank Sta=5000.6,5006.6
Exp/Cntr=0.3,0.1

Type RM Length L Ch R = 1,8912,445,445,445
BEGIN DESCRIPTION:
PEDERNALES TRIB 1 19.0
END DESCRIPTION:
XS GIS Cut Line= 4
      2983296.93     10098459.97      2982954.06     10097648.38
      2982724.03     10097335.88      2981699.73     10096680.50
#Sta/Elev= 30
  3876.9  910.82  3912.6  907.14  4047.2  896.25  4133.4  891.48  4155.1  892.28
  4252.8  884.82  4415.0  878.18  4523.6  874.18  4536.8  873.69  4741.0  865.47
  4864.3  859.61  4979.6  854.67  4997.5  851.54  5000.2  851.04  5003.5  851.54
  5015.1  856.34  5023.6  857.26  5079.1  856.82  5144.2  856.44  5325.7  860.49
  5439.7  863.88  5490.7  865.21  5553.8  867.11  5591.9  870.06  5701.0  873.43
  5940.3  885.04  6110.5  896.35  6258.3  908.02  6288.7  912.54  6362.0  918.49
#Mann=16,-1,0
  3876.9     0.1       0  3912.6    0.05       0  4047.2    0.16       0
  4415.0    0.05       0  4523.6     0.1       0  4536.8    0.05       0
  4741.0     0.1       0  4864.3    0.16       0  4997.5    0.07       0
  5003.5    0.16       0  5079.1     0.1       0  5325.7    0.16       0
  5439.7    0.05       0  5490.7    0.16       0  5553.8    0.05       0
  6110.5    0.16       0
Bank Sta=4997.5,5003.5
Exp/Cntr=0.3,0.1

Type RM Length L Ch R = 1,8467,421,421,421
BEGIN DESCRIPTION:
PEDERNALES TRIB 1 18.0
END DESCRIPTION:
XS GIS Cut Line= 4
      2983461.87     10098329.78      2983053.89     10097153.59
      2982711.01     10097014.70      2982125.08     10096129.30
#Sta/Elev= 30
  3605.5  911.60  3661.3  904.25  3748.7  895.43  3865.9  887.55  3881.5  888.49
  4044.8  879.91  4161.5  874.89  4298.0  870.16  4614.8  861.47  4720.5  857.62
  4826.1  854.24  4938.3  853.91  4996.3  849.94  4999.0  849.44  5002.3  849.94
  5018.0  854.01  5043.0  856.54  5075.4  857.74  5147.7  861.01  5281.5  863.84
  5476.0  869.85  5607.8  875.28  5645.4  877.01  5736.3  884.19  5775.9  883.94
  5808.5  887.98  5886.7  885.72  6088.3  892.45  6190.6  899.67  6282.1  903.25
#Mann=20,-1,0
  3605.5     0.1       0  3661.3    0.05       0  3881.5     0.1       0
  4044.8    0.05       0  4161.5     0.1       0  4298.0     0.1       0
  4614.8    0.05       0  4720.5     0.1       0  4826.1     0.1       0
  4938.3    0.05       0  4996.3   0.035       0  5002.3    0.05       0
  5043.0     0.1       0  5075.4    0.05       0  5147.7     0.1       0
  5281.5     0.1       0  5476.0    0.05       0  5607.8     0.1       0
  5645.4    0.05       0  5775.9    0.16       0
Bank Sta=4996.3,5002.3
Exp/Cntr=0.3,0.1

Type RM Length L Ch R = 1,8046,391,391,391
BEGIN DESCRIPTION:
PEDERNALES TRIB 1 17.0
END DESCRIPTION:
XS GIS Cut Line= 4
      2983744.00     10098112.79      2983240.52     10097214.35
      2983214.48     10096845.43      2982456.15     10096277.76
#Sta/Elev= 30
  3799.3  903.00  3889.9  894.58  3991.4  888.14  4039.0  885.70  4051.0  883.24
  4073.3  884.34  4266.7  872.94  4405.8  866.87  4566.3  861.96  4781.9  858.11
  4841.7  856.88  4960.1  852.35  4997.2  849.00  5000.0  848.50  5003.2  849.00
  5050.4  852.83  5110.2  853.31  5211.5  853.46  5426.1  858.37  5526.2  862.13
  5655.4  868.44  5755.4  875.15  5847.1  878.73  5876.3  878.15  5897.1  884.03
  5955.9  890.28  5993.1  893.44  6055.5  898.89  6118.1  901.76  6146.3  902.93
#Mann=10,-1,0
  3799.3    0.05       0  3991.4     0.1       0  4781.9    0.05       0
  4841.7     0.1       0  4997.2    0.07       0  5003.2     0.1       0
  5110.2    0.05       0  5955.9     0.1       0  5993.1    0.05       0
  6118.1    0.16       0
Bank Sta=4997.2,5003.2
Exp/Cntr=0.3,0.1

Type RM Length L Ch R = 1,7655,431,431,431
BEGIN DESCRIPTION:
PEDERNALES TRIB 1 16.0
END DESCRIPTION:
XS GIS Cut Line= 3
      2983926.28     10097926.14      2983796.08     10097032.06
      2982667.57     10096203.04
#Sta/Elev= 30
  3700.3  896.34  3753.3  890.27  3821.1  885.53  3929.1  879.40  3945.3  877.31
  3975.6  878.07  3999.1  875.47  4064.1  871.89  4204.3  865.13  4289.8  862.64
  4320.9  861.71  4429.0  858.20  4658.4  852.45  4965.5  852.20  4973.1  851.20
  4998.0  844.09  5000.8  843.59  5004.0  844.09  5022.7  847.24  5080.5  850.36
  5201.6  854.14  5222.5  853.40  5502.5  863.11  5703.2  874.30  5759.5  879.08
  5859.8  883.21  5924.6  883.68  5930.8  884.17  5960.1  892.39  6004.1  895.00
#Mann=7,-1,0
  3700.3    0.05       0  3821.1     0.1       0  4289.8    0.05       0
  4320.9     0.1       0  4429.0    0.05       0  4998.0   0.035       0
  5004.0    0.05       0
Bank Sta=4998,5004
Exp/Cntr=0.3,0.1

Type RM Length L Ch R = 1,7224,893,893,893
BEGIN DESCRIPTION:
PEDERNALES TRIB 1 15.0
END DESCRIPTION:
XS GIS Cut Line= 3
      2984416.76     10097687.48      2983778.72     10096697.86
      2983470.55     10096020.76
#Sta/Elev= 30
  3507.4  891.51  3677.1  882.25  3821.8  875.16  3959.8  868.58  4130.6  860.86
  4398.8  852.52  4565.1  849.57  4775.6  849.10  4832.2  847.47  4914.7  849.24
  4994.0  843.72  4996.8  843.22  5000.0  843.72  5058.6  853.15  5064.1  851.06
  5081.6  854.57  5087.1  853.18  5104.7  857.48  5110.2  856.69  5133.2  863.03
  5139.9  866.79  5152.5  868.53  5248.5  879.88  5337.6  887.64  5351.7  890.39
  5369.3  899.93  5374.8  900.09  5381.6  905.04  5397.0  909.09  5428.8  913.47
#Mann=9,-1,0
  3507.4     0.1       0  3677.1    0.16       0  3821.8     0.1       0
  3959.8    0.05       0  4775.6     0.1       0  4994.0   0.035       0
  5000.0     0.1       0  5152.5     0.1       0  5397.0    0.16       0
Bank Sta=4994,5000
Exp/Cntr=0.3,0.1

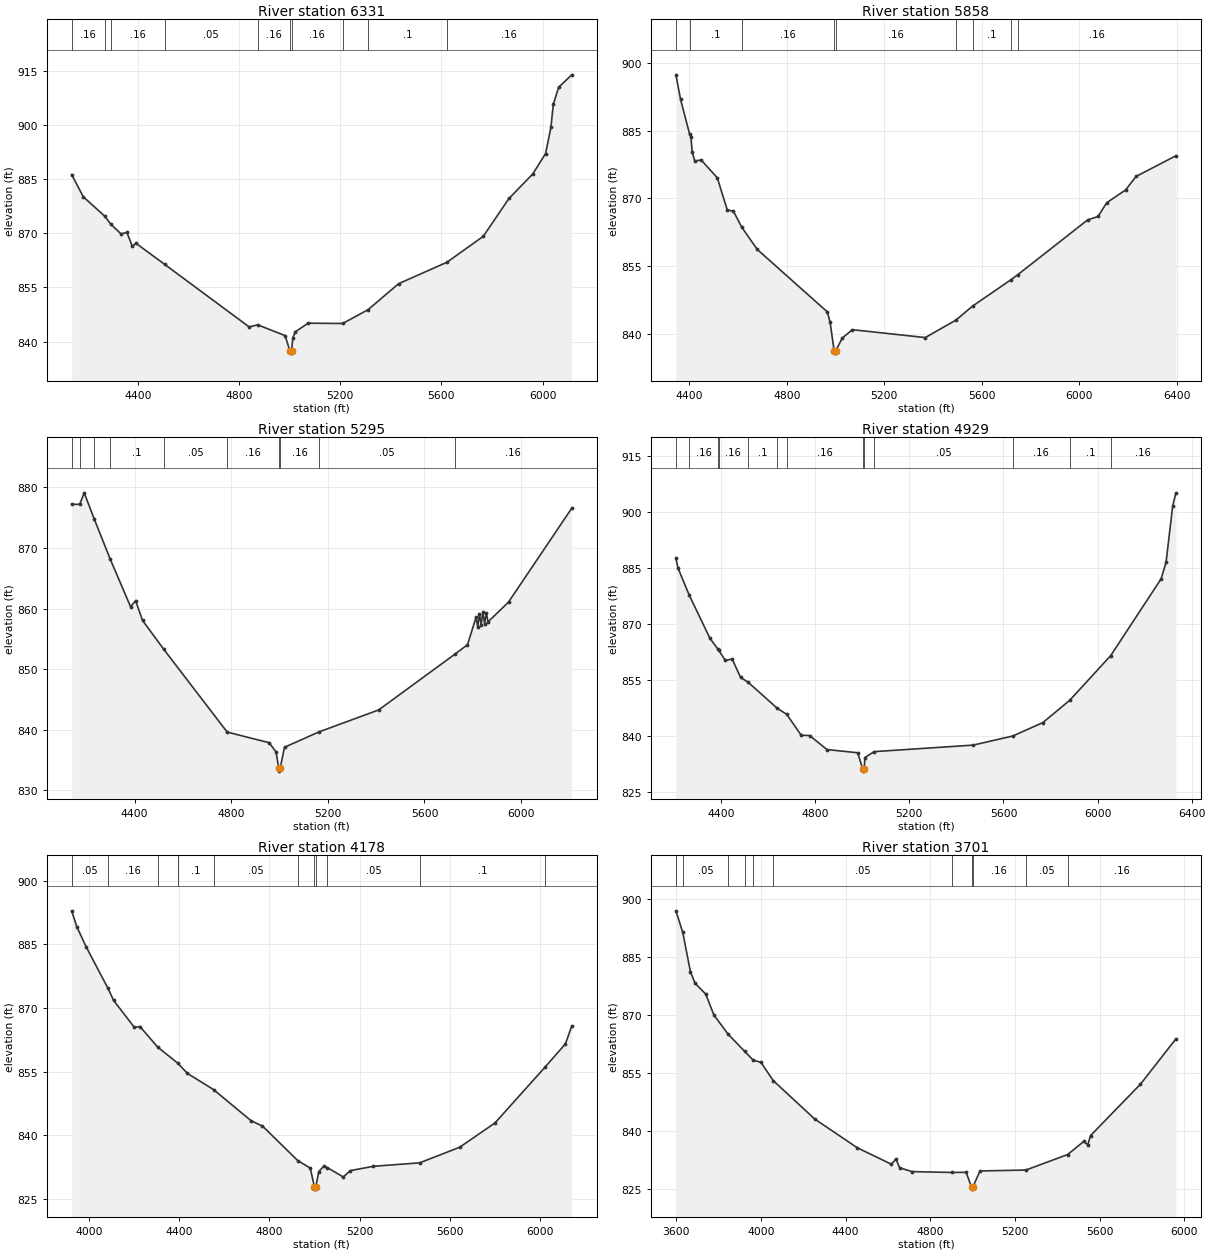
Type RM Length L Ch R = 1,6331,473,473,473
BEGIN DESCRIPTION:
PEDERNALES TRIB 1 14.0
END DESCRIPTION:
XS GIS Cut Line= 4
      2984707.54     10097266.46      2984455.80     10096641.43
      2984355.97     10096064.18      2983748.29     10095682.21
#Sta/Elev= 30
  4137.8  886.32  4183.9  880.14  4268.0  874.84  4292.0  872.59  4332.7  869.89
  4356.4  870.27  4377.9  866.39  4391.8  867.28  4506.0  861.39  4839.7  844.06
  4873.4  844.64  4981.8  841.65  5001.3  837.29  5004.0  836.79  5007.3  837.29
  5012.3  840.98  5022.4  842.72  5073.1  845.10  5209.6  845.01  5310.2  848.86
  5431.2  856.07  5621.6  861.99  5765.6  869.20  5867.0  879.69  5961.4  886.51
  6011.8  892.15  6033.0  899.42  6042.4  905.81  6063.6  910.55  6115.2  914.00
#Mann=10,-1,0
  4137.8    0.16       0  4268.0     0.1       0  4292.0    0.16       0
  4506.0    0.05       0  4873.4    0.16       0  5001.3    0.07       0
  5007.3    0.16       0  5209.6    0.05       0  5310.2     0.1       0
  5621.6    0.16       0
Bank Sta=5001.3,5007.3
Exp/Cntr=0.3,0.1

Type RM Length L Ch R = 1,5858,563,563,563
BEGIN DESCRIPTION:
PEDERNALES TRIB 1 12.0
END DESCRIPTION:
XS GIS Cut Line= 3
      2985037.40     10097019.03      2984850.76     10096224.77
      2983917.64     10095413.16
#Sta/Elev= 30
  4344.3  897.39  4363.3  891.98  4400.4  884.26  4405.7  883.68  4411.4  880.25
  4421.7  878.29  4448.1  878.49  4514.1  874.56  4555.2  867.41  4580.5  867.14
  4614.2  863.62  4678.5  858.64  4966.1  844.79  4977.5  842.46  4993.9  836.15
  4996.7  835.65  4999.9  836.15  5027.7  839.01  5068.8  840.85  5368.1  839.10
  5494.4  843.00  5562.2  846.09  5719.6  851.93  5746.7  853.01  6034.6  865.21
  6077.4  865.97  6112.5  869.00  6190.3  871.85  6233.1  874.84  6396.9  879.44
#Mann=9,-1,0
  4344.3    0.16       0  4400.4     0.1       0  4614.2    0.16       0
  4993.9    0.07       0  4999.9    0.16       0  5494.4    0.05       0
  5562.2     0.1       0  5719.6    0.05       0  5746.7    0.16       0
Bank Sta=4993.9,4999.9
Exp/Cntr=0.3,0.1

Type RM Length L Ch R = 1,5295,366,366,366
BEGIN DESCRIPTION:
PEDERNALES TRIB 1 11.0
END DESCRIPTION:
XS GIS Cut Line= 3
      2985605.99     10096619.75      2984894.17     10095795.08
      2984183.29     10095118.88
#Sta/Elev= 30
  4139.3  877.23  4172.4  877.22  4191.3  879.12  4232.2  874.85  4298.6  868.21
  4383.2  860.32  4404.1  861.32  4432.6  858.06  4521.0  853.27  4783.1  839.63
  4957.0  837.87  4985.5  836.35  4996.7  833.68  4999.5  833.18  5002.7  833.68
  5020.6  837.12  5162.4  839.64  5410.5  843.28  5725.3  852.46  5778.2  854.04
  5813.8  858.58  5820.7  856.98  5827.9  859.11  5834.8  857.37  5842.1  859.48
  5849.0  857.52  5856.3  859.29  5863.2  857.81  5948.1  861.08  6209.8  876.57
#Mann=10,-1,0
  4139.3    0.05       0  4172.4     0.1       0  4232.2    0.05       0
  4298.6     0.1       0  4521.0    0.05       0  4783.1    0.16       0
  4996.7    0.07       0  5002.7    0.16       0  5162.4    0.05       0
  5725.3    0.16       0
Bank Sta=4996.7,5002.7
Exp/Cntr=0.3,0.1

Type RM Length L Ch R = 1,4929,751,751,751
BEGIN DESCRIPTION:
PEDERNALES TRIB 1 10.0
END DESCRIPTION:
XS GIS Cut Line= 4
      2985775.25     10096450.47      2985428.02     10095968.69
      2985263.09     10095552.02      2984477.51     10094805.51
#Sta/Elev= 30
  4207.5  887.67  4216.3  885.00  4263.9  877.78  4352.5  866.16  4385.2  863.38
  4388.9  863.05  4417.5  860.30  4446.9  860.63  4482.5  855.72  4513.9  854.47
  4638.9  847.45  4678.7  845.85  4740.2  840.26  4775.8  840.19  4849.7  836.43
  4980.5  835.57  5001.8  831.16  5004.6  830.66  5007.8  831.16  5011.0  834.28
  5050.1  835.87  5470.9  837.62  5640.1  840.06  5767.8  843.66  5881.7  849.61
  6056.2  861.59  6270.1  882.09  6291.2  886.52  6319.5  901.64  6333.2  905.11
#Mann=13,-1,0
  4207.5     0.1       0  4263.9    0.16       0  4385.2     0.1       0
  4388.9    0.16       0  4513.9     0.1       0  4638.9    0.05       0
  4678.7    0.16       0  5001.8    0.07       0  5007.8    0.16       0
  5050.1    0.05       0  5640.1    0.16       0  5881.7     0.1       0
  6056.2    0.16       0
Bank Sta=5001.8,5007.8
Exp/Cntr=0.3,0.1

Type RM Length L Ch R = 1,4178,477,477,477
BEGIN DESCRIPTION:
PEDERNALES TRIB 1 9.0
END DESCRIPTION:
XS GIS Cut Line= 4
      2986165.87     10096185.72      2986000.94     10095404.45
      2985523.51     10095139.70      2984852.12     10094580.93
#Sta/Elev= 30
  3923.1  892.92  3945.6  889.22  3987.4  884.41  4084.4  874.61  4109.1  871.79
  4201.1  865.43  4225.9  865.62  4304.7  860.77  4394.0  856.96  4436.2  854.58
  4552.5  850.74  4719.4  843.38  4769.5  842.14  4925.5  834.01  4981.3  832.23
  5000.0  827.76  5002.8  827.26  5006.0  827.76  5019.0  831.38  5040.8  832.65
  5057.5  832.33  5127.8  830.12  5158.9  831.62  5261.8  832.65  5466.5  833.46
  5644.5  837.15  5800.8  842.88  6022.0  856.00  6113.2  861.54  6141.0  865.71
#Mann=11,-1,0
  3923.1    0.05       0  4084.4    0.16       0  4304.7    0.05       0
  4394.0     0.1       0  4552.5    0.05       0  4925.5    0.16       0
  5000.0    0.07       0  5006.0    0.16       0  5057.5    0.05       0
  5466.5     0.1       0  6022.0    0.16       0
Bank Sta=5000,5006
Exp/Cntr=0.3,0.1

Type RM Length L Ch R = 1,3701,558,558,558
BEGIN DESCRIPTION:
PEDERNALES TRIB 1 7.0
END DESCRIPTION:
XS GIS Cut Line= 4
      2986656.34     10095947.02      2986157.19     10094974.77
      2985493.13     10094579.80      2985315.81     10094117.05
#Sta/Elev= 30
  3598.6  896.88  3631.2  891.29  3667.3  881.14  3689.5  878.17  3739.5  875.40
  3778.3  869.98  3845.3  865.04  3923.5  860.62  3963.2  858.37  4000.2  857.78
  4058.5  853.06  4254.3  843.16  4454.9  835.76  4615.8  831.51  4638.0  832.86
  4654.6  830.61  4713.3  829.60  4903.5  829.38  4969.3  829.42  4994.5  825.58
  4997.3  825.08  5000.5  825.58  5034.6  829.77  5251.0  830.00  5448.1  833.99
  5524.3  837.38  5543.6  836.52  5556.3  838.88  5791.9  852.14  5959.7  863.85
#Mann=11,-1,0
  3598.6     0.1       0  3631.2    0.05       0  3845.3    0.16       0
  3923.5    0.05       0  3963.2     0.1       0  4058.5    0.05       0
  4903.5    0.16       0  4994.5    0.07       0  5000.5    0.16       0
  5251.0    0.05       0  5448.1    0.16       0
Bank Sta=4994.5,5000.5
Exp/Cntr=0.3,0.1