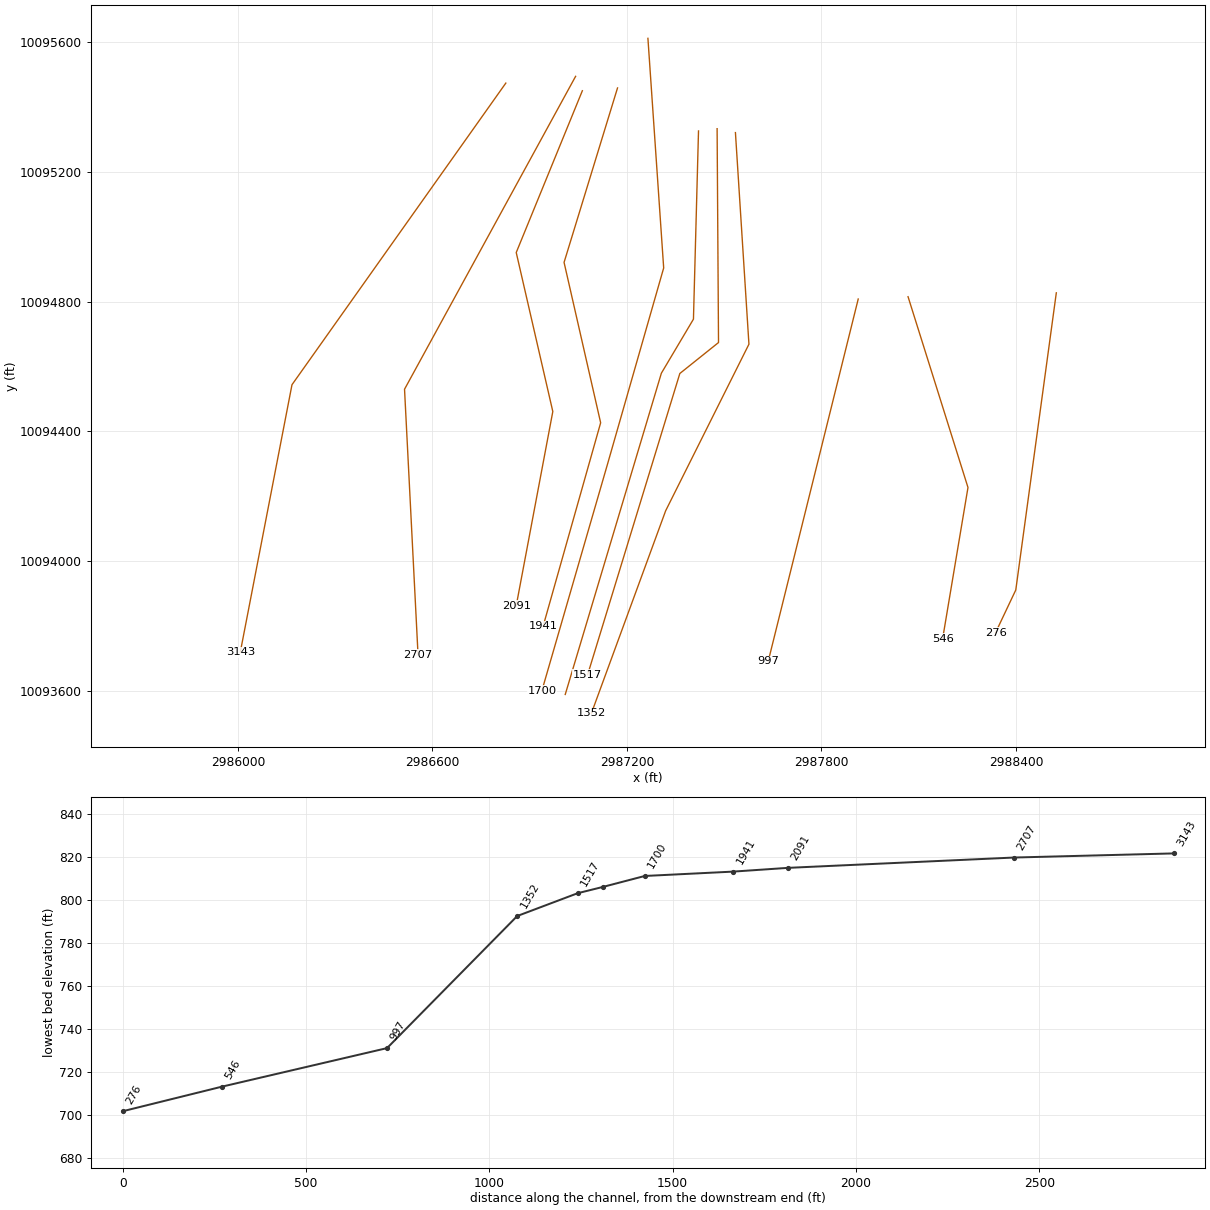
HEC-RAS study PEDERNALES TRIB 1.prj: PEDERNALES TRIB 1 Base Level Engineering

--- PEDERNALES TRIB 1.g01 (geometry) --- (continued)

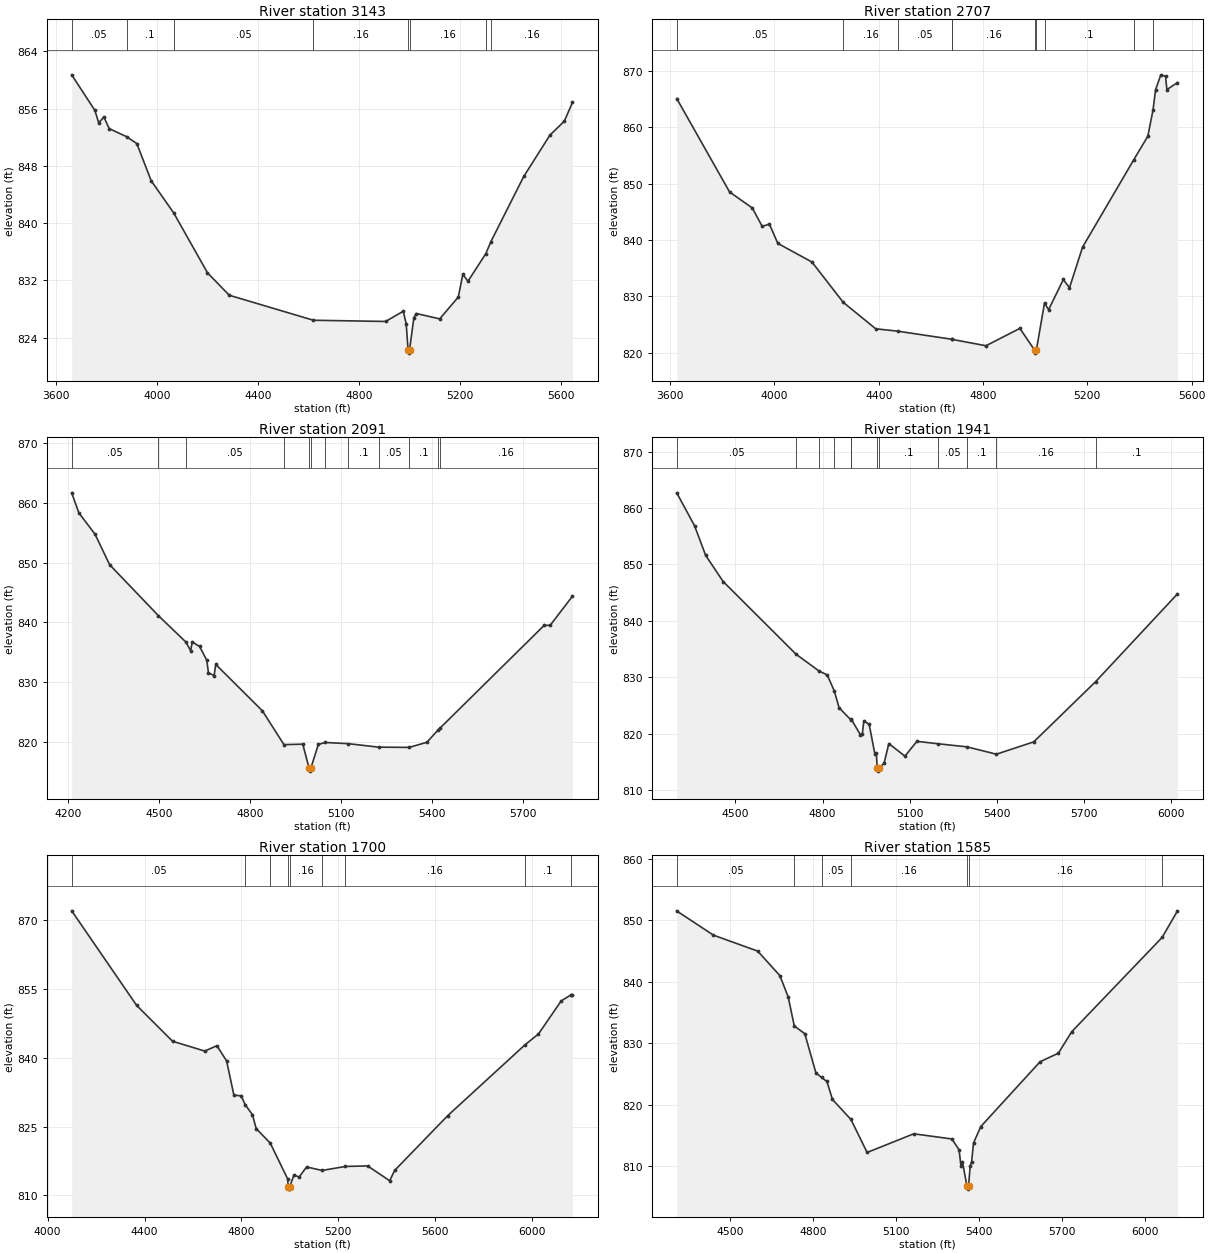
Type RM Length L Ch R = 1,3143,436,436,436
BEGIN DESCRIPTION:
PEDERNALES TRIB 1 6.0
END DESCRIPTION:
XS GIS Cut Line= 3
      2986826.43     10095473.86      2986166.74     10094543.34
      2986007.19     10093717.86
#Sta/Elev= 30
  3662.6  860.71  3754.4  855.74  3769.2  854.03  3790.1  854.81  3811.0  853.20
  3879.5  852.08  3920.2  851.12  3977.1  845.92  4066.6  841.41  4199.9  833.07
  4286.0  829.94  4618.9  826.45  4904.7  826.28  4974.7  827.71  4986.2  825.92
  4993.4  822.36  4996.1  821.86  4999.4  822.36  5016.7  826.83  5026.5  827.39
  5118.6  826.64  5192.2  829.68  5210.2  832.85  5230.6  831.90  5301.2  835.75
  5321.2  837.42  5451.2  846.52  5554.8  852.29  5611.7  854.24  5644.0  856.85
#Mann=8,-1,0
  3662.6    0.05       0  3879.5     0.1       0  4066.6    0.05       0
  4618.9    0.16       0  4993.4    0.07       0  4999.4    0.16       0
  5301.2     0.1       0  5321.2    0.16       0
Bank Sta=4993.4,4999.4
Exp/Cntr=0.3,0.1

Type RM Length L Ch R = 1,2707,616,616,616
BEGIN DESCRIPTION:
PEDERNALES TRIB 1 5.0
END DESCRIPTION:
XS GIS Cut Line= 3
      2987041.73     10095494.73      2986513.96     10094529.45
      2986555.62     10093710.05
#Sta/Elev= 30
  3625.1  865.13  3827.8  848.55  3915.1  845.70  3953.0  842.43  3980.5  842.85
  4012.8  839.42  4143.7  836.11  4263.9  828.95  4388.4  824.26  4472.3  823.84
  4679.1  822.41  4681.4  822.38  4811.1  821.25  4941.2  824.33  4998.3  820.44
  5001.1  819.94  5004.3  820.44  5035.7  828.83  5051.4  827.65  5107.9  833.01
  5131.5  831.53  5181.5  838.74  5377.2  854.20  5431.9  858.43  5451.6  863.03
  5461.9  866.73  5481.9  869.34  5500.1  869.06  5505.1  866.71  5545.7  867.97
#Mann=10,-1,0
  3625.1    0.05       0  4263.9    0.16       0  4472.3    0.05       0
  4679.1     0.1       0  4681.4    0.16       0  4998.3    0.07       0
  5004.3    0.16       0  5035.7     0.1       0  5377.2    0.05       0
  5451.6     0.1       0
Bank Sta=4998.3,5004.3
Exp/Cntr=0.3,0.1

Type RM Length L Ch R = 1,2091,150,150,150
BEGIN DESCRIPTION:
Mapping XS 91c779a7
END DESCRIPTION:
XS GIS Cut Line= 4
      2987062.54     10095450.26      2986858.55     10094951.13
      2986971.40     10094460.68      2986858.55     10093861.68
#Sta/Elev= 30
  4211.8  861.68  4235.4  858.33  4288.9  854.75  4336.9  849.66  4497.8  841.14
  4588.4  836.73  4604.1  835.29  4609.5  836.73  4633.5  836.00  4657.5  833.67
  4662.9  831.59  4681.6  831.12  4687.0  832.98  4840.7  825.24  4912.0  819.57
  4974.1  819.65  4994.8  815.64  4997.6  815.14  5000.8  815.64  5025.4  819.60
  5048.5  819.93  5124.6  819.73  5224.5  819.15  5325.1  819.11  5383.4  819.96
  5420.3  822.01  5426.0  822.29  5770.1  839.50  5790.5  839.54  5863.8  844.39
#Mann=12,-1,0
  4211.8    0.05       0  4497.8     0.1       0  4588.4    0.05       0
  4912.0    0.16       0  4994.8    0.07       0  5000.8    0.16       0
  5048.5    0.05       0  5124.6     0.1       0  5224.5    0.05       0
  5325.1     0.1       0  5420.3    0.05       0  5426.0    0.16       0
Bank Sta=4994.8,5000.8
Exp/Cntr=0.3,0.1

Type RM Length L Ch R = 1,1941,241,241,241
BEGIN DESCRIPTION:
Mapping XS 9e439c32
END DESCRIPTION:
XS GIS Cut Line= 4
      2987171.04     10095458.91      2987006.12     10094920.75
      2987118.97     10094425.96      2986941.31     10093797.65
#Sta/Elev= 30
  4298.0  862.69  4359.5  856.84  4397.5  851.62  4457.7  846.98  4708.7  834.10
  4787.6  831.13  4815.9  830.43  4840.4  827.58  4856.7  824.62  4897.4  822.47
  4898.5  822.59  4929.6  819.87  4936.8  819.97  4941.9  822.31  4960.4  821.66
  4979.8  816.44  4984.9  816.59  4988.1  813.89  4990.9  813.39  4994.1  813.89
  5011.7  814.80  5027.9  818.27  5083.4  816.04  5124.5  818.67  5197.1  818.24
  5297.0  817.69  5398.0  816.39  5526.6  818.57  5739.8  829.25  6021.3  844.79
#Mann=12,-1,0
  4298.0    0.05       0  4708.7     0.1       0  4787.6    0.05       0
  4840.4     0.1       0  4897.4    0.05       0  4898.5     0.1       0
  4988.1    0.07       0  4994.1     0.1       0  5197.1    0.05       0
  5297.0     0.1       0  5398.0    0.16       0  5739.8     0.1       0
Bank Sta=4988.1,4994.1
Exp/Cntr=0.3,0.1

Type RM Length L Ch R = 1,1700,115,115,115
BEGIN DESCRIPTION:
PEDERNALES TRIB 1 4.0
END DESCRIPTION:
XS GIS Cut Line= 4
      2987264.82     10095611.96      2987313.44     10094903.59
      2987140.67     10094300.09      2986937.57     10093598.89
#Sta/Elev= 30
  4099.4  872.10  4367.5  851.46  4515.7  843.64  4648.9  841.49  4699.0  842.67
  4739.1  839.33  4769.2  831.86  4799.3  831.74  4815.7  829.79  4845.7  827.61
  4861.3  824.55  4919.2  821.41  4991.2  813.58  4993.5  811.86  4996.3  811.36
  4999.5  811.86  5017.3  814.48  5038.1  813.98  5069.3  816.20  5133.6  815.44
  5229.8  816.31  5321.1  816.43  5412.6  813.19  5432.7  815.43  5652.0  827.39
  5970.8  842.84  6026.8  845.22  6120.5  852.43  6162.3  853.80  6167.2  853.80
#Mann=9,-1,0
  4099.4    0.05       0  4815.7     0.1       0  4919.2    0.16       0
  4993.5    0.07       0  4999.5    0.16       0  5133.6     0.1       0
  5229.8    0.16       0  5970.8     0.1       0  6162.3    0.16       0
Bank Sta=4993.5,4999.5
Exp/Cntr=0.3,0.1

Type RM Length L Ch R = 1,1585,68,68,68
BEGIN DESCRIPTION:
Mapping XS 70af5f57
END DESCRIPTION:
XS GIS Cut Line= 4
      2987420.89     10095326.26      2987405.27     10094745.58
      2987306.31     10094578.92      2987009.74     10093587.76
#Sta/Elev= 30
  4306.9  851.53  4439.5  847.59  4599.5  844.99  4679.6  841.00  4709.6  837.53
  4731.6  832.81  4769.6  831.54  4809.6  825.19  4830.1  824.41  4849.6  823.76
  4869.6  820.83  4936.3  817.58  4994.8  812.20  5163.3  815.24  5300.9  814.40
  5327.1  812.64  5334.0  809.95  5339.3  810.70  5355.4  806.73  5358.2  806.23
  5361.4  806.73  5367.1  809.99  5372.4  810.69  5379.3  813.75  5405.5  816.42
  5619.7  826.97  5685.9  828.37  5734.2  831.87  6060.6  847.21  6116.2  851.55
#Mann=7,-1,0
  4306.9    0.05       0  4731.6     0.1       0  4830.1    0.05       0
  4936.3    0.16       0  5355.4    0.07       0  5361.4    0.16       0
  6060.6     0.1       0
Bank Sta=5355.4,5361.4
Exp/Cntr=0.3,0.1

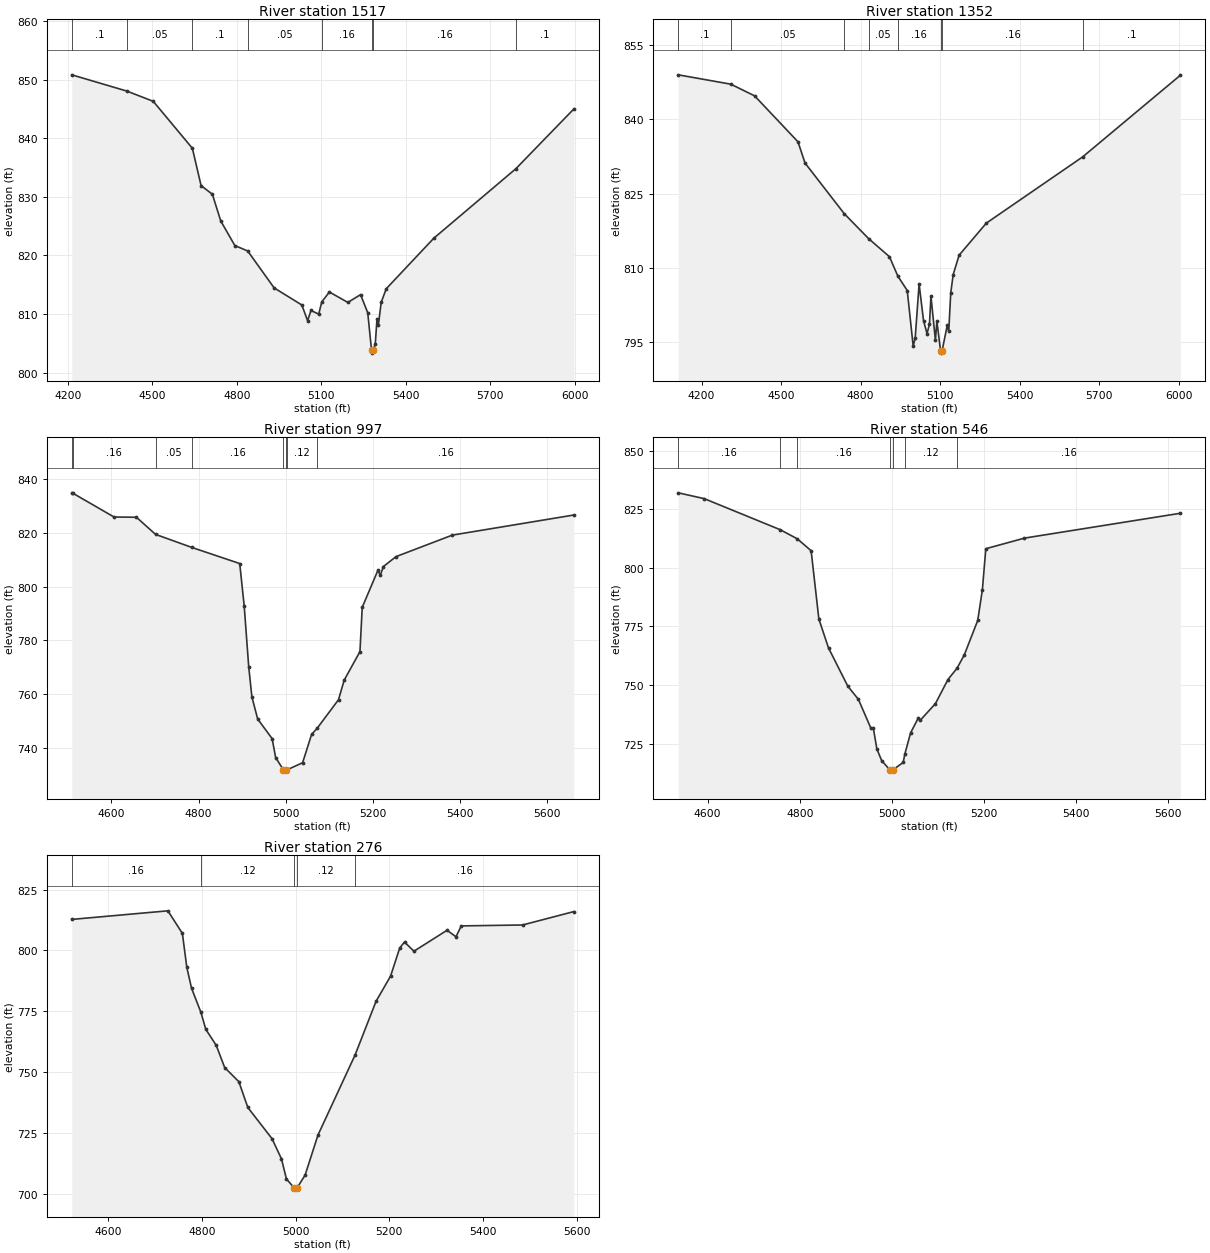
Type RM Length L Ch R = 1,1517,165,165,165
BEGIN DESCRIPTION:
Mapping XS be98134e
END DESCRIPTION:
XS GIS Cut Line= 4
      2987478.27     10095333.22      2987482.61     10094673.46
      2987363.25     10094577.97      2987078.96     10093649.13
#Sta/Elev= 30
  4213.4  850.82  4408.8  848.05  4502.9  846.30  4641.9  838.29  4672.9  831.92
  4712.9  830.45  4742.9  825.87  4792.9  821.69  4838.5  820.77  4932.4  814.47
  5030.9  811.55  5051.4  808.87  5063.3  810.62  5090.8  809.99  5101.8  812.09
  5128.8  813.77  5194.3  811.99  5239.6  813.32  5265.1  810.22  5278.5  803.84
  5281.2  803.34  5284.5  803.84  5291.9  804.92  5297.9  809.13  5303.1  808.22
  5312.8  811.99  5330.7  814.32  5499.7  822.94  5791.3  834.80  5997.4  845.00
#Mann=8,-1,0
  4213.4     0.1       0  4408.8    0.05       0  4641.9     0.1       0
  4838.5    0.05       0  5101.8    0.16       0  5278.5   0.035       0
  5284.5    0.16       0  5791.3     0.1       0
Bank Sta=5278.5,5284.5
Exp/Cntr=0.3,0.1

Type RM Length L Ch R = 1,1352,355,355,355
BEGIN DESCRIPTION:
PEDERNALES TRIB 1 3.0
END DESCRIPTION:
XS GIS Cut Line= 4
      2987534.79     10095321.15      2987576.46     10094668.34
      2987319.51     10094154.45      2987090.34     10093529.43
#Sta/Elev= 30
  4111.8  849.03  4310.1  847.14  4399.8  844.78  4563.6  835.48  4590.2  831.18
  4738.6  820.91  4830.3  815.88  4908.8  812.23  4940.6  808.28  4975.9  805.39
  4998.3  794.13  5005.9  795.78  5020.6  806.71  5037.4  799.27  5050.6  796.66
  5059.8  798.62  5065.3  804.26  5082.1  795.35  5087.7  799.19  5101.5  793.22
  5104.2  792.72  5107.5  793.22  5126.8  798.33  5132.4  797.13  5140.0  804.87
  5149.2  808.61  5171.6  812.54  5274.2  819.02  5637.6  832.42  6006.2  848.94
#Mann=8,-1,0
  4111.8     0.1       0  4310.1    0.05       0  4738.6     0.1       0
  4830.3    0.05       0  4940.6    0.16       0  5101.5    0.07       0
  5107.5    0.16       0  5637.6     0.1       0
Bank Sta=5101.5,5107.5
Exp/Cntr=0.3,0.1

Type RM Length L Ch R = 1,997,451,451,451
BEGIN DESCRIPTION:
PEDERNALES TRIB 1 2.0
END DESCRIPTION:
XS GIS Cut Line= 2
      2987913.62     10094807.78      2987635.83     10093689.67
#Sta/Elev= 30
  4508.9  835.02  4510.6  834.95  4605.8  826.01  4657.3  825.91  4701.2  819.52
  4784.7  814.64  4894.3  808.65  4904.6  792.81  4914.9  770.24  4922.2  758.94
  4935.5  750.68  4968.7  743.36  4976.7  736.32  4994.4  731.75  4997.1  731.25
  5000.4  731.75  5003.3  731.77  5038.6  734.38  5059.2  744.91  5072.5  747.34
  5121.0  757.89  5134.0  765.18  5170.2  775.82  5175.4  792.32  5211.6  806.20
  5216.7  804.22  5224.0  807.53  5252.9  811.23  5382.1  819.25  5661.0  826.75
#Mann=8,-1,0
  4508.9    0.05       0  4510.6    0.16       0  4701.2    0.05       0
  4784.7    0.16       0  4994.4    0.07       0  5000.4    0.16       0
  5003.3    0.12       0  5072.5    0.16       0
Bank Sta=4994.4,5000.4
Exp/Cntr=0.3,0.1

Type RM Length L Ch R = 1,546,270,270,270
BEGIN DESCRIPTION:
Mapping XS 4090b4c0
END DESCRIPTION:
XS GIS Cut Line= 3
      2988067.32     10094814.87      2988252.23     10094226.31
      2988174.10     10093760.14
#Sta/Elev= 30
  4536.4  832.03  4592.8  829.55  4757.5  816.31  4794.6  812.43  4824.8  807.33
  4841.6  778.17  4862.5  765.85  4904.5  749.49  4927.3  743.94  4954.5  731.60
  4959.7  731.77  4967.4  722.79  4977.8  717.79  4995.8  713.78  4998.5  713.28
  5001.8  713.78  5024.5  716.97  5028.2  720.57  5040.7  729.63  5056.9  735.75
  5062.1  735.08  5094.6  742.09  5121.7  752.35  5141.4  757.17  5157.2  762.86
  5186.4  777.60  5196.5  790.77  5203.9  808.18  5287.8  812.71  5626.0  823.31
#Mann=7,-1,0
  4536.4    0.16       0  4757.5    0.12       0  4794.6    0.16       0
  4995.8    0.07       0  5001.8    0.16       0  5028.2    0.12       0
  5141.4    0.16       0
Bank Sta=4995.8,5001.8
Exp/Cntr=0.3,0.1

Type RM Length L Ch R = 1,276,0,0,0
BEGIN DESCRIPTION:
PEDERNALES TRIB 1 1.0
END DESCRIPTION:
XS GIS Cut Line= 3
      2988524.73     10094826.88      2988399.72     10093910.18
      2988337.34     10093778.49
#Sta/Elev= 30
  4522.7  812.78  4727.7  816.31  4758.6  807.05  4768.1  793.05  4778.2  784.47
  4798.2  774.54  4808.5  767.61  4830.9  760.96  4848.8  751.88  4879.1  746.05
  4898.2  735.45  4949.8  722.62  4970.0  714.30  4980.6  706.03  4997.2  702.37
  5000.0  701.87  5003.2  702.37  5020.4  707.64  5047.9  724.14  5126.9  756.99
  5171.8  779.14  5202.6  789.42  5222.3  801.08  5232.4  803.48  5252.5  799.70
  5323.2  808.32  5342.2  805.63  5353.5  810.11  5484.3  810.49  5593.6  816.00
#Mann=5,-1,0
  4522.7    0.16       0  4798.2    0.12       0  4997.2    0.07       0
  5003.2    0.12       0  5126.9    0.16       0
Bank Sta=4997.2,5003.2
Exp/Cntr=0.3,0.1

Chan Stop Cuts=-1