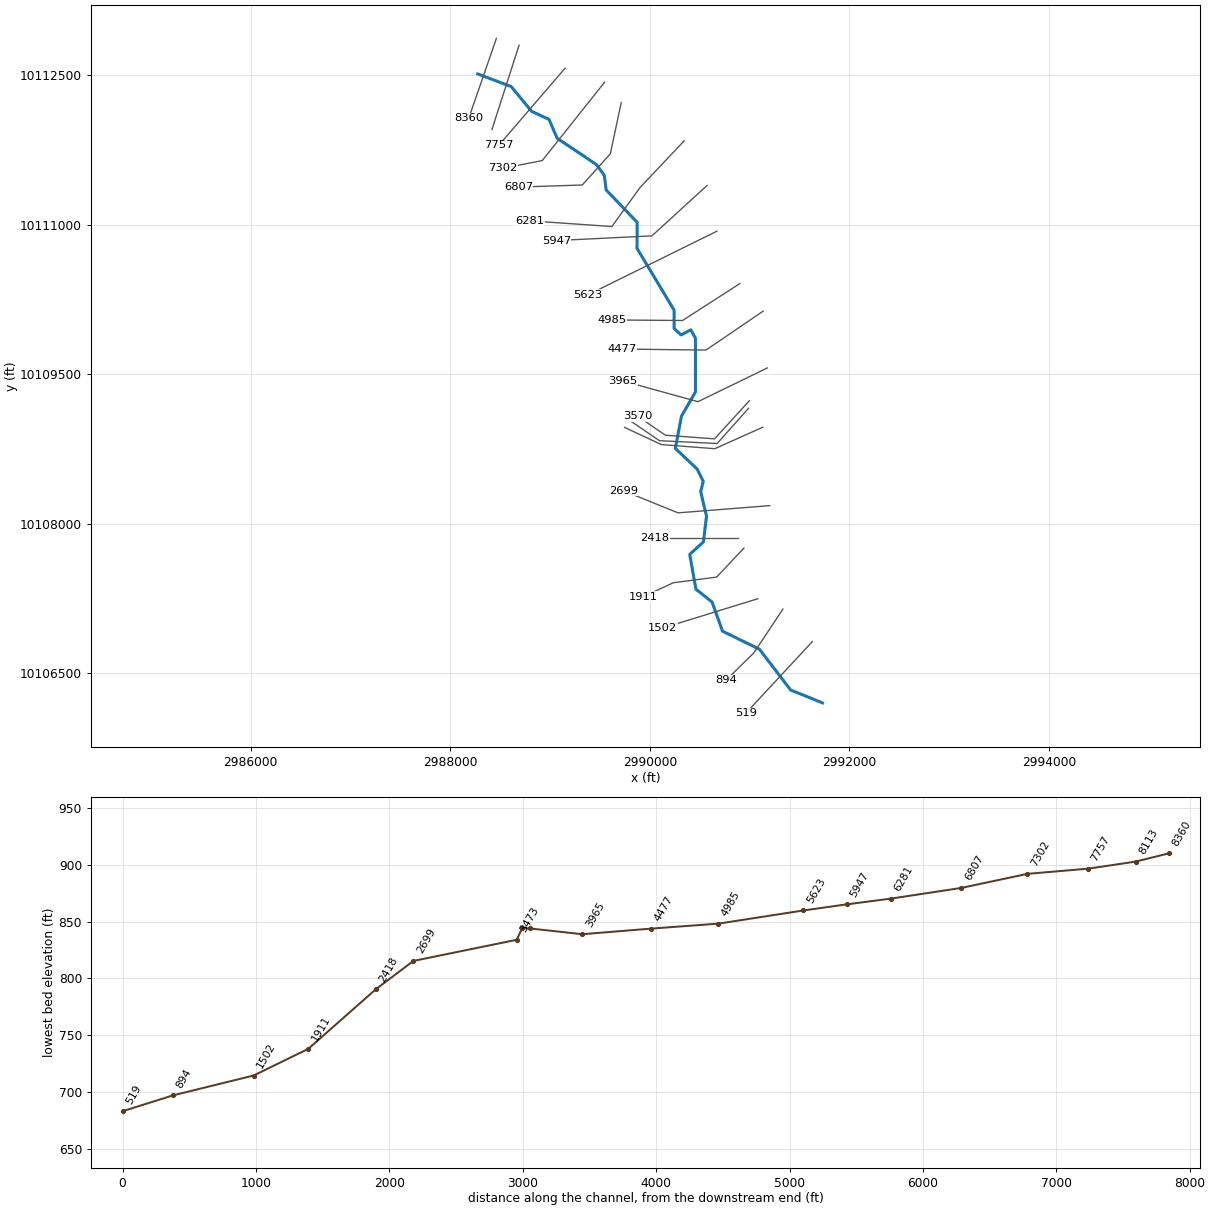
--- PEDERNALES TRIB 2.prj (project) ---

Proj Title=PEDERNALES TRIB 2 Base Level Engineering
Current Plan=p01
Default Exp/Contr=0.3,0.1
English Units
Geom File=g01
Flow File=f01
Plan File=p01
BEGIN DESCRIPTION:
PEDERNALES TRIB 2
END DESCRIPTION:

--- PEDERNALES TRIB 2.p01 (plan) ---

Plan Title=Multiple Run
Short Identifier=Multiple
Geom File=g01
Flow File=f01
Subcritical Flow
K Sum by GR= 0
Std Step Tol= 0.01
Critical Tol= 0.01
Num of Std Step Trials= 20
Max Error Tol= 0.3
Flow Tol Ratio= 0.001
Split Flow NTrial= 30
Split Flow Tol= 0.02
Split Flow Ratio= 0.02
Log Output Level= 0
Friction Slope Method= 1
Unsteady Friction Slope Method= 2
Unsteady Bridges Friction Slope Method= 1
Parabolic Critical Depth
Global Vel Dist=  1 , 1 , 1
Global Log Level= 0
CheckData=True
Encroach Param= -1, 0, 0, 0
BEGIN DESCRIPTION:
Multiple Run
END DESCRIPTION:

--- PEDERNALES TRIB 2.f01 (steady flow) ---

Flow Title=Multiple
Number of Profiles=7
Profile Names=10-year,25-year,50-year,1pct_min,100-year,1pct_plu,500-year
River Rch & RM= PEDERNALES TRIB ,Reach-1,8360
     862    1257    1603    1499    2027    2742    3251
River Rch & RM= PEDERNALES TRIB ,Reach-1,1911
    1463    2202    2867    2733    3696    4998    6165
Boundary for River Rch & Prof#=PEDERNALES TRIB ,Reach-1,1
Up Type=0
Dn Type=3
Dn Slope=0.005
Boundary for River Rch & Prof#=PEDERNALES TRIB ,Reach-1,2
Up Type=0
Dn Type=3
Dn Slope=0.005
Boundary for River Rch & Prof#=PEDERNALES TRIB ,Reach-1,3
Up Type=0
Dn Type=3
Dn Slope=0.005
Boundary for River Rch & Prof#=PEDERNALES TRIB ,Reach-1,4
Up Type=0
Dn Type=3
Dn Slope=0.005
Boundary for River Rch & Prof#=PEDERNALES TRIB ,Reach-1,5
Up Type=0
Dn Type=3
Dn Slope=0.005
Boundary for River Rch & Prof#=PEDERNALES TRIB ,Reach-1,6
Up Type=0
Dn Type=3
Dn Slope=0.005
Boundary for River Rch & Prof#=PEDERNALES TRIB ,Reach-1,7
Up Type=0
Dn Type=3
Dn Slope=0.005

--- PEDERNALES TRIB 2.g01 (geometry) ---

Geom Title=Existing Conditions

River Reach=PEDERNALES TRIB ,Reach-1
Reach XY= 30
      2988276.36     10112514.75      2988611.10     10112388.37
      2988816.90     10112139.04      2988990.36     10112058.62
      2989071.61     10111870.45      2989467.37     10111604.06
      2989544.23     10111496.59      2989563.17     10111350.91
      2989873.21     10111026.20      2989872.00     10110765.30
      2990243.17     10110146.27      2990243.92     10109960.98
      2990314.05     10109896.32      2990411.16     10109947.70
      2990457.49     10109863.40      2990457.42     10109324.17
      2990317.50     10109081.75      2990255.87     10108757.53
      2990474.42     10108551.00      2990535.53     10108428.05
      2990509.86     10108324.09      2990568.29     10108076.47
      2990536.85     10107819.38      2990400.14     10107694.39
      2990462.00     10107345.17      2990624.06     10107216.79
      2990728.54     10106924.22      2991098.85     10106742.84
      2991410.83     10106333.89      2991730.23     10106204.65

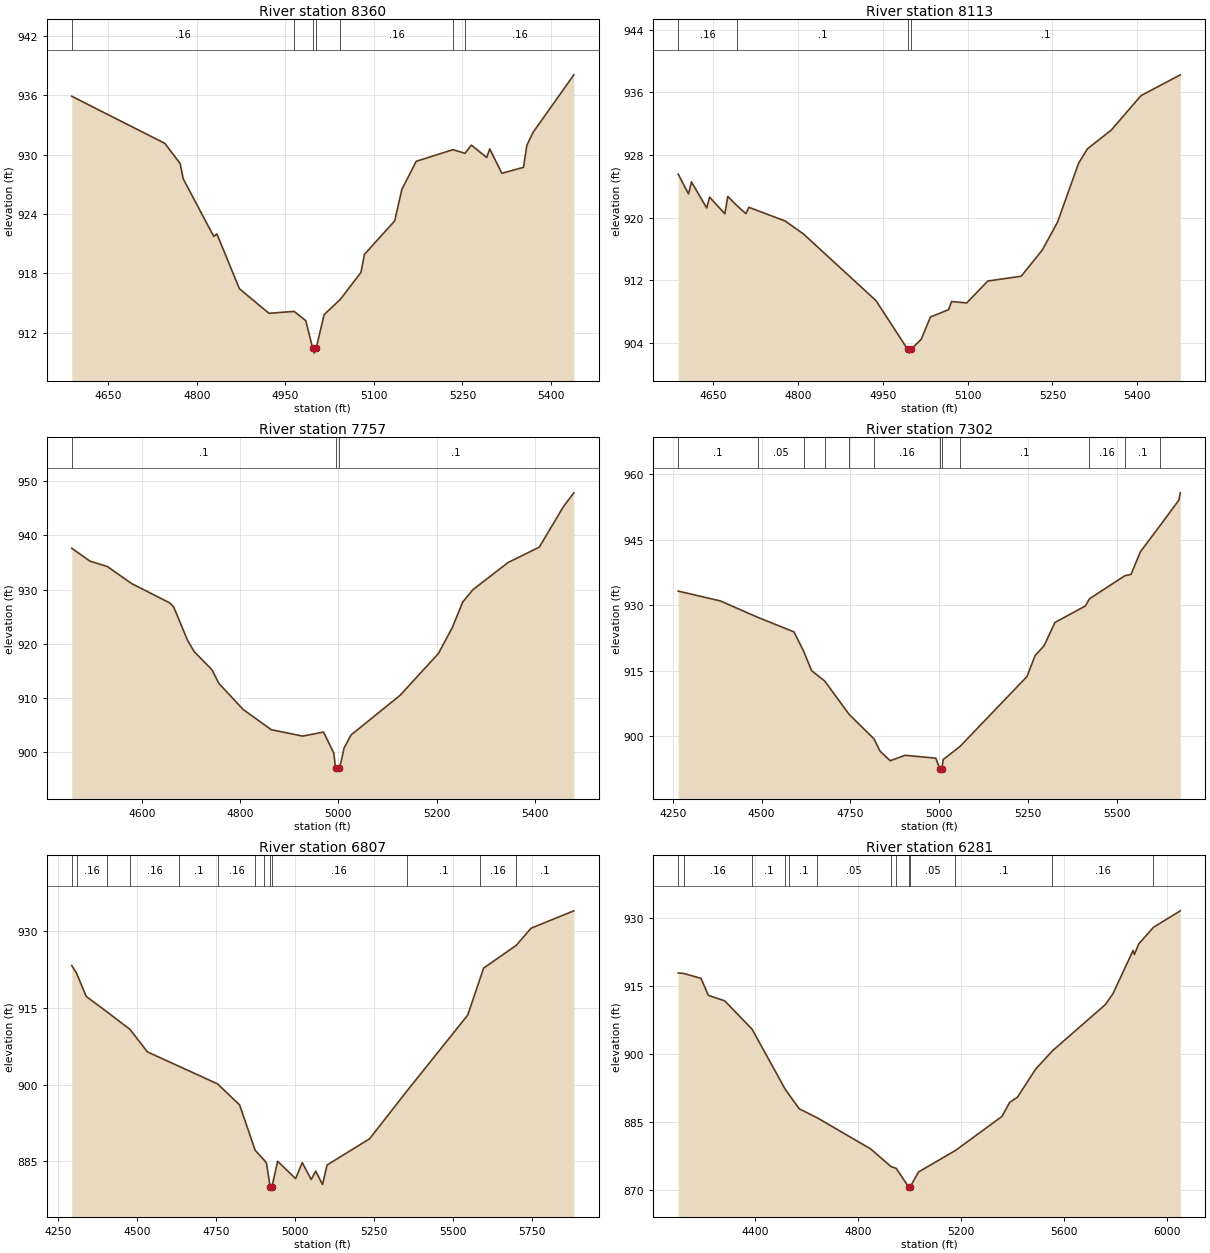
Type RM Length L Ch R = 1,8360,247,247,247
BEGIN DESCRIPTION:
PEDERNALES TRIB 2 6.0
END DESCRIPTION:
XS GIS Cut Line= 2
      2988463.42     10112872.15      2988185.46     10112068.46
#Sta/Elev= 30
  4588.2  935.90  4745.8  931.14  4771.7  929.11  4777.0  927.55  4828.7  921.72
  4834.0  921.98  4872.2  916.43  4922.2  913.95  4964.9  914.14  4984.6  913.20
  4996.2  910.42  4998.9  909.92  5002.2  910.42  5015.7  913.82  5043.1  915.36
  5078.1  918.09  5083.8  919.90  5135.1  923.29  5147.3  926.48  5171.6  929.32
  5233.9  930.50  5254.2  930.13  5265.1  930.96  5290.9  929.71  5296.2  930.58
  5316.6  928.11  5353.3  928.71  5359.0  930.94  5369.5  932.25  5438.6  938.07
#Mann=7,-1,0
  4588.2    0.16       0  4964.9     0.1       0  4996.2    0.07       0
  5002.2     0.1       0  5043.1    0.16       0  5233.9     0.1       0
  5254.2    0.16       0
Bank Sta=4996.2,5002.2
Exp/Cntr=0.3,0.1

Type RM Length L Ch R = 1,8113,356,356,356
BEGIN DESCRIPTION:
PEDERNALES TRIB 2 18.0
END DESCRIPTION:
XS GIS Cut Line= 2
      2988690.13     10112802.60      2988418.48     10111957.49
#Sta/Elev= 30
  4588.3  925.56  4606.5  923.04  4611.7  924.58  4638.6  921.25  4643.8  922.63
  4670.7  920.50  4675.9  922.72  4692.1  921.54  4708.0  920.52  4713.3  921.33
  4777.4  919.58  4809.5  917.94  4937.9  909.42  4993.8  903.21  4996.5  902.71
  4999.8  903.21  5017.8  904.46  5034.2  907.32  5066.3  908.26  5071.6  909.30
  5098.4  909.12  5135.7  911.92  5194.7  912.53  5232.0  915.88  5258.9  919.43
  5296.2  926.97  5311.9  928.81  5353.9  931.19  5406.4  935.59  5476.0  938.25
#Mann=4,-1,0
  4588.3    0.16       0  4692.1     0.1       0  4993.8    0.07       0
  4999.8     0.1       0
Bank Sta=4993.8,4999.8
Exp/Cntr=0.3,0.1

Type RM Length L Ch R = 1,7757,455,455,455
BEGIN DESCRIPTION:
PEDERNALES TRIB 2 17.0
END DESCRIPTION:
XS GIS Cut Line= 2
      2989151.48     10112572.53      2988485.77     10111797.61
#Sta/Elev= 30
  4457.6  937.64  4494.8  935.25  4529.9  934.27  4579.3  931.12  4657.2  927.54
  4664.9  926.81  4693.3  920.64  4706.6  918.57  4742.8  915.22  4757.1  912.68
  4806.4  907.88  4863.5  904.16  4927.2  902.97  4969.9  903.72  4990.8  899.84
  4994.4  897.01  4997.1  896.51  5000.4  897.01  5005.1  898.05  5011.7  900.77
  5025.9  903.19  5125.8  910.51  5203.7  918.22  5232.2  923.06  5253.1  927.71
  5273.9  929.99  5345.3  935.00  5408.9  937.84  5458.3  945.36  5479.2  947.86
#Mann=3,-1,0
  4457.6     0.1       0  4994.4    0.07       0  5000.4     0.1       0
Bank Sta=4994.4,5000.4
Exp/Cntr=0.3,0.1

Type RM Length L Ch R = 1,7302,495,495,495
BEGIN DESCRIPTION:
PEDERNALES TRIB 2 16.0
END DESCRIPTION:
XS GIS Cut Line= 3
      2989547.29     10112431.89      2988922.29     10111645.43
      2988522.37     10111567.52
#Sta/Elev= 30
  4265.6  933.20  4384.4  930.94  4488.7  927.21  4591.1  923.86  4618.6  919.38
  4640.7  914.97  4677.4  912.61  4746.6  904.92  4816.2  899.34  4833.0  896.55
  4861.8  894.32  4903.4  895.58  4990.0  894.92  5001.1  892.45  5003.8  891.95
  5007.1  892.45  5010.8  894.62  5057.0  897.52  5246.3  913.62  5269.2  918.42
  5294.4  920.68  5325.0  926.01  5410.7  929.80  5422.1  931.44  5521.8  936.73
  5538.9  937.02  5565.5  942.23  5621.6  948.32  5673.9  954.10  5677.6  955.72
#Mann=12,-1,0
  4265.6     0.1       0  4488.7    0.05       0  4618.6     0.1       0
  4677.4    0.05       0  4746.6     0.1       0  4816.2    0.16       0
  5001.1    0.07       0  5007.1    0.16       0  5057.0     0.1       0
  5422.1    0.16       0  5521.8     0.1       0  5621.6    0.05       0
Bank Sta=5001.1,5007.1
Exp/Cntr=0.3,0.1

Type RM Length L Ch R = 1,6807,526,526,526
BEGIN DESCRIPTION:
PEDERNALES TRIB 2 15.0
END DESCRIPTION:
XS GIS Cut Line= 4
      2989713.96     10112228.76      2989604.58     10111713.14
      2989323.33     10111400.64      2988683.09     10111379.81
#Sta/Elev= 30
  4293.8  923.26  4308.9  921.78  4339.5  917.23  4406.5  914.16  4478.1  910.78
  4533.0  906.40  4633.7  903.56  4755.1  900.14  4824.7  896.04  4874.1  887.16
  4902.8  885.23  4909.9  884.63  4921.1  880.09  4923.8  879.59  4927.1  880.09
  4945.0  885.03  5001.8  881.64  5022.8  884.76  5051.2  881.47  5065.4  883.11
  5087.0  880.49  5101.2  884.30  5235.8  889.42  5353.0  898.68  5546.3  913.59
  5584.9  920.64  5596.4  922.76  5699.8  927.21  5746.5  930.55  5881.9  933.95
#Mann=13,-1,0
  4293.8     0.1       0  4308.9    0.16       0  4406.5     0.1       0
  4478.1    0.16       0  4633.7     0.1       0  4755.1    0.16       0
  4874.1     0.1       0  4902.8    0.16       0  4921.1    0.07       0
  4927.1    0.16       0  5353.0     0.1       0  5584.9    0.16       0
  5699.8     0.1       0
Bank Sta=4921.1,4927.1
Exp/Cntr=0.3,0.1

Type RM Length L Ch R = 1,6281,334,334,334
BEGIN DESCRIPTION:
PEDERNALES TRIB 2 14.0
END DESCRIPTION:
XS GIS Cut Line= 4
      2990344.15     10111843.33      2989901.46     10111374.59
      2989620.21     10110983.97      2988797.28     10111041.26
#Sta/Elev= 30
  4100.0  917.88  4122.3  917.75  4188.6  916.68  4216.9  912.94  4280.4  911.73
  4387.1  905.47  4514.9  892.31  4531.6  890.97  4570.5  887.91  4641.0  885.91
  4847.3  879.09  4927.3  875.17  4946.9  874.79  4995.2  870.71  4998.0  870.21
  5001.2  870.71  5033.8  874.00  5177.2  878.73  5358.1  886.25  5388.2  889.35
  5418.3  890.49  5488.5  896.65  5554.1  900.71  5759.1  910.86  5789.2  913.30
  5867.5  922.83  5872.5  921.95  5889.4  924.28  5946.8  927.94  6051.0  931.57
#Mann=13,-1,0
  4100.0     0.1       0  4122.3    0.16       0  4387.1     0.1       0
  4514.9    0.05       0  4531.6     0.1       0  4641.0    0.05       0
  4927.3     0.1       0  4946.9    0.05       0  4995.2   0.035       0
  5001.2    0.05       0  5177.2     0.1       0  5554.1    0.16       0
  5946.8     0.1       0
Bank Sta=4995.2,5001.2
Exp/Cntr=0.3,0.1

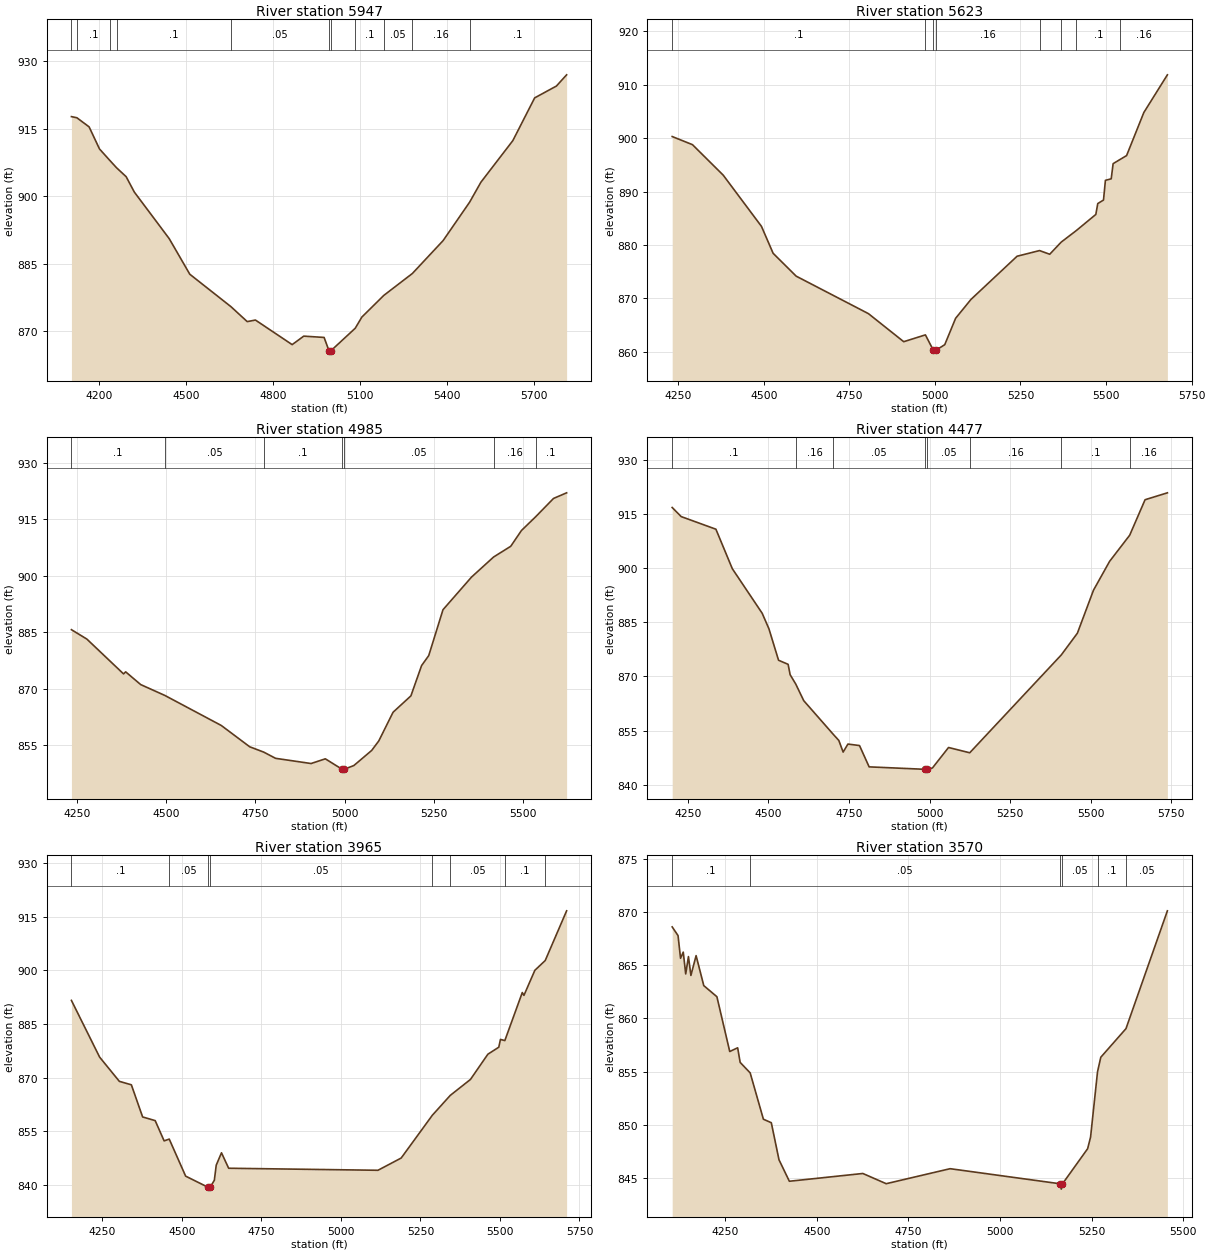
Type RM Length L Ch R = 1,5947,324,324,324
BEGIN DESCRIPTION:
PEDERNALES TRIB 2 13.0
END DESCRIPTION:
XS GIS Cut Line= 3
      2990573.36     10111395.45      2990021.25     10110890.22
      2989063.19     10110843.36
#Sta/Elev= 30
  4104.0  917.73  4122.8  917.48  4165.0  915.45  4200.8  910.54  4236.8  907.96
  4259.7  906.35  4292.7  904.37  4321.0  900.94  4441.3  890.58  4512.2  882.67
  4654.2  875.45  4710.2  872.13  4738.5  872.48  4865.2  867.01  4905.2  868.90
  4975.3  868.61  4992.3  865.62  4995.1  865.12  4998.3  865.62  5082.6  870.65
  5105.5  873.14  5181.2  877.96  5279.8  882.84  5385.8  890.16  5477.1  898.70
  5516.0  903.14  5626.1  912.39  5701.4  921.90  5776.3  924.53  5811.6  927.03
#Mann=11,-1,0
  4104.0    0.05       0  4122.8     0.1       0  4236.8    0.16       0
  4259.7     0.1       0  4654.2    0.05       0  4992.3   0.035       0
  4998.3    0.05       0  5082.6     0.1       0  5181.2    0.05       0
  5279.8    0.16       0  5477.1     0.1       0
Bank Sta=4992.3,4998.3
Exp/Cntr=0.3,0.1

Type RM Length L Ch R = 1,5623,638,638,638
BEGIN DESCRIPTION:
PEDERNALES TRIB 2 12.0
END DESCRIPTION:
XS GIS Cut Line= 2
      2990672.25     10110937.07      2989375.44     10110296.48
#Sta/Elev= 30
  4232.7  900.32  4291.9  898.80  4381.7  893.09  4493.5  883.49  4527.5  878.45
  4594.8  874.17  4805.8  867.15  4909.0  861.89  4972.3  863.17  4995.8  860.25
  4998.5  859.75  5001.8  860.25  5028.8  861.33  5060.5  866.27  5105.4  869.81
  5240.1  877.90  5305.7  878.96  5335.4  878.27  5368.7  880.53  5413.5  882.73
  5470.1  885.73  5475.7  887.76  5492.5  888.43  5498.1  892.12  5515.0  892.40
  5520.6  895.24  5541.0  896.03  5559.9  896.75  5610.3  904.82  5679.1  911.88
#Mann=8,-1,0
  4232.7     0.1       0  4972.3    0.16       0  4995.8    0.07       0
  5001.8    0.16       0  5305.7     0.1       0  5368.7    0.16       0
  5413.5     0.1       0  5541.0    0.16       0
Bank Sta=4995.8,5001.8
Exp/Cntr=0.3,0.1

Type RM Length L Ch R = 1,4985,508,508,508
BEGIN DESCRIPTION:
PEDERNALES TRIB 2 11.0
END DESCRIPTION:
XS GIS Cut Line= 3
      2990901.50     10110411.08      2990328.54     10110041.26
      2989621.80     10110046.46
#Sta/Elev= 30
  4233.9  885.73  4277.1  883.24  4380.1  873.98  4386.0  874.53  4428.3  871.14
  4496.0  868.26  4654.1  860.29  4733.8  854.63  4773.4  853.20  4806.4  851.56
  4906.0  850.18  4945.9  851.43  4992.9  848.66  4995.7  848.16  4998.9  848.66
  5025.9  849.64  5075.9  853.65  5095.9  856.19  5135.9  863.80  5185.9  868.15
  5215.9  876.20  5235.9  878.84  5275.9  891.03  5355.9  899.70  5417.8  905.03
  5465.9  907.88  5495.9  912.07  5535.9  915.74  5585.9  920.59  5622.6  922.08
#Mann=7,-1,0
  4233.9     0.1       0  4496.0    0.05       0  4773.4     0.1       0
  4992.9    0.07       0  4998.9    0.05       0  5417.8    0.16       0
  5535.9     0.1       0
Bank Sta=4992.9,4998.9
Exp/Cntr=0.3,0.1

Type RM Length L Ch R = 1,4477,512,512,512
BEGIN DESCRIPTION:
PEDERNALES TRIB 2 10.0
END DESCRIPTION:
XS GIS Cut Line= 3
      2991135.86     10110135.03      2990562.92     10109744.39
      2989719.13     10109754.80
#Sta/Elev= 30
  4201.1  916.73  4229.1  914.21  4336.8  910.72  4387.7  899.80  4480.5  887.45
  4501.4  883.17  4531.3  874.45  4561.0  873.32  4567.2  870.46  4584.8  867.84
  4609.5  863.26  4700.9  853.97  4718.4  852.25  4731.8  849.03  4746.7  851.25
  4782.6  850.84  4812.5  844.94  4986.0  844.26  4988.8  843.76  4992.0  844.26
  5009.0  844.63  5059.0  850.30  5124.8  848.84  5409.0  875.92  5459.0  881.94
  5509.0  893.84  5559.0  901.82  5621.4  909.06  5669.1  918.88  5738.4  920.79
#Mann=8,-1,0
  4201.1     0.1       0  4584.8    0.16       0  4700.9    0.05       0
  4986.0   0.035       0  4992.0    0.05       0  5124.8    0.16       0
  5409.0     0.1       0  5621.4    0.16       0
Bank Sta=4986,4992
Exp/Cntr=0.3,0.1

Type RM Length L Ch R = 1,3965,395,395,395
BEGIN DESCRIPTION:
Mapping XS 35c6b243
END DESCRIPTION:
XS GIS Cut Line= 3
      2991177.90     10109565.25      2990482.65     10109226.70
      2989727.00     10109435.25
#Sta/Elev= 30
  4152.4  891.63  4241.1  875.77  4303.1  869.00  4340.9  868.03  4376.3  859.04
  4415.8  858.02  4443.9  852.35  4460.0  852.85  4511.6  842.49  4582.5  839.36
  4585.3  838.86  4588.5  839.36  4601.8  841.34  4607.8  845.57  4624.3  849.02
  4646.8  844.70  5116.4  844.13  5189.4  847.56  5287.2  859.50  5343.7  865.07
  5407.2  869.53  5461.9  876.58  5496.3  878.55  5501.5  880.72  5515.3  880.40
  5570.2  893.83  5575.4  893.04  5609.7  900.05  5642.3  902.78  5709.6  916.68
#Mann=8,-1,0
  4152.4     0.1       0  4460.0    0.05       0  4582.5    0.03       0
  4588.5    0.05       0  5287.2     0.1       0  5343.7    0.05       0
  5515.3     0.1       0  5642.3    0.05       0
Bank Sta=4582.5,4588.5
Exp/Cntr=0.3,0.1

Type RM Length L Ch R = 1,3570,55,55,55
BEGIN DESCRIPTION:
PEDERNALES TRIB 2 9.0
END DESCRIPTION:
XS GIS Cut Line= 4
      2990997.84     10109236.60      2990648.85     10108853.76
      2990156.67     10108890.22      2989875.42     10109082.92
#Sta/Elev= 30
  4104.6  868.60  4120.6  867.78  4127.4  865.65  4134.8  866.23  4141.5  864.18
  4149.0  865.81  4155.7  864.04  4169.9  865.90  4190.9  863.08  4226.7  862.04
  4261.8  856.89  4283.4  857.24  4290.2  855.87  4317.6  854.88  4353.7  850.53
  4375.3  850.20  4396.3  846.72  4424.6  844.70  4625.3  845.43  4689.1  844.47
  4863.7  845.88  5164.6  844.46  5167.3  843.96  5170.6  844.46  5239.3  847.76
  5247.3  848.85  5266.3  854.99  5275.2  856.35  5344.0  859.04  5457.1  870.11
#Mann=6,-1,0
  4104.6     0.1       0  4317.6    0.05       0  5164.6   0.033       0
  5170.6    0.05       0  5266.3     0.1       0  5344.0    0.05       0
Bank Sta=5164.6,5170.6
Exp/Cntr=0.3,0.1

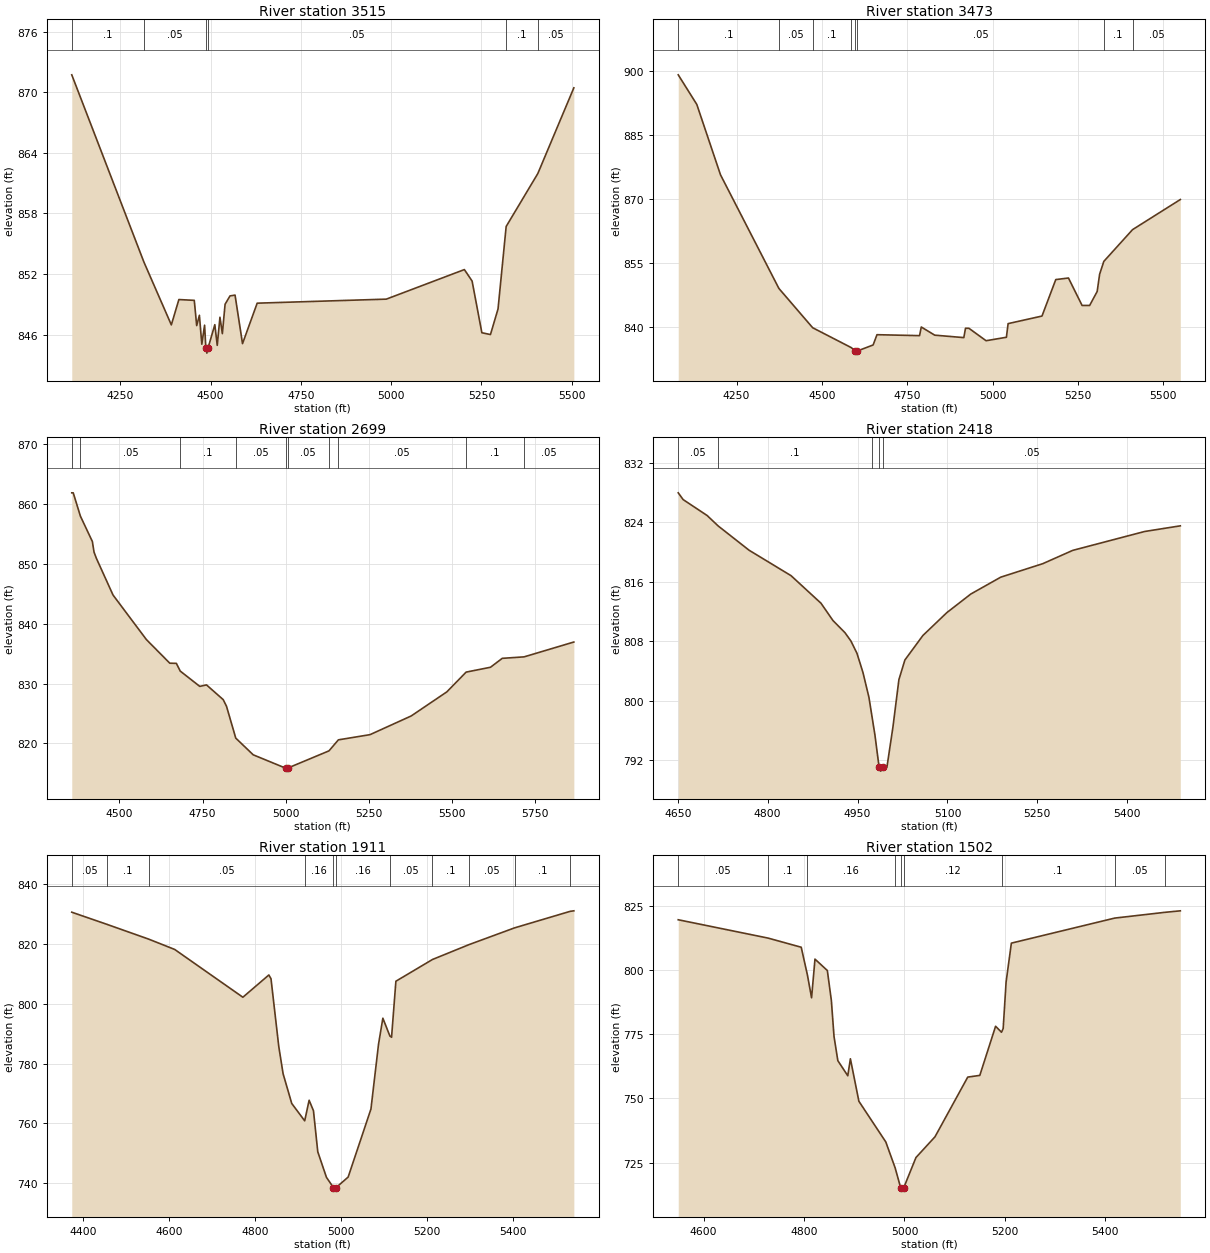
Type RM Length L Ch R = 1,3515,42,42,42
BEGIN DESCRIPTION:
PEDERNALES TRIB 2 8.0
END DESCRIPTION:
XS GIS Cut Line= 4
      2990989.97     10109161.02      2990674.90     10108806.89
      2990096.77     10108835.53      2989818.10     10109025.66
#Sta/Elev= 30
  4115.8  871.74  4315.5  853.19  4391.5  846.96  4412.4  849.47  4455.0  849.39
  4461.7  846.89  4469.2  847.91  4475.9  845.04  4483.5  846.93  4487.1  844.66
  4489.9  844.16  4493.1  844.66  4511.9  846.98  4518.6  844.93  4526.1  847.72
  4532.8  846.09  4540.3  849.00  4553.9  849.83  4567.9  849.91  4588.6  845.10
  4629.2  849.11  4986.7  849.51  5202.9  852.44  5224.3  851.30  5251.3  846.18
  5275.1  846.00  5296.1  848.54  5318.6  856.71  5406.3  861.96  5506.0  870.45
#Mann=6,-1,0
  4115.8     0.1       0  4315.5    0.05       0  4487.1    0.03       0
  4493.1    0.05       0  5318.6     0.1       0  5406.3    0.05       0
Bank Sta=4487.1,4493.1
Exp/Cntr=0.3,0.1

Type RM Length L Ch R = 1,3473,774,774,774
BEGIN DESCRIPTION:
PEDERNALES TRIB 2 7.0
END DESCRIPTION:
XS GIS Cut Line= 4
      2991133.24     10108970.95      2990651.46     10108754.80
      2990115.00     10108796.47      2989747.85     10108968.33
#Sta/Elev= 30
  4078.9  899.04  4133.3  892.12  4202.8  875.65  4373.9  849.08  4472.9  839.89
  4586.2  835.23  4598.0  834.45  4600.8  833.95  4604.0  834.45  4650.1  835.86
  4661.4  838.26  4786.2  838.04  4791.2  840.06  4830.6  838.15  4915.9  837.58
  4920.9  839.77  4930.9  839.76  4981.1  836.85  5040.7  837.66  5045.7  840.85
  5145.0  842.62  5185.4  851.15  5222.6  851.52  5262.6  845.09  5284.7  845.10
  5306.8  848.38  5313.9  852.40  5326.2  855.40  5410.4  862.83  5550.4  869.87
#Mann=8,-1,0
  4078.9     0.1       0  4373.9    0.05       0  4472.9     0.1       0
  4586.2    0.05       0  4598.0    0.03       0  4604.0    0.05       0
  5326.2     0.1       0  5410.4    0.05       0
Bank Sta=4598,4604
Exp/Cntr=0.3,0.1

Type RM Length L Ch R = 1,2699,281,281,281
BEGIN DESCRIPTION:
Mapping XS 168d088e
END DESCRIPTION:
XS GIS Cut Line= 3
      2991202.12     10108183.84      2990283.15     10108111.29
      2989739.02     10108331.96
#Sta/Elev= 30
  4356.6  861.90  4361.0  861.90  4382.5  858.01  4418.5  853.76  4423.5  851.99
  4430.5  850.96  4480.6  844.81  4580.9  837.36  4651.2  833.41  4670.9  833.38
  4682.6  832.09  4741.4  829.53  4761.5  829.78  4811.7  827.32  4821.7  826.20
  4849.5  820.88  4901.9  818.09  4999.3  815.86  5002.0  815.36  5005.3  815.86
  5129.7  818.75  5157.9  820.59  5253.0  821.46  5376.6  824.58  5483.8  828.61
  5541.9  831.92  5615.1  832.73  5650.4  834.22  5716.2  834.47  5865.6  836.95
#Mann=10,-1,0
  4356.6     0.1       0  4382.5    0.05       0  4682.6     0.1       0
  4849.5    0.05       0  4999.3   0.035       0  5005.3    0.05       0
  5129.7     0.1       0  5157.9    0.05       0  5541.9     0.1       0
  5716.2    0.05       0
Bank Sta=4999.3,5005.3
Exp/Cntr=0.3,0.1

Type RM Length L Ch R = 1,2418,507,507,507
BEGIN DESCRIPTION:
PEDERNALES TRIB 2 5.0
END DESCRIPTION:
XS GIS Cut Line= 2
      2990886.70     10107857.23      2990049.00     10107857.23
#Sta/Elev= 30
  4650.8  827.94  4659.0  827.03  4699.0  824.89  4717.5  823.48  4769.0  820.22
  4839.0  816.80  4889.0  813.09  4909.0  810.76  4929.0  809.13  4939.0  808.00
  4949.0  806.36  4959.0  803.78  4969.0  800.43  4973.7  798.05  4979.0  795.36
  4986.0  791.01  4988.8  790.51  4992.0  791.01  4999.0  791.04  5009.0  796.42
  5019.0  802.82  5029.0  805.46  5059.0  808.75  5099.0  811.83  5139.0  814.33
  5189.0  816.60  5259.0  818.41  5309.0  820.20  5429.0  822.74  5488.5  823.50
#Mann=5,-1,0
  4650.8    0.05       0  4717.5     0.1       0  4973.7    0.05       0
  4986.0   0.035       0  4992.0    0.05       0
Bank Sta=4986,4992
Exp/Cntr=0.3,0.1

Type RM Length L Ch R = 1,1911,409,409,409
BEGIN DESCRIPTION:
PEDERNALES TRIB 2 4.0
END DESCRIPTION:
XS GIS Cut Line= 4
      2990943.14     10107757.42      2990669.69     10107466.61
      2990235.66     10107410.18      2989936.16     10107271.29
#Sta/Elev= 30
  4374.5  830.57  4456.1  826.52  4553.0  821.59  4613.7  818.13  4772.2  802.16
  4832.6  809.60  4837.6  808.34  4855.6  785.75  4865.7  776.60  4885.8  766.67
  4915.9  760.87  4926.2  767.74  4936.3  764.23  4946.3  750.53  4966.5  741.98
  4982.8  738.55  4985.5  738.05  4988.8  738.55  5016.9  742.08  5069.9  764.80
  5087.5  786.44  5097.6  795.16  5113.9  789.21  5117.8  788.80  5127.9  807.51
  5212.9  814.77  5297.7  819.73  5403.8  825.34  5533.0  830.86  5541.5  831.03
#Mann=11,-1,0
  4374.5    0.05       0  4456.1     0.1       0  4553.0    0.05       0
  4915.9    0.16       0  4982.8    0.07       0  4988.8    0.16       0
  5113.9    0.05       0  5212.9     0.1       0  5297.7    0.05       0
  5403.8     0.1       0  5533.0    0.05       0
Bank Sta=4982.8,4988.8
Exp/Cntr=0.3,0.1

Type RM Length L Ch R = 1,1502,608,608,608
BEGIN DESCRIPTION:
PEDERNALES TRIB 2 3.0
END DESCRIPTION:
XS GIS Cut Line= 2
      2991081.98     10107249.58      2990127.15     10106954.46
#Sta/Elev= 30
  4549.7  819.66  4728.7  812.50  4794.5  808.94  4806.8  798.17  4815.1  789.23
  4821.9  804.31  4846.5  799.87  4854.5  788.20  4859.8  774.14  4867.4  764.71
  4887.2  758.83  4892.4  765.45  4909.3  748.88  4962.9  733.01  4981.5  722.89
  4992.5  715.12  4995.3  714.62  4998.5  715.12  5022.9  726.94  5060.8  735.03
  5126.0  758.31  5150.0  758.97  5181.4  778.13  5193.2  775.79  5196.5  777.24
  5202.3  795.31  5212.8  810.54  5418.6  820.31  5518.7  822.56  5549.1  823.14
#Mann=9,-1,0
  4549.7    0.05       0  4728.7     0.1       0  4806.8    0.16       0
  4981.5    0.12       0  4992.5    0.07       0  4998.5    0.12       0
  5193.2     0.1       0  5418.6    0.05       0  5518.7     0.1       0
Bank Sta=4992.5,4998.5
Exp/Cntr=0.3,0.1

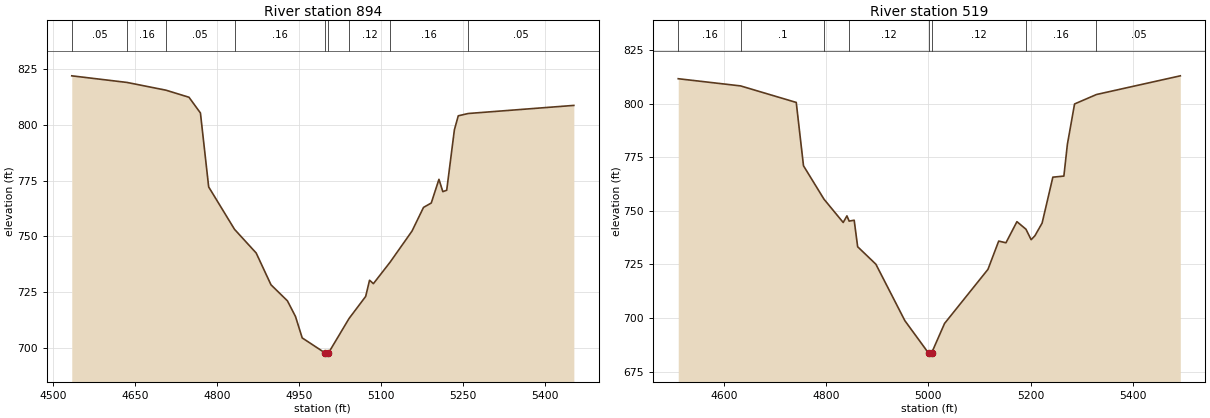
Type RM Length L Ch R = 1,894,375,375,375
BEGIN DESCRIPTION:
PEDERNALES TRIB 2 2.0
END DESCRIPTION:
XS GIS Cut Line= 3
      2991333.73     10107145.40      2991042.95     10106707.06
      2990762.14     10106430.57
#Sta/Elev= 30
  4533.5  822.01  4634.7  819.04  4706.0  815.57  4748.3  812.39  4769.3  805.32
  4784.4  772.12  4831.8  753.08  4871.5  742.44  4898.6  728.18  4928.7  720.98
  4943.5  713.95  4955.8  704.33  4997.9  697.55  5000.7  697.05  5003.9  697.55
  5041.6  713.03  5072.1  722.95  5079.2  730.23  5086.3  728.70  5116.9  738.35
  5157.0  752.29  5178.1  762.93  5192.3  764.90  5206.4  775.54  5213.5  770.02
  5220.6  770.62  5234.7  797.78  5241.8  804.06  5260.0  805.09  5453.6  808.73
#Mann=9,-1,0
  4533.5    0.05       0  4634.7    0.16       0  4706.0    0.05       0
  4831.8    0.16       0  4997.9    0.07       0  5003.9    0.16       0
  5041.6    0.12       0  5116.9    0.16       0  5260.0    0.05       0
Bank Sta=4997.9,5003.9
Exp/Cntr=0.3,0.1

Type RM Length L Ch R = 1,519,0,0,0
BEGIN DESCRIPTION:
PEDERNALES TRIB 2 1.0
END DESCRIPTION:
XS GIS Cut Line= 2
      2991628.90     10106819.92      2990960.49     10106099.42
#Sta/Elev= 30
  4510.3  811.63  4632.3  808.28  4741.3  800.57  4755.5  771.03  4795.6  755.46
  4833.2  744.59  4840.5  747.67  4844.9  745.22  4854.7  745.65  4861.5  733.28
  4897.2  725.13  4953.9  698.81  5000.2  683.70  5003.0  683.20  5006.2  683.70
  5031.6  697.49  5116.6  722.74  5137.6  735.92  5151.8  735.12  5173.3  744.97
  5191.0  741.44  5201.1  736.56  5208.5  738.40  5222.6  744.32  5243.6  765.72
  5265.2  766.23  5272.0  780.96  5286.1  799.86  5329.0  804.27  5493.1  812.98
#Mann=8,-1,0
  4510.3    0.16       0  4632.3     0.1       0  4795.6    0.16       0
  4844.9    0.12       0  5000.2    0.07       0  5006.2    0.12       0
  5191.0    0.16       0  5329.0    0.05       0
Bank Sta=5000.2,5006.2
Exp/Cntr=0.3,0.1

Chan Stop Cuts=-1