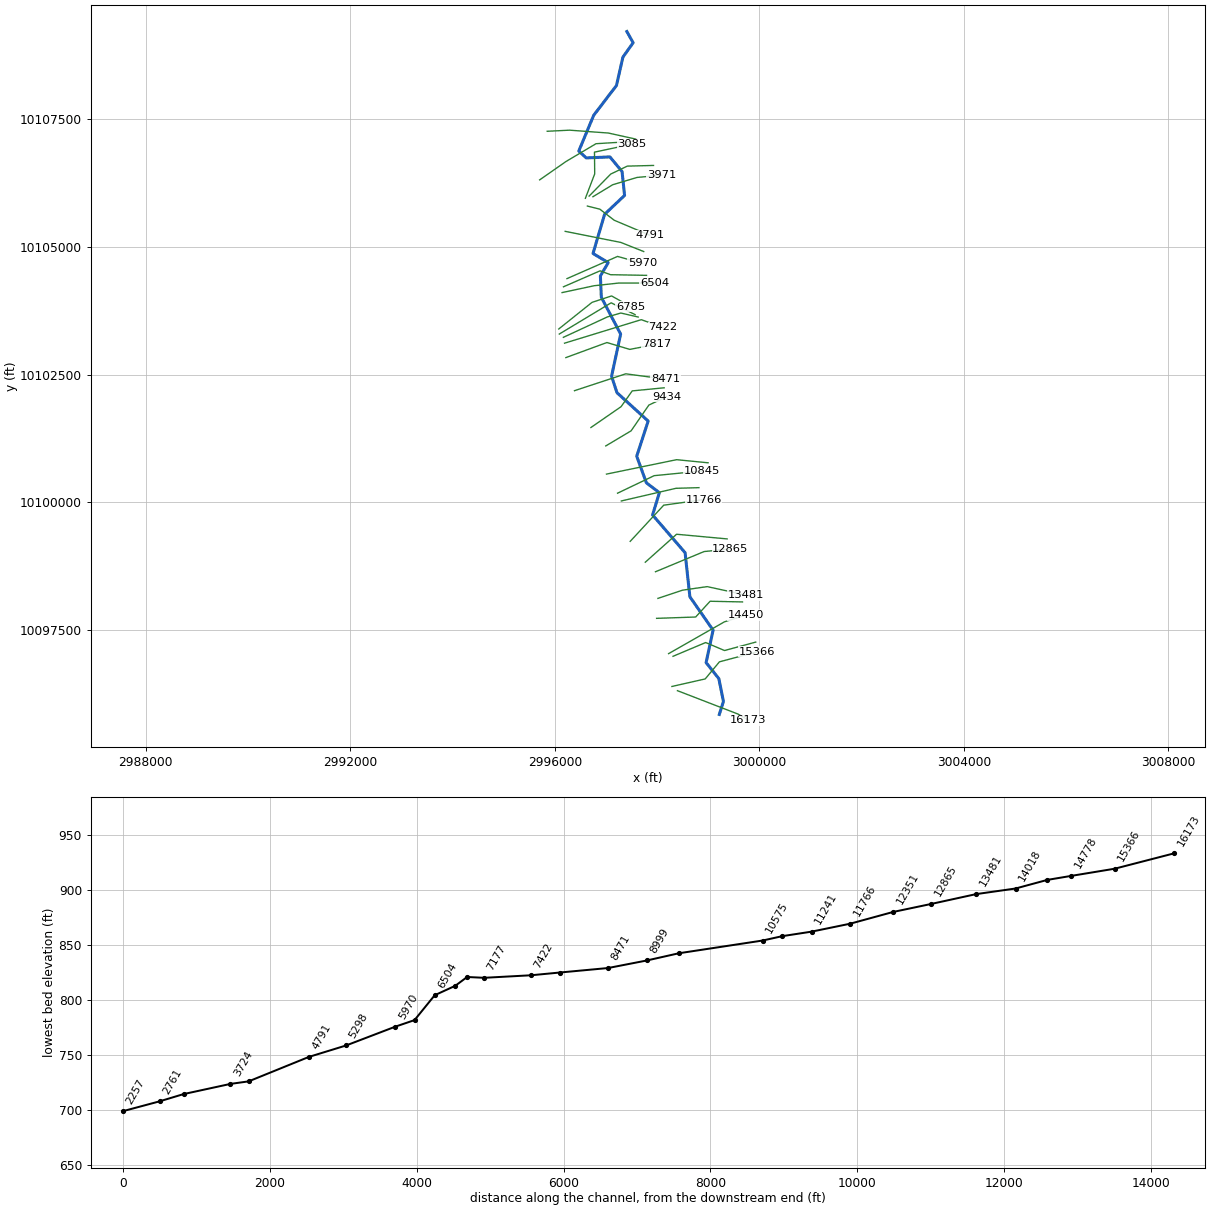
--- PEDERNALES TRIB 3.prj (project) ---

Proj Title=PEDERNALES TRIB 3 Base Level Engineering
Current Plan=p01
Default Exp/Contr=0.3,0.1
English Units
Geom File=g01
Flow File=f01
Plan File=p01
Y Axis Title=Elevation
X Axis Title(PF)=Main Channel Distance
X Axis Title(XS)=Station
BEGIN DESCRIPTION:
PEDERNALES TRIB 3
END DESCRIPTION:
DSS Export Rating Curves= 0
DSS Export Rating Curve Sorted= 0
DSS Export Volume Flow Curves= 0
DXF OffsetX= 0
DXF OffsetY= 0
DXF ScaleX= 1
DXF ScaleY= 10

--- PEDERNALES TRIB 3.p01 (plan) ---

Plan Title=Multiple Run
Short Identifier=Multiple
Geom File=g01
Flow File=f01
Subcritical Flow
K Sum by GR= 0
Std Step Tol= 0.01
Critical Tol= 0.01
Num of Std Step Trials= 20
Max Error Tol= 0.3
Flow Tol Ratio= 0.001
Split Flow NTrial= 30
Split Flow Tol= 0.02
Split Flow Ratio= 0.02
Log Output Level= 0
Friction Slope Method= 1
Unsteady Friction Slope Method= 2
Unsteady Bridges Friction Slope Method= 1
Parabolic Critical Depth
Global Vel Dist=  1 , 1 , 1
Global Log Level= 0
CheckData=True
Encroach Param= -1, 0, 0, 0
BEGIN DESCRIPTION:
Multiple Run
END DESCRIPTION:

--- PEDERNALES TRIB 3.f01 (steady flow) ---

Flow Title=Multiple
Number of Profiles=7
Profile Names=10-year,25-year,50-year,1pct_min,100-year,1pct_plu,500-year
River Rch & RM= PEDERNALES TRIB ,Reach-1,16173
     883    1279    1622    1507    2038    2756    3226
River Rch & RM= PEDERNALES TRIB ,Reach-1,15366
    1299    1914    2455    2302    3114    4211    5028
River Rch & RM= PEDERNALES TRIB ,Reach-1,6504
    1787    2679    3477    3296    4457    6028    7356
Boundary for River Rch & Prof#=PEDERNALES TRIB ,Reach-1,1
Up Type=0
Dn Type=3
Dn Slope=0.005
Boundary for River Rch & Prof#=PEDERNALES TRIB ,Reach-1,2
Up Type=0
Dn Type=3
Dn Slope=0.005
Boundary for River Rch & Prof#=PEDERNALES TRIB ,Reach-1,3
Up Type=0
Dn Type=3
Dn Slope=0.005
Boundary for River Rch & Prof#=PEDERNALES TRIB ,Reach-1,4
Up Type=0
Dn Type=3
Dn Slope=0.005
Boundary for River Rch & Prof#=PEDERNALES TRIB ,Reach-1,5
Up Type=0
Dn Type=3
Dn Slope=0.005
Boundary for River Rch & Prof#=PEDERNALES TRIB ,Reach-1,6
Up Type=0
Dn Type=3
Dn Slope=0.005
Boundary for River Rch & Prof#=PEDERNALES TRIB ,Reach-1,7
Up Type=0
Dn Type=3
Dn Slope=0.005

--- PEDERNALES TRIB 3.g01 (geometry) ---

Geom Title=Existing Conditions
Program Version=4.10

River Reach=PEDERNALES TRIB ,Reach-1
Reach XY= 30
      2999217.65     10095853.82      2999298.16     10096108.84
      2999208.47     10096553.73      2998959.12     10096868.53
      2999095.83      10097502.6      2998641.93     10098155.46
      2998548.05     10099018.56      2997912.14     10099755.92
      2998045.62     10100192.53      2997790.85     10100384.56
      2997602.04     10100904.35      2997825.76     10101592.64
      2997216.28     10102147.11      2997110.06     10102469.52
      2997287.55     10103293.31      2996909.68     10104014.25
      2996891.72     10104429.98      2997044.83     10104692.11
      2996747.27     10104870.42      2996973.71     10105636.27
      2997364.55     10106005.34      2997315.39     10106472.45
      2997078.01     10106759.24      2996614.29     10106739.22
      2996469.05     10106874.19       2996760.4     10107572.75
      2997205.94      10108155.9      2997332.06     10108710.93
      2997531.78     10108992.39      2997409.11     10109211.97

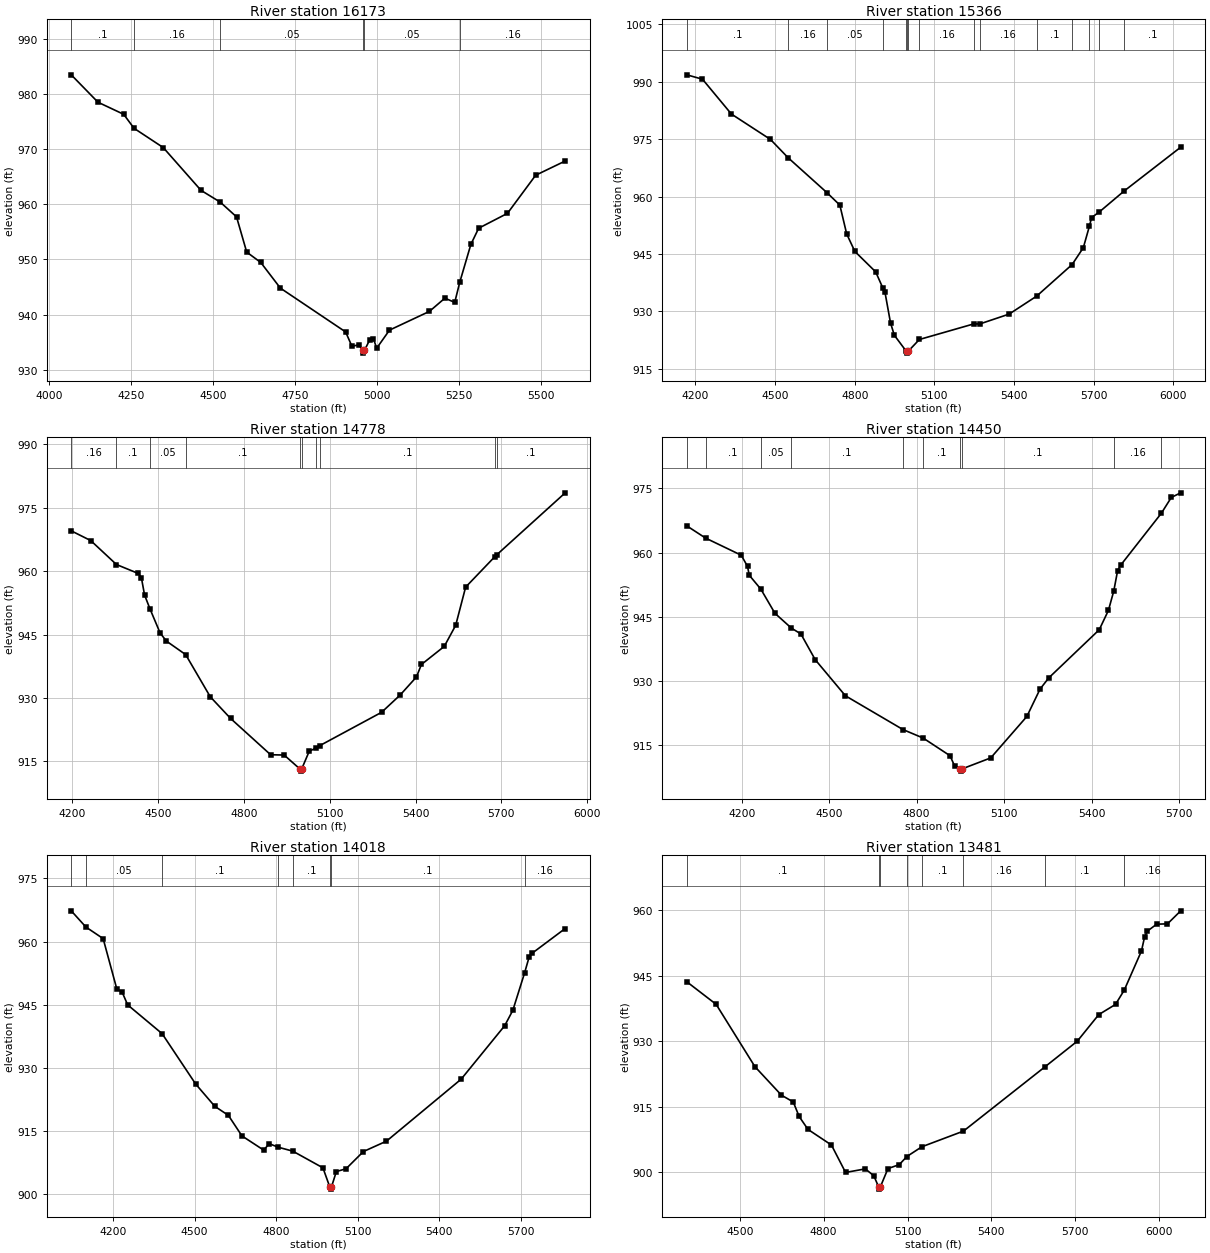
Type RM Length L Ch R = 1 ,16173   ,807,807,807
BEGIN DESCRIPTION:
PEDERNALES TRIB 3 36.0
END DESCRIPTION:
XS GIS Cut Line= 3
      2998399.18      10096318.8      2999579.77     10095863.05
      2999788.12     10095741.52
#Sta/Elev= 30
  4067.1  983.48  4148.7  978.51  4227.1  976.32  4258.7  973.78  4347.7  970.29
  4462.9  962.53  4521.7  960.39  4571.3  957.72  4602.3  951.33  4645.1  949.46
    4705   944.8  4904.1  936.85  4923.3  934.24  4945.3  934.54  4955.6  933.51
  4958.4  933.01  4961.6  933.51  4977.5  935.42  4988.6  935.64  4998.9  933.91
  5037.8  937.18  5159.7  940.58  5206.8  942.98  5236.8  942.21    5252  945.83
    5286  952.72  5309.8  955.66  5397.7  958.36  5483.7  965.27  5573.8  967.85
#Mann= 6 ,-1 , 0
  4067.1      .1       0  4258.7     .16       0  4521.7     .05       0
  4955.6    .035       0  4961.6     .05       0    5252     .16       0
Bank Sta=4955.6,4961.6
XS Rating Curve= 0 ,0
Exp/Cntr=0.3,0.1

Type RM Length L Ch R = 1 ,15366   ,588,588,588
BEGIN DESCRIPTION:
PEDERNALES TRIB 3 35.0
END DESCRIPTION:
XS GIS Cut Line= 4
      2998290.75     10096401.26      2998941.75     10096548.82
      2999219.53     10096883.02      2999952.99     10097078.32
#Sta/Elev= 30
  4167.1  991.79  4226.3  990.65  4335.3  981.55  4482.6  974.91  4549.1  970.13
  4695.3  961.02  4743.9  957.77  4769.7  950.23  4800.5  945.67  4878.9  940.33
  4905.5  936.18    4914  934.98  4934.8  927.01  4949.2  923.78  4992.8  919.73
  4995.6  919.61  4998.4  919.11  5001.6  919.61  5043.5  922.67  5247.9  926.73
    5272  926.75  5381.9  929.31  5485.7  934.01    5619  942.24  5661.3  946.65
  5684.3  952.29  5692.4  954.52  5721.7  955.99  5814.7  961.43  6028.2  972.89
#Mann= 15 ,-1 , 0
  4167.1      .1       0  4549.1     .16       0  4695.3     .05       0
  4905.5      .1       0  4992.8     .05       0  4995.6    .035       0
  5001.6     .05       0  5043.5     .16       0  5247.9      .1       0
    5272     .16       0  5485.7      .1       0    5619     .16       0
  5684.3      .1       0  5721.7     .16       0  5814.7      .1       0
Bank Sta=4995.6,5001.6
XS Rating Curve= 0 ,0
Exp/Cntr=0.3,0.1

Type RM Length L Ch R = 1 ,14778   ,328,328,328
BEGIN DESCRIPTION:
PEDERNALES TRIB 3 34.0
END DESCRIPTION:
XS GIS Cut Line= 4
      2998312.38     10096991.51      2998950.43     10097260.62
      2999319.36     10097104.37      2999930.23     10097269.01
#Sta/Elev= 30
  4197.2  969.55  4265.4  967.24  4355.2  961.57  4431.7  959.45  4442.3  958.44
  4453.4  954.35  4471.8  951.15  4507.7  945.36  4529.7  943.44    4597  940.24
  4682.9  930.26    4754  925.12  4893.8  916.53  4941.1  916.46  4996.3  913.15
  4999.1  912.65  5002.3  913.15  5028.7  917.36  5050.7  918.06  5066.2  918.71
  5281.5  926.58  5345.9  930.64  5403.3  934.95  5420.6   937.9  5500.5  942.19
  5540.4  947.18  5575.1  956.22  5676.5  963.39  5683.4  963.85    5923  978.55
#Mann= 10 ,-1 , 0
  4197.2     .16       0  4355.2      .1       0  4471.8     .05       0
    4597      .1       0  4996.3     .07       0  5002.3      .1       0
  5050.7     .16       0  5066.2      .1       0  5676.5     .16       0
  5683.4      .1       0
Bank Sta=4996.3,5002.3
XS Rating Curve= 0 ,0
Exp/Cntr=0.3,0.1

Type RM Length L Ch R = 1 ,14450   ,432,432,432
BEGIN DESCRIPTION:
PEDERNALES TRIB 3 32.0
END DESCRIPTION:
XS GIS Cut Line= 3
       2998225.6     10097043.61      2999315.02     10097664.27
       2999734.6     10097798.36
#Sta/Elev= 30
  4011.6  966.27  4076.2  963.41  4198.5  959.41  4220.1  956.79  4225.9  954.74
  4265.8  951.48  4314.1  945.84  4370.6  942.38  4403.1  941.02  4452.2  935.01
  4555.8  926.58  4753.2  918.69  4822.3  916.71  4914.6  912.58  4930.4  910.18
    4949  909.48  4951.8  908.98    4955  909.48  5054.3  912.07  5178.2  921.75
  5223.3  928.13  5253.2  930.75  5426.5  942.01    5458  946.54  5476.2  951.03
  5489.5  955.81    5500  957.09  5639.5  969.21  5673.7  972.91  5705.9  973.98
#Mann= 10 ,-1 , 0
  4011.6     .16       0  4076.2      .1       0  4265.8     .05       0
  4370.6      .1       0  4753.2     .16       0  4822.3      .1       0
    4949     .07       0    4955      .1       0  5476.2     .16       0
  5639.5      .1       0
Bank Sta=4949,4955
XS Rating Curve= 0 ,0
Exp/Cntr=0.3,0.1

Type RM Length L Ch R = 1 ,14018   ,537,537,537
BEGIN DESCRIPTION:
PEDERNALES TRIB 3 31.0
END DESCRIPTION:
XS GIS Cut Line= 4
      2997991.19     10097733.71      2998755.12     10097759.76
      2999037.24     10098067.92      2999670.93      10098054.9
#Sta/Elev= 30
  4046.6  967.29  4100.5  963.44  4163.9  960.69    4214  948.75    4234  947.94
    4254  944.95  4380.7  938.11  4504.1  926.14  4574.2  920.86  4624.2  918.71
  4674.2  913.82  4754.3  910.44  4774.3  911.98  4807.9  911.13  4861.2   910.2
  4971.9  906.24  4997.2  901.68    5000  901.18  5003.2  901.68  5021.2  905.35
    5057  906.02  5120.5   910.1  5205.6  912.58  5480.1   927.3  5640.1     940
  5670.1  943.66  5713.1  952.51  5730.1  956.34  5740.1  957.17  5862.6  963.09
#Mann= 8 ,-1 , 0
  4046.6     .16       0  4100.5     .05       0  4380.7      .1       0
  4807.9     .16       0  4861.2      .1       0  4997.2     .07       0
  5003.2      .1       0  5713.1     .16       0
Bank Sta=4997.2,5003.2
XS Rating Curve= 0 ,0
Exp/Cntr=0.3,0.1

Type RM Length L Ch R = 1 ,13481   ,616,616,616
BEGIN DESCRIPTION:
PEDERNALES TRIB 3 30.0
END DESCRIPTION:
XS GIS Cut Line= 4
      2998017.23     10098124.33      2998499.04     10098284.93
      2998980.82     10098354.37      2999734.72     10098189.73
#Sta/Elev= 30
  4310.6   943.6  4415.7  938.42  4554.3  924.15  4649.2  917.61  4691.4  916.06
  4712.5  912.73  4744.1  909.77    4828  906.19  4878.5  899.91  4949.2  900.73
  4979.5  899.14  4996.8  896.59  4999.5  896.09  5002.8  896.59  5030.1   900.8
  5070.5   901.7  5097.5  903.55  5151.2  905.79    5300  909.38  5590.6  924.06
  5706.9  929.97  5783.9  936.07  5843.7   938.4  5875.1  941.69  5936.6  950.66
  5947.7  953.86  5957.9   955.2  5990.8  956.78  6029.6  956.86  6076.9  959.84
#Mann= 8 ,-1 , 0
  4310.6      .1       0  4996.8     .07       0  5002.8      .1       0
  5097.5     .16       0  5151.2      .1       0    5300     .16       0
  5590.6      .1       0  5875.1     .16       0
Bank Sta=4996.8,5002.8
XS Rating Curve= 0 ,0
Exp/Cntr=0.3,0.1

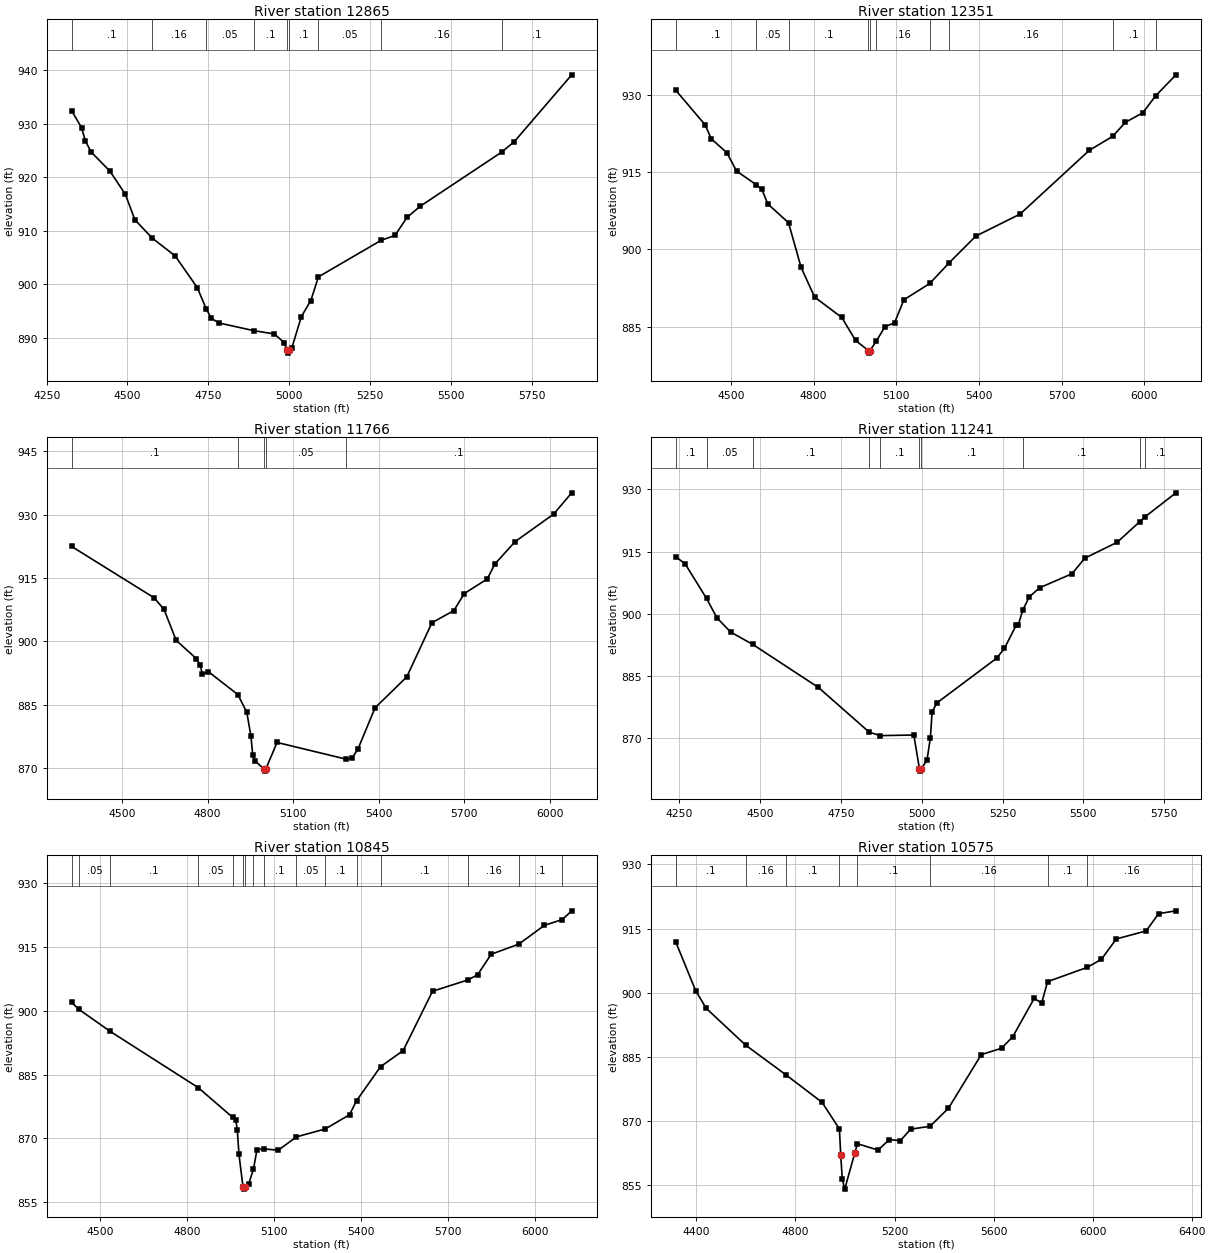
Type RM Length L Ch R = 1 ,12865   ,514,514,514
BEGIN DESCRIPTION:
PEDERNALES TRIB 3 29.0
END DESCRIPTION:
XS GIS Cut Line= 3
      2997969.57     10098645.19      2998920.05     10099040.14
      2999434.97     10099092.06
#Sta/Elev= 30
  4327.3  932.45  4357.9  929.29  4369.4  926.86  4387.2  924.76  4445.7  921.15
  4493.4  916.83  4522.7  912.07  4576.7  908.62  4647.4   905.3  4715.9  899.36
  4743.1  895.45  4759.3  893.62  4782.9  892.75  4891.8   891.3  4954.2   890.7
  4984.7  889.07  4994.5  887.61  4997.2  887.11  5000.5  887.61  5008.3  888.08
  5037.8  893.94  5067.1  896.95  5090.6  901.38    5285  908.23  5327.3  909.13
    5365  912.52  5405.2  914.58  5657.2  924.71  5696.7  926.69  5874.1  939.18
#Mann= 9 ,-1 , 0
  4327.3      .1       0  4576.7     .16       0  4743.1     .05       0
  4891.8      .1       0  4994.5     .07       0  5000.5      .1       0
  5090.6     .05       0    5285     .16       0  5657.2      .1       0
Bank Sta=4994.5,5000.5
XS Rating Curve= 0 ,0
Exp/Cntr=0.3,0.1

Type RM Length L Ch R = 1 ,12351   ,585,585,585
BEGIN DESCRIPTION:
PEDERNALES TRIB 3 28.0
END DESCRIPTION:
XS GIS Cut Line= 3
       2997769.9     10098831.82      2998381.86     10099378.68
      2999371.47     10099287.53
#Sta/Elev= 30
  4300.7  930.83  4406.9  924.14  4428.7  921.46  4485.5  918.76  4520.6  915.21
  4591.8  912.56  4612.6  911.65  4634.1  908.82  4709.4  905.17  4754.7  896.57
    4804  890.76  4902.7  886.81  4952.8  882.35  4999.1   880.4  5001.9   879.9
  5005.1   880.4  5028.2  882.24    5059  885.02  5094.1  885.78    5128  890.24
  5221.8   893.4  5292.2  897.41  5389.1  902.59  5549.8  906.86  5800.9  919.22
  5885.6  921.92  5931.4  924.63  5994.9  926.49  6041.2  929.76  6115.2  933.85
#Mann= 10 ,-1 , 0
  4300.7      .1       0  4591.8     .05       0  4709.4      .1       0
  4999.1     .07       0  5005.1      .1       0  5028.2     .16       0
  5221.8     .05       0  5292.2     .16       0  5885.6      .1       0
  6041.2     .16       0
Bank Sta=4999.1,5005.1
XS Rating Curve= 0 ,0
Exp/Cntr=0.3,0.1

Type RM Length L Ch R = 1 ,11766   ,525,525,525
BEGIN DESCRIPTION:
PEDERNALES TRIB 3 26.0
END DESCRIPTION:
XS GIS Cut Line= 3
      2997474.75      10099239.8      2998130.12     10099947.26
      2998911.36     10100055.76
#Sta/Elev= 30
  4323.7  922.46  4612.3  910.33  4647.5  907.56    4690  900.23  4760.9  895.89
    4775  894.28  4781.8   892.2  4803.4  892.79  4906.3  887.38  4937.7  883.19
  4951.9  877.65  4958.7  873.05  4966.1  871.67  4998.3  869.75    5001  869.25
  5004.3  869.75  5043.8  876.04    5285   872.1  5306.6  872.33  5326.8   874.4
  5387.4  884.25  5498.4  891.56  5586.9  904.41  5663.6  907.27  5700.3  911.32
  5781.1  914.78    5807  918.29  5878.7  923.63  6013.3  930.12  6076.8  935.17
#Mann= 5 ,-1 , 0
  4323.7      .1       0  4906.3     .05       0  4998.3    .035       0
  5004.3     .05       0    5285      .1       0
Bank Sta=4998.3,5004.3
XS Rating Curve= 0 ,0
Exp/Cntr=0.3,0.1

Type RM Length L Ch R = 1 ,11241   ,396,396,396
BEGIN DESCRIPTION:
PEDERNALES TRIB 3 25.0
END DESCRIPTION:
XS GIS Cut Line= 3
      2997301.12     10100029.72      2998368.84     10100277.12
      2998820.25     10100290.14
#Sta/Elev= 30
  4238.9  913.67    4267   912.1  4333.8  903.68    4366     899  4408.6  895.57
  4476.4  892.62  4680.1  882.22  4836.9  871.46    4871  870.61  4975.2  870.76
  4992.8  862.55  4995.5  862.05  4998.8  862.55  5016.3  864.83  5026.6  870.15
  5031.8  876.37  5047.1  878.53  5231.9   889.3  5255.5  891.63    5293  897.37
  5298.2  897.28  5312.6  900.87  5332.1  904.02  5364.5  906.26  5464.6  909.64
  5504.6  913.41  5604.6  917.23  5674.7  922.22  5691.4   923.4  5786.5  929.16
#Mann= 10 ,-1 , 0
  4238.9      .1       0  4333.8     .05       0  4476.4      .1       0
  4836.9     .05       0    4871      .1       0  4992.8     .07       0
  4998.8      .1       0  5312.6      .1       0  5674.7     .16       0
  5691.4      .1       0
Bank Sta=4992.8,4998.8
XS Rating Curve= 0 ,0
Exp/Cntr=0.3,0.1

Type RM Length L Ch R = 1 ,10845   ,270,270,270
BEGIN DESCRIPTION:
PEDERNALES TRIB 3 24.0
END DESCRIPTION:
XS GIS Cut Line= 3
      2997227.32     10100181.62      2997943.49     10100524.51
       2998872.3     10100615.66
#Sta/Elev= 30
  4401.1  901.99  4426.6  900.32  4533.9  895.17  4838.3  881.91  4957.4   874.9
  4967.8   874.4  4973.3   871.9  4978.9  866.24    4993   858.5  4995.8     858
    4999   858.5  5012.2  859.14    5029  862.69  5041.3  867.32  5064.2  867.48
  5114.9  867.17  5177.3  870.31  5277.5  872.18  5360.9  875.53    5385  878.81
    5468  886.85  5546.1  890.63  5647.6  904.61  5770.6   907.3    5803  908.49
  5850.5  913.34  5945.7  915.72  6034.1  920.14  6095.8   921.5  6128.4  923.56
#Mann= 16 ,-1 , 0
  4401.1      .1       0  4426.6     .05       0  4533.9      .1       0
  4838.3     .05       0  4957.4      .1       0    4993     .07       0
    4999      .1       0    5029     .05       0  5064.2      .1       0
  5177.3     .05       0  5277.5      .1       0    5385     .16       0
    5468      .1       0  5770.6     .16       0  5945.7      .1       0
  6095.8     .16       0
Bank Sta=4993,4999
XS Rating Curve= 0 ,0
Exp/Cntr=0.3,0.1

Type RM Length L Ch R = 1 ,10575   ,1141,1141,1141
BEGIN DESCRIPTION:
PEDERNALES TRIB 3 23.0
END DESCRIPTION:
XS GIS Cut Line= 3
      2997010.36      10100554.9      2998381.86     10100837.01
      2998998.16     10100776.25
#Sta/Elev= 30
  4317.1  911.77  4396.8  900.48  4439.1  896.35  4598.5  887.72  4761.1  880.77
  4907.3  874.33  4977.5  868.08  4982.6  862.09    4989  856.39  4998.9     854
    5040  862.55  5050.2  864.63  5133.6  863.14  5178.9   865.6  5223.8  865.33
  5264.6  868.03  5343.5  868.71  5417.8  872.93  5550.5  885.49  5632.2  886.98
  5677.2  889.65  5764.1  898.65  5794.3  897.55    5818  902.57  5977.7   905.9
  6035.5  907.79  6095.7  912.57  6216.3  914.44  6266.6  918.49  6336.6  919.15
#Mann= 8 ,-1 , 0
  4317.1      .1       0  4598.5     .16       0  4761.1      .1       0
  4977.5     .07       0  5050.2      .1       0  5343.5     .16       0
    5818      .1       0  5977.7     .16       0
Bank Sta=4982.6,5040
XS Rating Curve= 0 ,0
Exp/Cntr=0.3,0.1

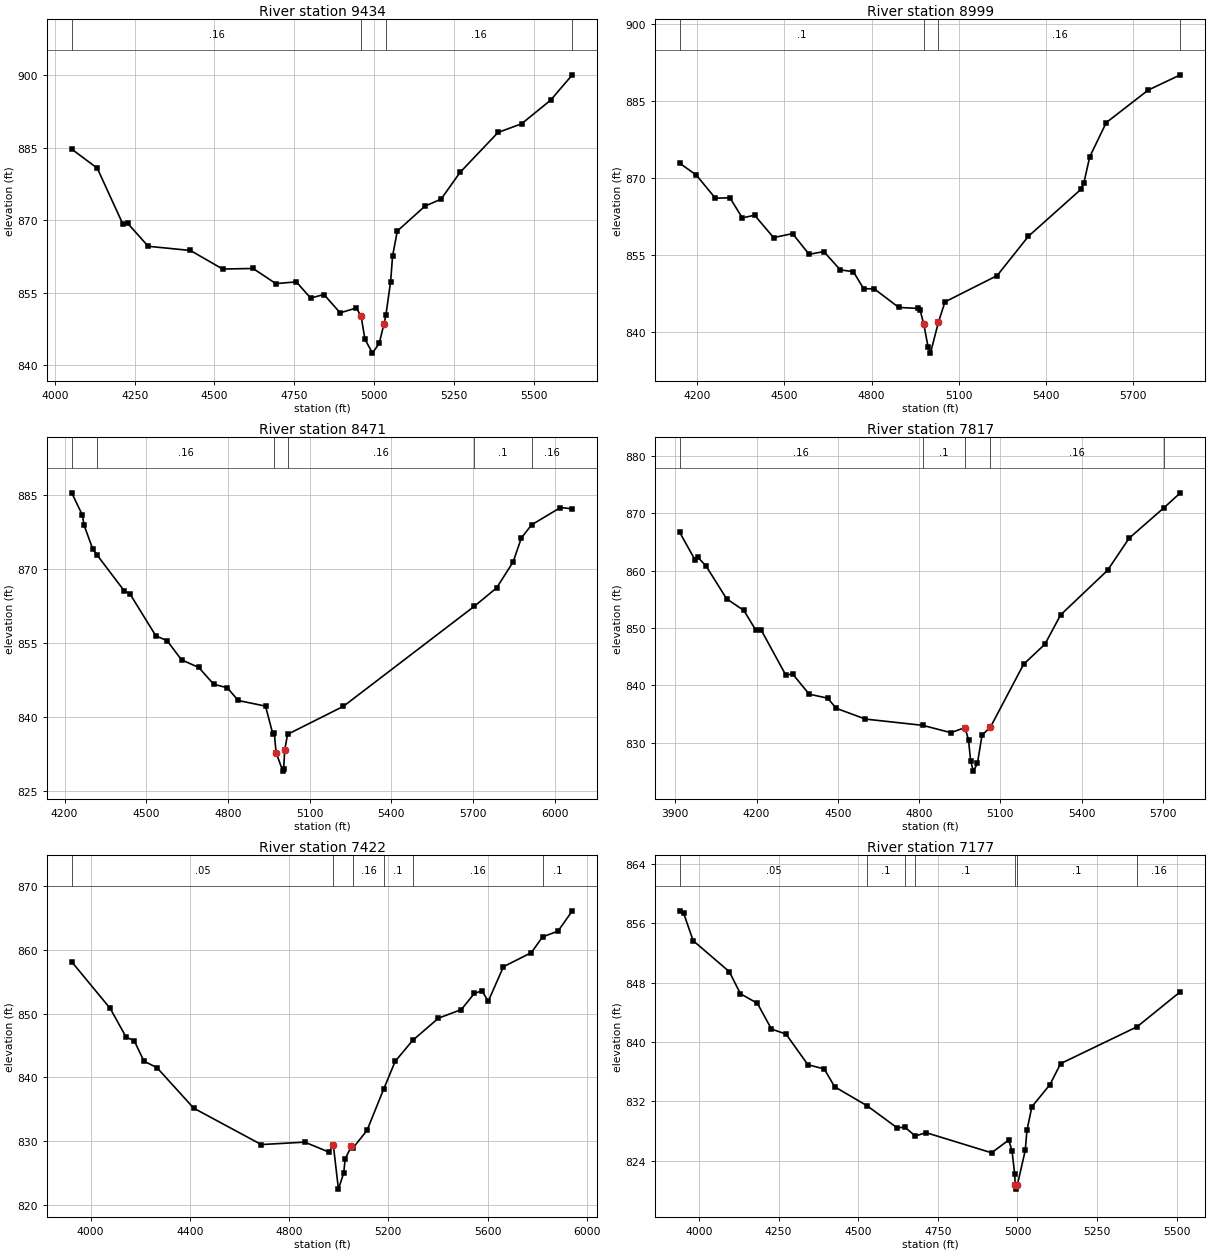
Type RM Length L Ch R = 1 ,9434    ,435,435,435
BEGIN DESCRIPTION:
PEDERNALES TRIB 3 21.0
END DESCRIPTION:
XS GIS Cut Line= 4
      2996997.35     10101106.13       2997492.1     10101401.25
      2997839.32     10101904.72      2998184.03     10102068.46
#Sta/Elev= 30
  4052.4  884.73  4132.5  880.78  4212.3  869.25  4227.8  869.35  4292.1  864.59
  4424.4  863.72  4525.6  859.87    4621  859.99  4692.2  856.85  4756.6  857.21
  4801.3  853.85  4843.2  854.59  4893.9  850.79  4944.6   851.8  4959.5   850.1
  4971.6  845.32  4995.1  842.44  5016.3  844.45  5031.2  848.48  5037.2  850.28
  5052.1  857.27  5058.2  862.55  5073.1  867.75  5159.6   872.9  5210.3  874.37
  5269.8  879.91  5388.9  888.19  5462.6  889.98  5553.5  894.87  5621.7  900.13
#Mann= 4 ,-1 , 0
  4052.4     .16       0  4959.5      .1       0  5037.2     .16       0
  5621.7     .16       0
Bank Sta=4959.5,5031.2
XS Rating Curve= 0 ,0
Exp/Cntr=0.3,0.1

Type RM Length L Ch R = 1 ,8999    ,528,528,528
BEGIN DESCRIPTION:
PEDERNALES TRIB 3 20.0
END DESCRIPTION:
XS GIS Cut Line= 4
       2996706.5     10101466.34      2997296.79     10101874.34
       2997513.8      10102182.5      2998138.78     10102243.26
#Sta/Elev= 30
  4139.8  872.92  4196.8  870.62  4262.4   866.1  4312.4   866.2    4355  862.27
  4397.5  862.79  4462.5  858.43    4528  859.21  4584.8  855.17  4635.5  855.71
  4692.3  852.13  4736.9   851.8  4772.7  848.45  4808.5  848.46  4893.3  844.82
  4958.2  844.63  4966.7  844.28  4979.1  841.63  4993.9   837.2  5002.3  835.91
  5029.6   841.9  5052.3   845.9  5231.7  851.02  5339.4  858.69  5520.3  867.85
  5530.3  869.13  5550.4  874.19  5607.2  880.85  5751.4  887.18  5862.2  890.16
#Mann= 4 ,-1 , 0
  4139.8      .1       0  4979.1     .09       0  5029.6     .16       0
  5862.2     .16       0
Bank Sta=4979.1,5029.6
XS Rating Curve= 0 ,0
Exp/Cntr=0.3,0.1

Type RM Length L Ch R = 1 ,8471    ,654,654,654
BEGIN DESCRIPTION:
PEDERNALES TRIB 3 19.0
END DESCRIPTION:
XS GIS Cut Line= 3
      2996385.35     10102186.85      2997387.93      10102516.7
      2998164.14     10102412.63
#Sta/Elev= 30
    4226   885.5  4265.1     881  4271.4  878.94    4303  874.15  4319.3  872.88
  4418.8  865.63  4439.8  865.02  4534.6  856.53  4576.7  855.49  4629.3  851.63
  4692.5  850.09  4747.2  846.69  4797.8  845.96  4837.3  843.39  4937.9  842.24
  4964.5   836.6  4969.7  836.89  4976.7  832.81  5001.3  829.06  5004.5  829.56
  5008.3  833.35  5018.8  836.52    5224  842.21  5704.2  862.47  5786.5  866.22
    5847  871.47  5877.3  876.34    5915  879.01  6021.1  882.52  6064.6  882.25
#Mann= 6 ,-1 , 0
    4226      .1       0  4319.3     .16       0  4969.7     .07       0
  5018.8     .16       0  5704.2      .1       0    5915     .16       0
Bank Sta=4976.7,5008.3
XS Rating Curve= 0 ,0
Exp/Cntr=0.3,0.1

Type RM Length L Ch R = 1 ,7817    ,395,395,395
BEGIN DESCRIPTION:
PEDERNALES TRIB 3 17.0
END DESCRIPTION:
XS GIS Cut Line= 4
      2996216.07     10102833.55      2997019.01     10103128.68
      2997466.06     10102994.13      2997982.58     10103093.96
#Sta/Elev= 30
  3916.5  866.69  3972.3  861.95    3983  862.37    4014   860.8  4089.5   855.1
  4153.4  853.06  4196.9  849.65  4216.7  849.69  4308.1  841.77  4333.3  841.98
  4394.2  838.44  4462.4  837.75  4494.4  835.97  4602.2  834.09  4813.2     833
  4917.6  831.72  4969.8   832.6  4982.7  830.44  4990.7  826.69  5000.9     825
  5015.7  826.38  5032.5  831.28  5063.8   832.7    5186  843.66  5264.9  847.18
  5322.8  852.29  5495.9  860.07  5575.8  865.69  5704.2     871  5764.9  873.61
#Mann= 5 ,-1 , 0
  3916.5     .16       0  4813.2      .1       0  4969.8     .07       0
  5063.8     .16       0  5704.2      .1       0
Bank Sta=4969.8,5063.8
XS Rating Curve= 0 ,0
Exp/Cntr=0.3,0.1

Type RM Length L Ch R = 1 ,7422    ,637,637,637
BEGIN DESCRIPTION:
PEDERNALES TRIB 3 16.0
END DESCRIPTION:
XS GIS Cut Line= 3
      2996190.05     10103115.67      2997691.75     10103575.73
      2998112.79     10103423.81
#Sta/Elev= 30
  3923.7  858.15  4078.9  850.83  4142.9  846.34  4175.7  845.77  4214.9  842.56
  4267.2  841.55  4415.5  835.19    4688  829.48  4863.3  829.86  4960.5   828.3
  4978.4  829.39    4999  822.49  5020.2  825.02    5026  827.21  5051.6  829.28
  5058.8     829  5114.3  831.71  5181.3  838.17  5227.8  842.54  5298.3  845.82
    5402   849.3  5494.3  850.65  5546.8  853.18  5577.5   853.6  5602.9  851.95
  5664.2  857.38  5776.3  859.57  5822.1  862.06  5884.1  862.95  5941.9  866.14
#Mann= 6 ,-1 , 0
  3923.7     .05       0  4978.4      .1       0  5058.8     .16       0
  5181.3      .1       0  5298.3     .16       0  5822.1      .1       0
Bank Sta=4978.4,5051.6
XS Rating Curve= 0 ,0
Exp/Cntr=0.3,0.1

Type RM Length L Ch R = 1 ,7177    ,232,232,232
BEGIN DESCRIPTION:
Mapping XS aa108f09
END DESCRIPTION:
XS GIS Cut Line= 4
      2996167.41     10103230.05      2997028.56     10103629.37
      2997290.71     10103705.76      2997630.97     10103627.64
#Sta/Elev= 30
    3940  857.67  3952.2  857.35  3982.1  853.65  4095.5  849.48  4130.6   846.5
  4183.7  845.22  4227.8  841.75  4273.5  841.08  4342.2  836.95  4393.6  836.38
  4426.2  833.98  4528.2  831.42  4622.7  828.44  4645.9  828.56  4679.7  827.35
  4712.8  827.81  4918.9  825.09  4972.5  826.81  4982.9  825.38  4991.1  822.29
  4993.3   820.7  4996.1   820.2  4999.3   820.7  5024.5  825.42  5029.8  828.13
  5045.4   831.3    5102  834.27  5135.5   837.1  5375.5  842.06  5511.4  846.78
#Mann= 7 ,-1 , 0
    3940     .05       0  4528.2      .1       0  4645.9     .05       0
  4679.7      .1       0  4993.3     .07       0  4999.3      .1       0
  5375.5     .16       0
Bank Sta=4993.3,4999.3
XS Rating Curve= 0 ,0
Exp/Cntr=0.3,0.1

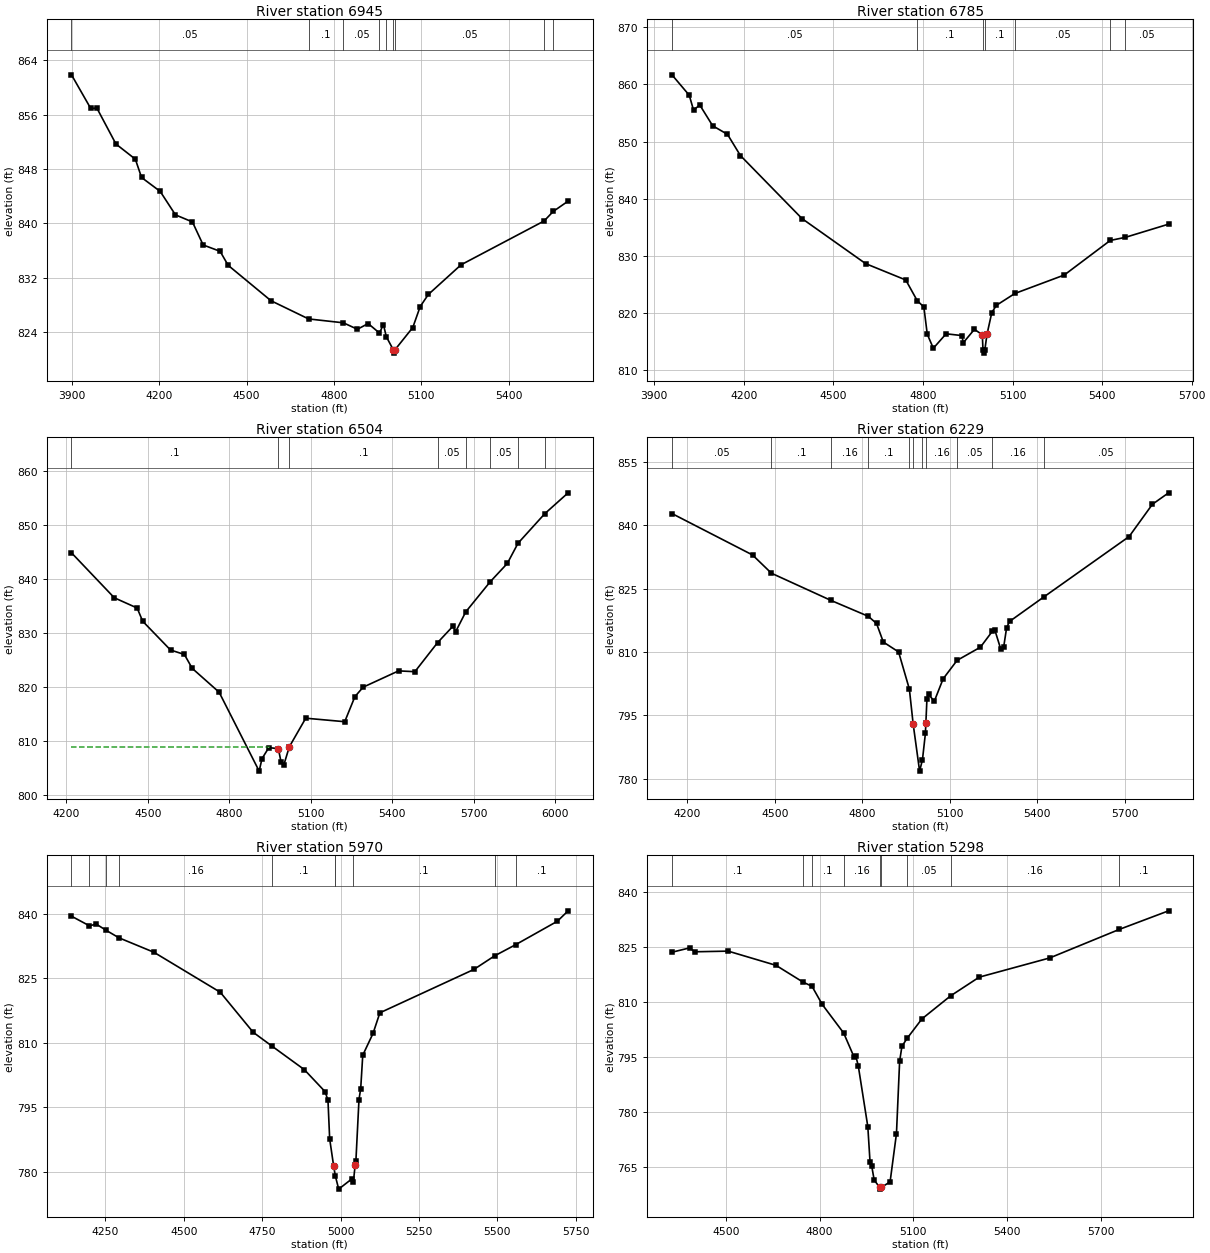
Type RM Length L Ch R = 1 ,6945    ,160,160,160
BEGIN DESCRIPTION:
Mapping XS b85fbb0b
END DESCRIPTION:
XS GIS Cut Line= 3
      2996087.56     10103294.29      2997101.47     10103905.41
      2997570.24      10103674.5
#Sta/Elev= 30
  3898.2  861.87  3964.2  856.93  3985.6  856.96    4051  851.69  4117.6  849.46
  4138.9  846.77    4203  844.72  4255.4  841.27  4313.7  840.23  4350.6  836.84
  4408.8  835.91  4436.4  833.85  4583.6  828.64  4712.9  825.96  4832.4  825.39
  4880.6  824.44  4917.5  825.28  4956.3  823.89  4969.9  825.13  4980.1  823.33
  5003.8  821.43  5006.6  820.93  5009.8  821.43  5070.9   824.7  5096.3  827.78
  5124.3  829.56  5236.6  833.92  5522.1  840.37  5553.6  841.78  5604.6  843.29
#Mann= 9 ,-1 , 0
  3898.2     .05       0  4712.9      .1       0  4832.4     .05       0
  4956.3      .1       0  4980.1     .05       0  5003.8    .035       0
  5009.8     .05       0  5522.1      .1       0  5553.6     .16       0
Bank Sta=5003.8,5009.8
XS Rating Curve= 0 ,0
Exp/Cntr=0.3,0.1

Type RM Length L Ch R = 1 ,6785    ,281,281,281
BEGIN DESCRIPTION:
PEDERNALES TRIB 3 15.0
END DESCRIPTION:
XS GIS Cut Line= 4
      2996077.15     10103393.42      2996728.21     10103914.27
      2997110.16     10104040.14      2997483.43      10103831.8
#Sta/Elev= 30
  3959.3  861.66  4017.2  858.09  4031.6  855.49  4052.4  856.39  4095.7  852.75
  4145.3  851.25  4188.5  847.55    4395  836.52  4607.9  828.65  4742.4  825.79
  4780.9  822.16    4803  821.07  4814.4  816.31  4834.7  813.85  4877.6  816.38
    4930  816.07  4935.3  814.83  4972.3  817.16  4998.8  816.21  5001.1   813.5
  5003.9     813  5007.1   813.5  5014.4  816.27  5030.6   820.1    5046  821.36
  5107.9  823.43  5273.4  826.66  5427.3   832.7  5478.3  833.25  5622.7  835.55
#Mann= 7 ,-1 , 0
  3959.3     .05       0  4780.9      .1       0  5001.1     .07       0
  5007.1      .1       0  5107.9     .05       0  5427.3      .1       0
  5478.3     .05       0
Bank Sta=4998.8,5014.4
XS Rating Curve= 0 ,0
Exp/Cntr=0.3,0.1

Type RM Length L Ch R = 1 ,6504    ,275,275,275
BEGIN DESCRIPTION:
PEDERNALES TRIB 3 14.0
END DESCRIPTION:
XS GIS Cut Line= 4
      2996142.31     10104105.25      2996771.61     10104239.79
      2997249.04     10104291.87      2997952.16     10104291.87
#Sta/Elev= 30
  4219.7  844.86  4377.1  836.53  4461.2  834.63  4481.6  832.18  4583.9  826.85
    4635  826.02  4663.7  823.45  4762.7  819.03  4910.1   804.4  4920.4  806.71
  4945.6  808.76  4980.8  808.56  4990.8  806.03  5000.9  805.57    5021  808.91
  5081.4  814.21  5224.8  813.56  5262.4  818.22  5292.6  819.96  5422.9  822.98
  5482.9  822.83  5566.1   828.2  5622.9  831.26  5632.9  830.25  5670.1  833.92
  5759.7  839.48  5822.9  842.89  5862.2  846.63  5960.9  852.12  6046.6  855.98
#Mann= 8 ,-1 , 0
  4219.7      .1       0  4980.8     .05       0    5021      .1       0
  5566.1     .05       0  5670.1      .1       0  5759.7     .05       0
  5862.2     .16       0  5960.9      .1       0
#XS Ineff= 2 , 0
         4947.44  808.94
Permanent Ineff=
       T       T
Bank Sta=4980.8,5021
XS Rating Curve= 0 ,0
Exp/Cntr=0.3,0.1

Type RM Length L Ch R = 1 ,6229    ,259,259,259
BEGIN DESCRIPTION:
Mapping XS 0988175e
END DESCRIPTION:
XS GIS Cut Line= 4
       2996169.4     10104218.57      2996885.53     10104531.06
      2997088.65     10104455.54      2997793.88     10104442.53
#Sta/Elev= 30
  4146.9  842.73  4423.2  832.94  4488.1  828.62  4692.7  822.18  4820.2  818.44
  4848.5  816.75  4871.9  812.35  4924.2  810.01  4961.2  801.22  4974.1  793.03
  4996.3  781.83  5006.1  784.53  5016.2  790.76  5017.8  793.24  5021.5  798.97
  5027.4  799.97  5046.6  798.33  5076.9  803.64  5124.7  808.01  5204.8  811.13
  5246.1  814.92  5254.8  815.09  5274.8  810.64  5284.8  811.25  5294.8  815.75
  5304.8  817.22  5422.6  823.02  5714.9  837.29  5794.9  844.93  5850.3  847.63
#Mann= 11 ,-1 , 0
  4146.9     .05       0  4488.1      .1       0  4692.7     .16       0
  4820.2      .1       0  4961.2     .05       0  4974.1     .05       0
  5006.1     .05       0  5017.8     .16       0  5124.7     .05       0
  5246.1     .16       0  5422.6     .05       0
Bank Sta=4974.1,5017.8
XS Rating Curve= 0 ,0
Exp/Cntr=0.3,0.1

Type RM Length L Ch R = 1 ,5970    ,672,672,672
BEGIN DESCRIPTION:
PEDERNALES TRIB 3 13.0
END DESCRIPTION:
XS GIS Cut Line= 3
      2996237.77     10104378.68      2997227.34     10104812.71
      2997712.43     10104678.44
#Sta/Elev= 30
  4141.6   839.4    4199  837.16  4220.3  837.57  4251.7  836.14  4292.8  834.38
  4404.4  831.02  4616.1  821.72  4721.1  812.41  4782.3  809.13    4884  803.74
  4950.4  798.61  4959.6   796.6    4965  787.62 4977.73  781.31    4983  779.03
  4993.8  775.95  5035.2   778.3  5040.6  777.62 5046.25  781.51  5048.7  782.56
  5058.5  796.77    5064  799.34  5070.5  807.08  5103.3  812.15  5125.1  816.94
  5425.1  827.03    5491  830.18  5559.2  832.82  5691.2  838.23  5725.5  840.65
#Mann= 10 ,-1 , 0
  4141.6     .05       0    4199      .1       0  4251.7     .05       0
  4292.8     .16       0  4782.3      .1       0    4983     .16       0
    4983     .05       0  5040.6      .1       0    5491     .05       0
  5559.2      .1       0
Bank Sta=4977.73,5046.25
XS Rating Curve= 0 ,0
Exp/Cntr=0.3,0.1

Type RM Length L Ch R = 1 ,5298    ,507,507,507
BEGIN DESCRIPTION:
PEDERNALES TRIB 3 12.0
END DESCRIPTION:
XS GIS Cut Line= 3
      2996203.05     10105303.16      2997292.45     10105086.15
      2997738.78     10104908.48
#Sta/Elev= 30
  4326.7  823.56  4383.2  824.74  4399.5  823.68  4506.8  823.86    4660  819.98
  4746.4  815.41  4775.4  814.25  4808.2  809.29  4876.9  801.48  4910.4  794.88
  4915.5   795.3  4923.6  792.54  4954.2  775.93  4961.4  766.14  4966.5  765.25
  4974.6  761.33    4992  759.34  4994.7  758.84    4998  759.34  5025.6  760.83
    5046  774.01  5056.2  793.86  5063.6  797.87  5079.9     800  5127.5  805.34
  5219.5  811.64  5311.1  816.75  5537.1     822  5759.5  829.78  5917.9  834.87
#Mann= 9 ,-1 , 0
  4326.7      .1       0  4746.4     .05       0  4775.4      .1       0
  4876.9     .16       0    4992     .07       0    4998     .16       0
  5079.9     .05       0  5219.5     .16       0  5759.5      .1       0
Bank Sta=4992,4998
XS Rating Curve= 0 ,0
Exp/Cntr=0.3,0.1

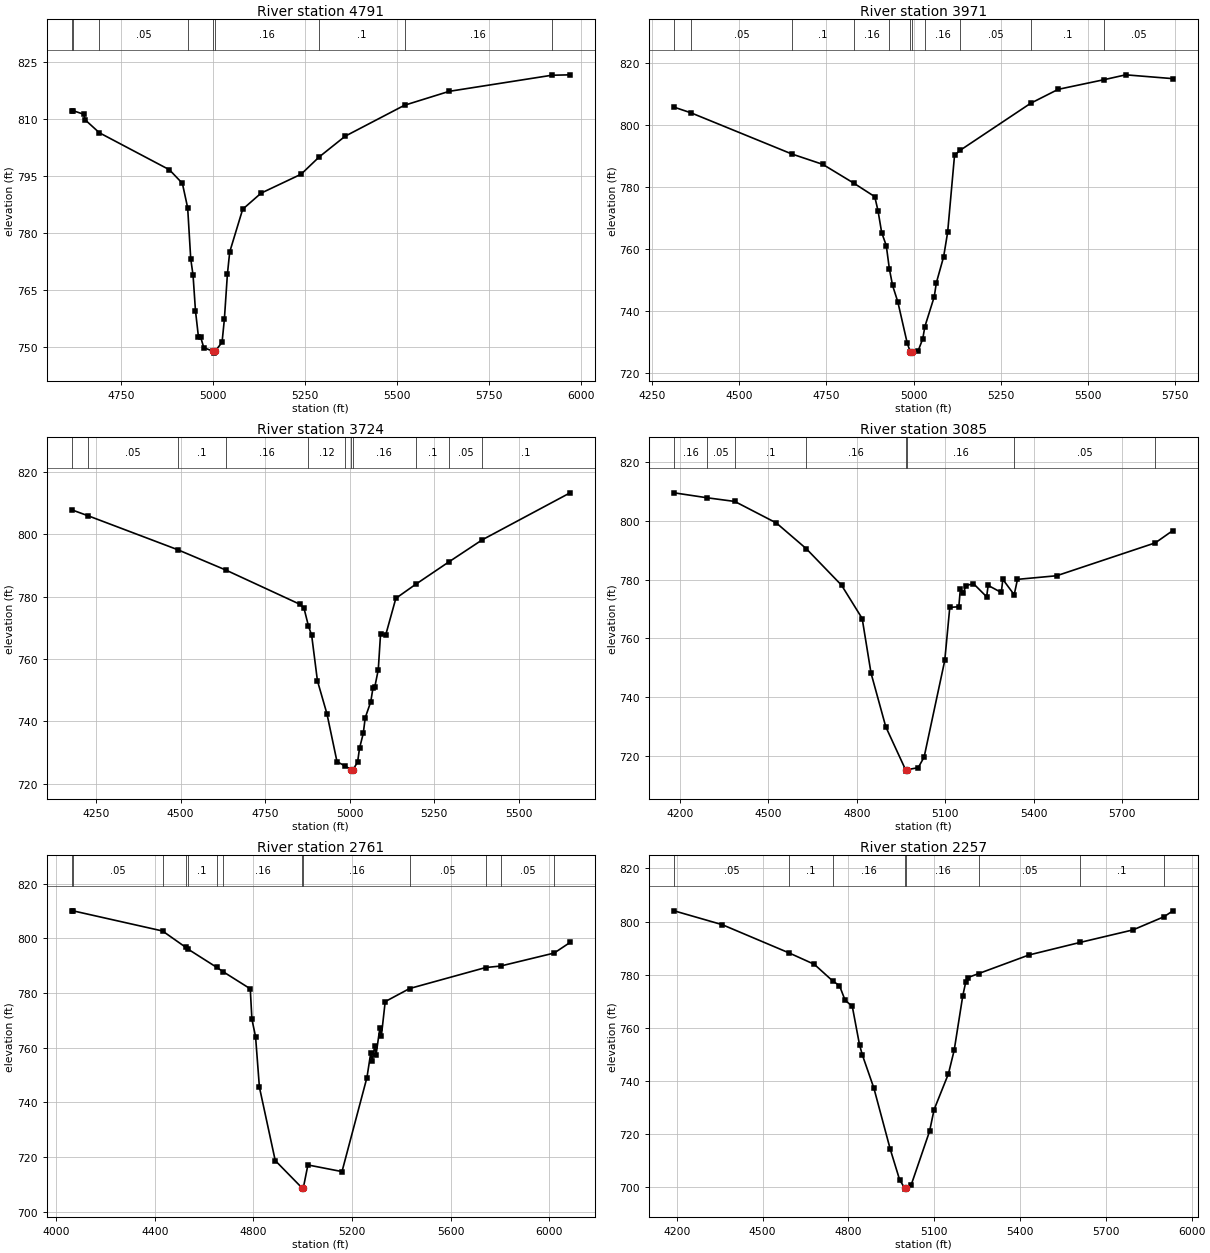
Type RM Length L Ch R = 1 ,4791    ,820,820,820
BEGIN DESCRIPTION:
PEDERNALES TRIB 3 10.0
END DESCRIPTION:
XS GIS Cut Line= 4
      2996637.04     10105797.96      2996880.12     10105737.19
      2997162.24     10105520.17      2997852.38     10105229.36
#Sta/Elev= 30
  4615.5  812.28  4620.5  812.28  4647.9  811.38  4653.3  809.81    4691  806.49
  4881.4  796.75  4916.7  793.17  4931.1  786.72  4939.4  773.32  4945.8   768.9
  4952.3  759.62  4960.3  752.81  4966.6  752.63  4974.8   749.9  4999.8  748.95
  5002.5  748.45  5005.8  748.95  5024.6   751.3  5030.9  757.37  5039.1  769.21
  5045.4  775.09  5080.7  786.35  5130.6  790.58  5239.6  795.58  5288.4   800.1
  5359.4  805.59  5520.7  813.74  5642.1   817.4  5921.1  821.64  5970.9  821.75
#Mann= 9 ,-1 , 0
  4615.5     .05       0  4620.5      .1       0    4691     .05       0
  4931.1     .16       0  4999.8     .07       0  5005.8     .16       0
  5288.4      .1       0  5520.7     .16       0  5921.1      .1       0
Bank Sta=4999.8,5005.8
XS Rating Curve= 0 ,0
Exp/Cntr=0.3,0.1

Type RM Length L Ch R = 1 ,3971    ,247,247,247
BEGIN DESCRIPTION:
PEDERNALES TRIB 3 9.0
END DESCRIPTION:
XS GIS Cut Line= 4
      2996745.56     10105980.23      2997131.86     10106214.62
      2997609.29     10106357.85      2998085.13      10106401.1
#Sta/Elev= 30
  4314.1  805.85    4363     804  4651.7  790.69  4739.9  787.35    4829  781.25
  4888.8   776.9  4898.1  772.37  4908.6   765.3  4921.8  761.08  4930.7  753.52
  4939.9  748.17  4954.9  742.86  4981.7  729.59  4990.2  726.78  4992.9  726.28
  4996.2  726.78    5013  726.99  5026.3  730.91  5032.4  734.87  5059.3  744.55
  5065.2     749  5086.1  757.45  5097.6  765.37  5117.4  790.33  5134.2  791.96
  5335.5  807.12  5414.2  811.62  5546.6  814.77  5607.8  816.32  5742.2  815.09
#Mann= 11 ,-1 , 0
  4314.1     .16       0    4363     .05       0  4651.7      .1       0
    4829     .16       0  4930.7     .12       0  4990.2     .07       0
  4996.2     .12       0  5032.4     .16       0  5134.2     .05       0
  5335.5      .1       0  5546.6     .05       0
Bank Sta=4990.2,4996.2
XS Rating Curve= 0 ,0
Exp/Cntr=0.3,0.1

Type RM Length L Ch R = 1 ,3724    ,639,639,639
BEGIN DESCRIPTION:
PEDERNALES TRIB 3 8.0
END DESCRIPTION:
XS GIS Cut Line= 4
      2996671.78     10105993.25      2997092.79     10106422.95
      2997418.32      10106579.2       2997930.5     10106592.22
#Sta/Elev= 30
  4177.4  807.84  4225.9  805.93  4491.4  795.03  4633.8   788.5  4851.8  777.57
  4865.1  776.22  4878.3  770.52  4887.7  767.59  4904.8  752.96    4933  742.35
  4962.7  727.02  4985.6  725.68  5004.1  724.48  5006.9  723.98  5010.1  724.48
  5023.6  726.85  5029.3   731.3  5040.4  736.09  5046.2   741.1  5062.6  746.25
  5068.9  750.51  5074.4  750.93  5084.8  756.52  5091.5  767.92  5106.9  767.71
  5136.8  779.42  5195.3  783.91  5293.9  791.13  5392.6  798.21  5652.4  813.28
#Mann= 11 ,-1 , 0
  4177.4     .16       0  4225.9     .05       0  4491.4      .1       0
  4633.8     .16       0  4878.3     .12       0  4985.6     .16       0
  5004.1     .07       0  5010.1     .16       0  5195.3      .1       0
  5293.9     .05       0  5392.6      .1       0
Bank Sta=5004.1,5010.1
XS Rating Curve= 0 ,0
Exp/Cntr=0.3,0.1

Type RM Length L Ch R = 1 ,3085    ,324,324,324
BEGIN DESCRIPTION:
PEDERNALES TRIB 3 7.0
END DESCRIPTION:
XS GIS Cut Line= 4
        2996598.     10105949.84      2996780.29     10106427.29
      2996775.95     10106852.64      2997513.27     10107008.78
#Sta/Elev= 30
    4181  809.64  4292.8  807.95  4386.5   806.7  4527.5  799.36  4628.5  790.63
  4748.5  778.14  4818.5  766.78  4848.5  748.16  4898.5  729.85  4965.5  715.23
  4968.3  714.73  4971.5  715.23  5008.5  715.91  5028.5  719.53  5098.5  752.48
  5115.5  770.56  5146.2   770.8  5151.3  776.82  5160.9   775.5  5171.1  778.03
  5195.9  778.66  5240.5  774.18  5245.6  778.07  5290.2  775.65  5295.3  780.13
  5333.9  774.88    5345  780.13  5477.8  781.36  5812.5  792.59  5871.1  796.74
#Mann= 8 ,-1 , 0
    4181     .16       0  4292.8     .05       0  4386.5      .1       0
  4628.5     .16       0  4965.5     .07       0  4971.5     .16       0
  5333.9     .05       0  5812.5      .1       0
Bank Sta=4965.5,4971.5
XS Rating Curve= 0 ,0
Exp/Cntr=0.3,0.1

Type RM Length L Ch R = 1 ,2761    ,504,504,504
BEGIN DESCRIPTION:
PEDERNALES TRIB 3 6.0
END DESCRIPTION:
XS GIS Cut Line= 4
      2995703.92     10106310.11       2996220.4     10106670.35
      2996806.34     10107017.57      2997518.12     10107060.97
#Sta/Elev= 30
  4061.5  810.07  4068.2  810.05  4430.7  802.69  4525.2  796.69  4532.3  796.16
  4651.4  789.34  4676.1  787.82  4786.9  781.53  4793.6  770.35  4808.4  764.02
    4824  745.53  4888.3  718.65  4996.4   708.7  4999.2   708.2  5002.4   708.7
  5020.9  717.05  5159.3  714.62  5260.6  749.05  5276.2  758.16    5282  754.93
  5291.9  760.63  5297.7  757.45  5313.3  767.33  5319.1  764.22  5334.7  776.84
  5433.9  781.63  5742.5  789.31  5803.1  789.86  6020.6  794.61  6085.4   798.5
#Mann= 13 ,-1 , 0
  4061.5     .16       0  4068.2     .05       0  4430.7      .1       0
  4525.2     .16       0  4532.3      .1       0  4651.4     .05       0
  4676.1     .16       0  4996.4     .07       0  5002.4     .16       0
  5433.9     .05       0  5742.5      .1       0  5803.1     .05       0
  6020.6      .1       0
Bank Sta=4996.4,5002.4
XS Rating Curve= 0 ,0
Exp/Cntr=0.3,0.1

Type RM Length L Ch R = 1 ,2257    ,602,602,602
BEGIN DESCRIPTION:
PEDERNALES TRIB 3 5.0
END DESCRIPTION:
XS GIS Cut Line= 4
      2995851.52     10107260.63      2996289.84     10107282.33
      2997049.39      10107225.9      2997578.88     10107108.72
#Sta/Elev= 30
  4190.8  804.03  4358.8  798.82  4593.5  788.13  4680.8  783.88  4746.1  777.52
  4768.7  775.88  4788.7  770.28  4813.5  768.11  4838.9  753.56  4848.9  749.71
    4889  737.27  4946.1  714.31  4979.2  702.66  4996.3  699.69    4999  699.19
  5002.3  699.69  5019.4  700.73  5083.8     721  5099.6  729.15  5149.7  742.63
  5169.8  751.48  5199.8  771.99  5209.9  777.03  5216.5  778.84  5255.1  780.38
  5431.3   787.4  5610.5  792.14  5794.8  796.84  5903.7  801.82  5933.6  803.97
#Mann= 8 ,-1 , 0
  4190.8     .05       0  4593.5      .1       0  4746.1     .16       0
  4996.3     .07       0  5002.3     .16       0  5255.1     .05       0
  5610.5      .1       0  5903.7     .05       0
Bank Sta=4996.3,5002.3
XS Rating Curve= 0 ,0
Exp/Cntr=0.3,0.1