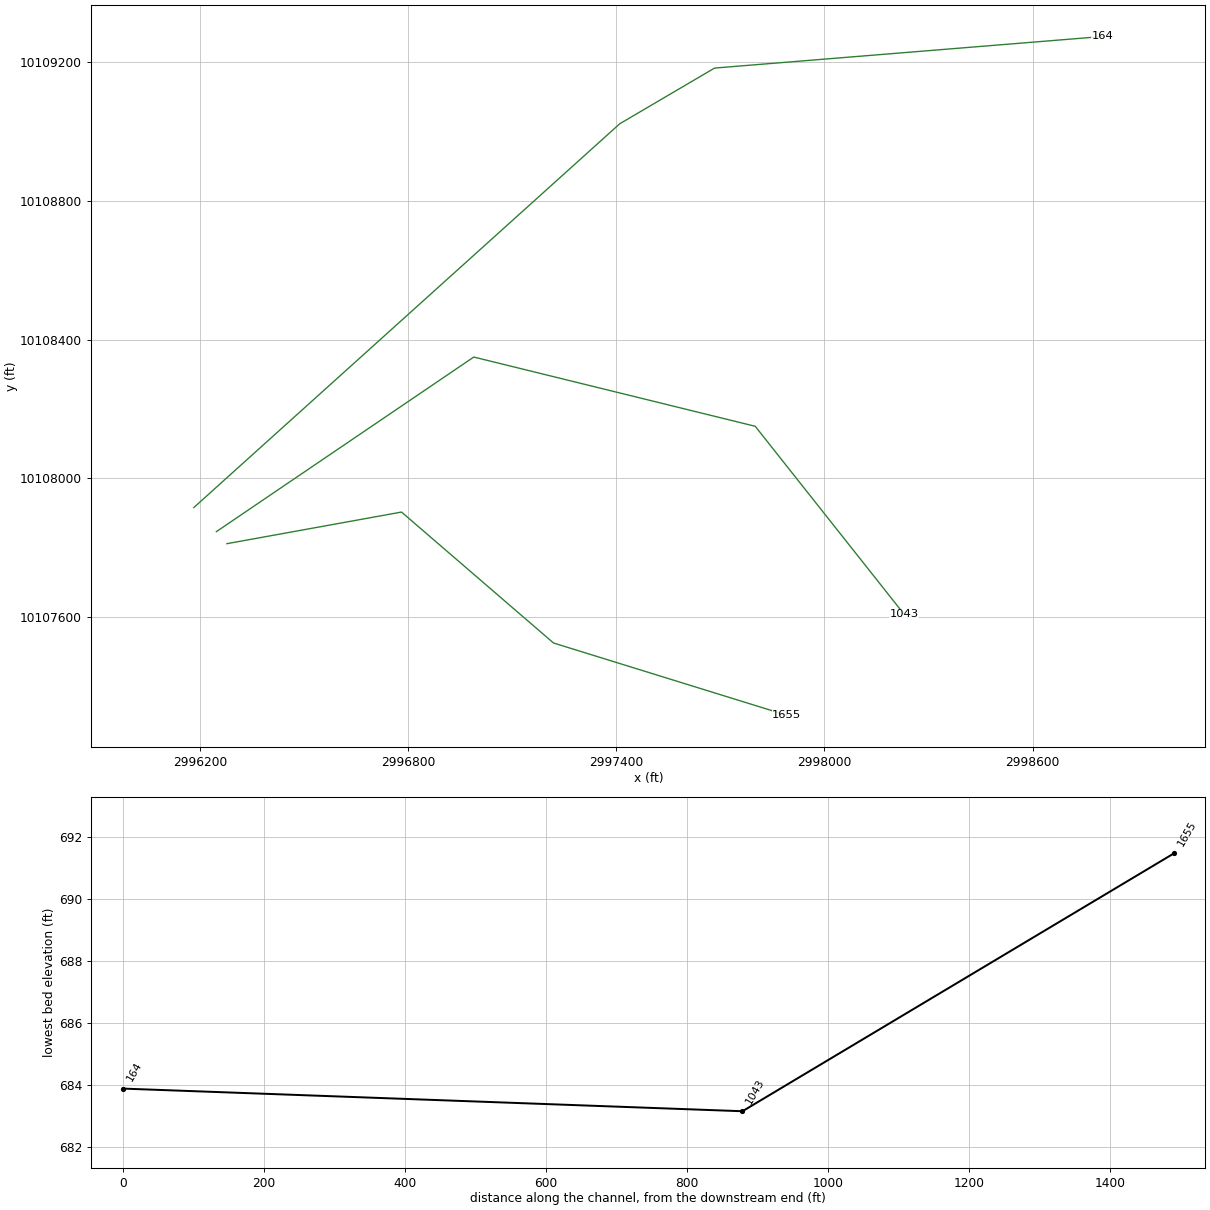
HEC-RAS study PEDERNALES TRIB 3.prj: PEDERNALES TRIB 3 Base Level Engineering

--- PEDERNALES TRIB 3.g01 (geometry) --- (continued)

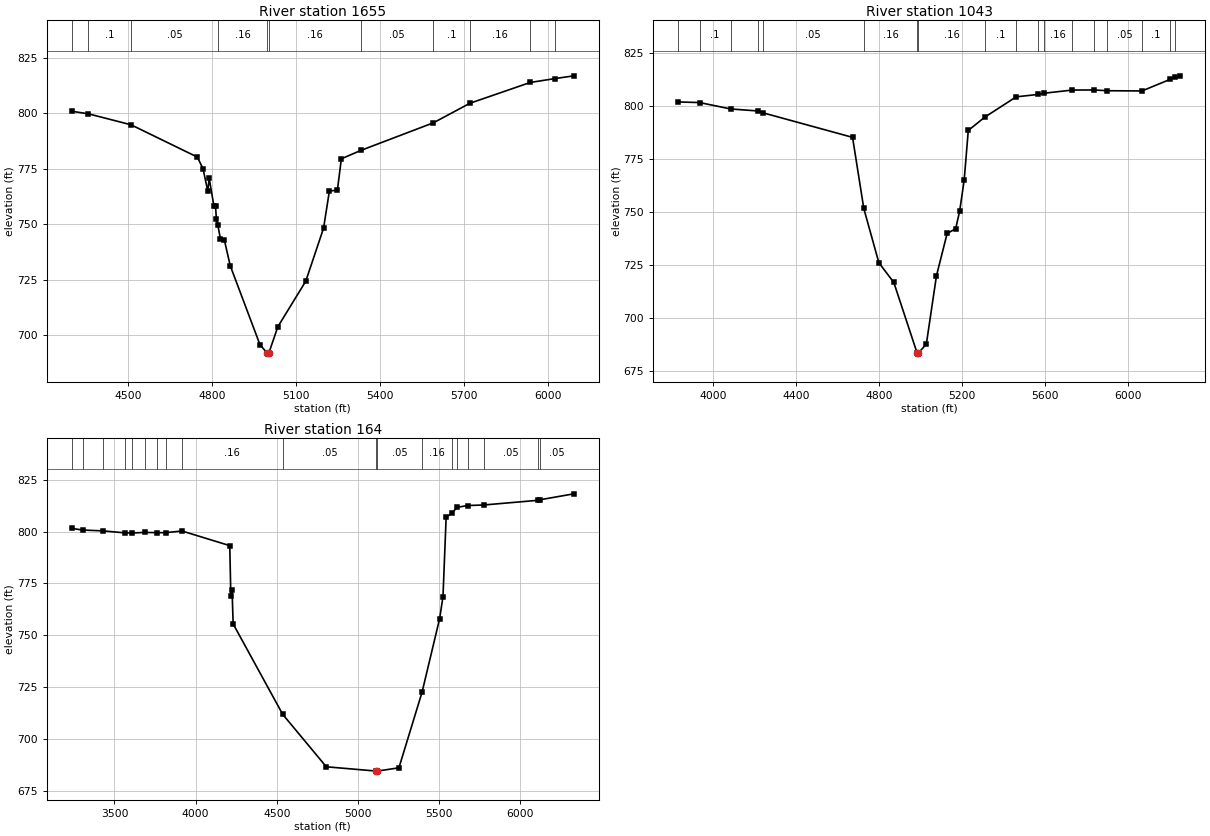
Type RM Length L Ch R = 1 ,1655    ,612,612,612
BEGIN DESCRIPTION:
PEDERNALES TRIB 3 3.0
END DESCRIPTION:
XS GIS Cut Line= 4
      2996276.78     10107811.83      2996780.29     10107902.99
      2997218.66     10107525.38      2997891.37     10107317.06
#Sta/Elev= 30
    4299  800.95  4358.6   799.8  4510.7  794.86  4747.9   780.3  4768.2  775.02
  4785.1  764.95  4790.2  770.71  4807.2  758.11  4812.8  758.11    4816  752.19
  4821.2   749.5  4830.3  743.47  4844.6  742.78  4865.4  731.33  4971.8  695.67
  4997.4  691.97  5000.1  691.47  5003.4  691.97  5035.5  703.81  5135.3  724.33
    5199  748.28  5219.8  765.03  5248.3  765.34  5262.6  779.53  5331.9  783.29
  5591.4  795.75    5722  804.56  5937.7  813.94  6025.8  815.68  6093.5  816.93
#Mann= 11 ,-1 , 0
    4299     .05       0  4358.6      .1       0  4510.7     .05       0
  4821.2     .16       0  4997.4     .07       0  5003.4     .16       0
  5331.9     .05       0  5591.4      .1       0    5722     .16       0
  5937.7      .1       0  6025.8     .05       0
Bank Sta=4997.4,5003.4
XS Rating Curve= 0 ,0
Exp/Cntr=0.3,0.1

Type RM Length L Ch R = 1 ,1043    ,879,879,879
BEGIN DESCRIPTION:
PEDERNALES TRIB 3 2.0
END DESCRIPTION:
XS GIS Cut Line= 4
       2996246.4     10107846.54      2996988.63     10108350.03
      2997800.26     10108150.38      2998229.58     10107608.32
#Sta/Elev= 30
  3829.9  801.81  3933.3  801.51  4083.2   798.5  4214.2  797.56  4237.8  796.72
  4671.6  785.14  4725.8  751.69  4798.7  726.14  4870.8  716.88  4983.3  683.66
  4986.1  683.16  4989.3  683.66  5027.9  687.91  5076.8  720.06  5128.2  739.92
  5169.4  742.15  5188.8  750.49  5210.6  765.08  5230.3  788.39  5310.6  794.69
  5461.6   804.2  5565.4  805.32    5597  805.91  5733.4   807.4  5839.7  807.43
  5901.3  807.08  6069.2  806.98  6203.9  812.39  6230.4  813.35  6254.1  814.09
#Mann= 18 ,-1 , 0
  3829.9     .05       0  3933.3      .1       0  4083.2     .05       0
  4214.2      .1       0  4237.8     .05       0  4725.8     .16       0
  4983.3     .07       0  4989.3     .16       0  5310.6      .1       0
  5461.6     .16       0  5565.4      .1       0    5597     .16       0
  5733.4     .05       0  5839.7      .1       0  5901.3     .05       0
  6069.2      .1       0  6203.9     .05       0  6230.4     .16       0
Bank Sta=4983.3,4989.3
XS Rating Curve= 0 ,0
Exp/Cntr=0.3,0.1

Type RM Length L Ch R = 1 ,164     ,0,0,0
BEGIN DESCRIPTION:
PEDERNALES TRIB 3 1.0
END DESCRIPTION:
XS GIS Cut Line= 4
      2996181.32     10107915.99      2997409.64     10109022.78
      2997683.07     10109183.37      2998802.86     10109274.51
#Sta/Elev= 30
  3236.9  801.58  3303.7   800.8  3431.6  800.37  3565.4  799.42  3607.8  799.37
  3687.6  799.64  3761.9  799.53  3815.5  799.52    3916  800.33  4210.5  793.26
  4217.2  768.74  4224.7  771.75  4231.4  755.47  4536.6  711.82  4805.4  686.47
  5114.2  684.39  5116.9  683.89  5120.2  684.39    5253  685.98  5395.6  722.51
  5503.8  758.01  5524.5  768.65  5543.9  806.94  5578.6  808.91  5611.8  811.76
  5677.3  812.63  5775.9  812.89    6113  815.17  6119.4  815.37  6330.9  818.28
#Mann= 19 ,-1 , 0
  3236.9     .05       0  3303.7     .16       0  3431.6      .1       0
  3565.4     .05       0  3607.8      .1       0  3687.6     .05       0
  3761.9      .1       0  3815.5     .05       0    3916     .16       0
  4536.6     .05       0  5114.2    .033       0  5120.2     .05       0
  5395.6     .16       0  5578.6      .1       0  5611.8     .16       0
  5677.3      .1       0  5775.9     .05       0    6113      .1       0
  6119.4     .05       0
Bank Sta=5114.2,5120.2
XS Rating Curve= 0 ,0
Exp/Cntr=0.3,0.1

Chan Stop Cuts=-1
Use User Specified Reach Order=0
Composite Channel Slope=5