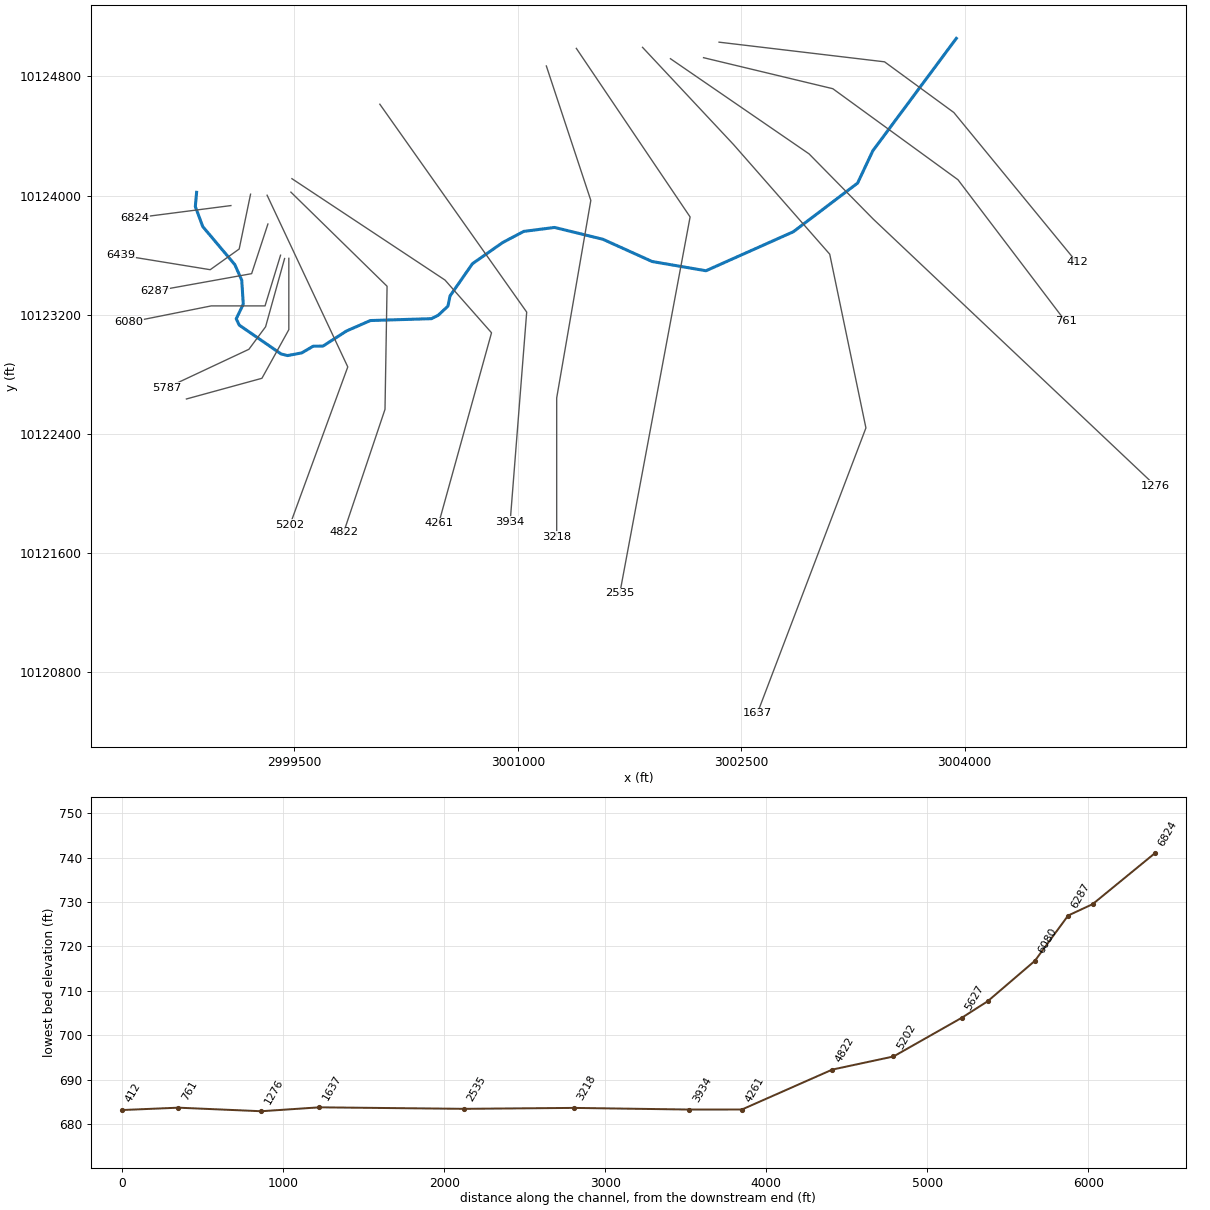
--- PEDERNALES TRIB 4.prj (project) ---

Proj Title=PEDERNALES TRIB 4 Base Level Engineering
Current Plan=p01
Default Exp/Contr=0.3,0.1
English Units
Geom File=g01
Flow File=f01
Plan File=p01
BEGIN DESCRIPTION:
PEDERNALES TRIB 4
END DESCRIPTION:

--- PEDERNALES TRIB 4.p01 (plan) ---

Plan Title=Multiple Run
Short Identifier=Multiple
Geom File=g01
Flow File=f01
Subcritical Flow
K Sum by GR= 0
Std Step Tol= 0.01
Critical Tol= 0.01
Num of Std Step Trials= 20
Max Error Tol= 0.3
Flow Tol Ratio= 0.001
Split Flow NTrial= 30
Split Flow Tol= 0.02
Split Flow Ratio= 0.02
Log Output Level= 0
Friction Slope Method= 1
Unsteady Friction Slope Method= 2
Unsteady Bridges Friction Slope Method= 1
Parabolic Critical Depth
Global Vel Dist=  1 , 1 , 1
Global Log Level= 0
CheckData=True
Encroach Param= -1, 0, 0, 0
BEGIN DESCRIPTION:
Multiple Run
END DESCRIPTION:

--- PEDERNALES TRIB 4.f01 (steady flow) ---

Flow Title=Multiple
Number of Profiles=7
Profile Names=10-year,25-year,50-year,1pct_min,100-year,1pct_plu,500-year
River Rch & RM= PEDERNALES TRIB ,Reach-1,6824
     908    1332    1706    1601    2166    2929    3502
River Rch & RM= PEDERNALES TRIB ,Reach-1,5202
    1664    2500    3251    3088    4176    5648    6924
River Rch & RM= PEDERNALES TRIB ,Reach-1,1276
    1888    2849    3715    3538    4784    6470    7971
Boundary for River Rch & Prof#=PEDERNALES TRIB ,Reach-1,1
Up Type=0
Dn Type=3
Dn Slope=0.005
Boundary for River Rch & Prof#=PEDERNALES TRIB ,Reach-1,2
Up Type=0
Dn Type=3
Dn Slope=0.005
Boundary for River Rch & Prof#=PEDERNALES TRIB ,Reach-1,3
Up Type=0
Dn Type=3
Dn Slope=0.005
Boundary for River Rch & Prof#=PEDERNALES TRIB ,Reach-1,4
Up Type=0
Dn Type=3
Dn Slope=0.005
Boundary for River Rch & Prof#=PEDERNALES TRIB ,Reach-1,5
Up Type=0
Dn Type=3
Dn Slope=0.005
Boundary for River Rch & Prof#=PEDERNALES TRIB ,Reach-1,6
Up Type=0
Dn Type=3
Dn Slope=0.005
Boundary for River Rch & Prof#=PEDERNALES TRIB ,Reach-1,7
Up Type=0
Dn Type=3
Dn Slope=0.005

--- PEDERNALES TRIB 4.g01 (geometry) ---

Geom Title=Existing Conditions

River Reach=PEDERNALES TRIB ,Reach-1
Reach XY= 30
      2998842.70     10124022.20      2998834.02     10123926.72
      2998883.93     10123792.17      2999099.22     10123536.55
      2999145.61     10123432.52      2999156.19     10123271.28
      2999108.70     10123172.78      2999129.07     10123130.39
      2999409.83     10122936.73      2999452.84     10122925.93
      2999548.47     10122943.73      2999625.60     10122988.95
      2999690.78     10122989.42      2999849.53     10123091.16
      3000009.64     10123161.17      3000419.43     10123173.70
      3000465.19     10123196.81      3000530.33     10123257.96
      3000544.31     10123326.20      3000694.76     10123542.76
      3000898.23     10123685.17      3001039.70     10123759.81
      3001246.46     10123786.15      3001570.24     10123707.07
      3001901.15     10123557.53      3002262.95     10123495.48
      3002849.48     10123757.29      3003281.05     10124084.13
      3003383.17     10124300.92      3003944.08     10125056.06

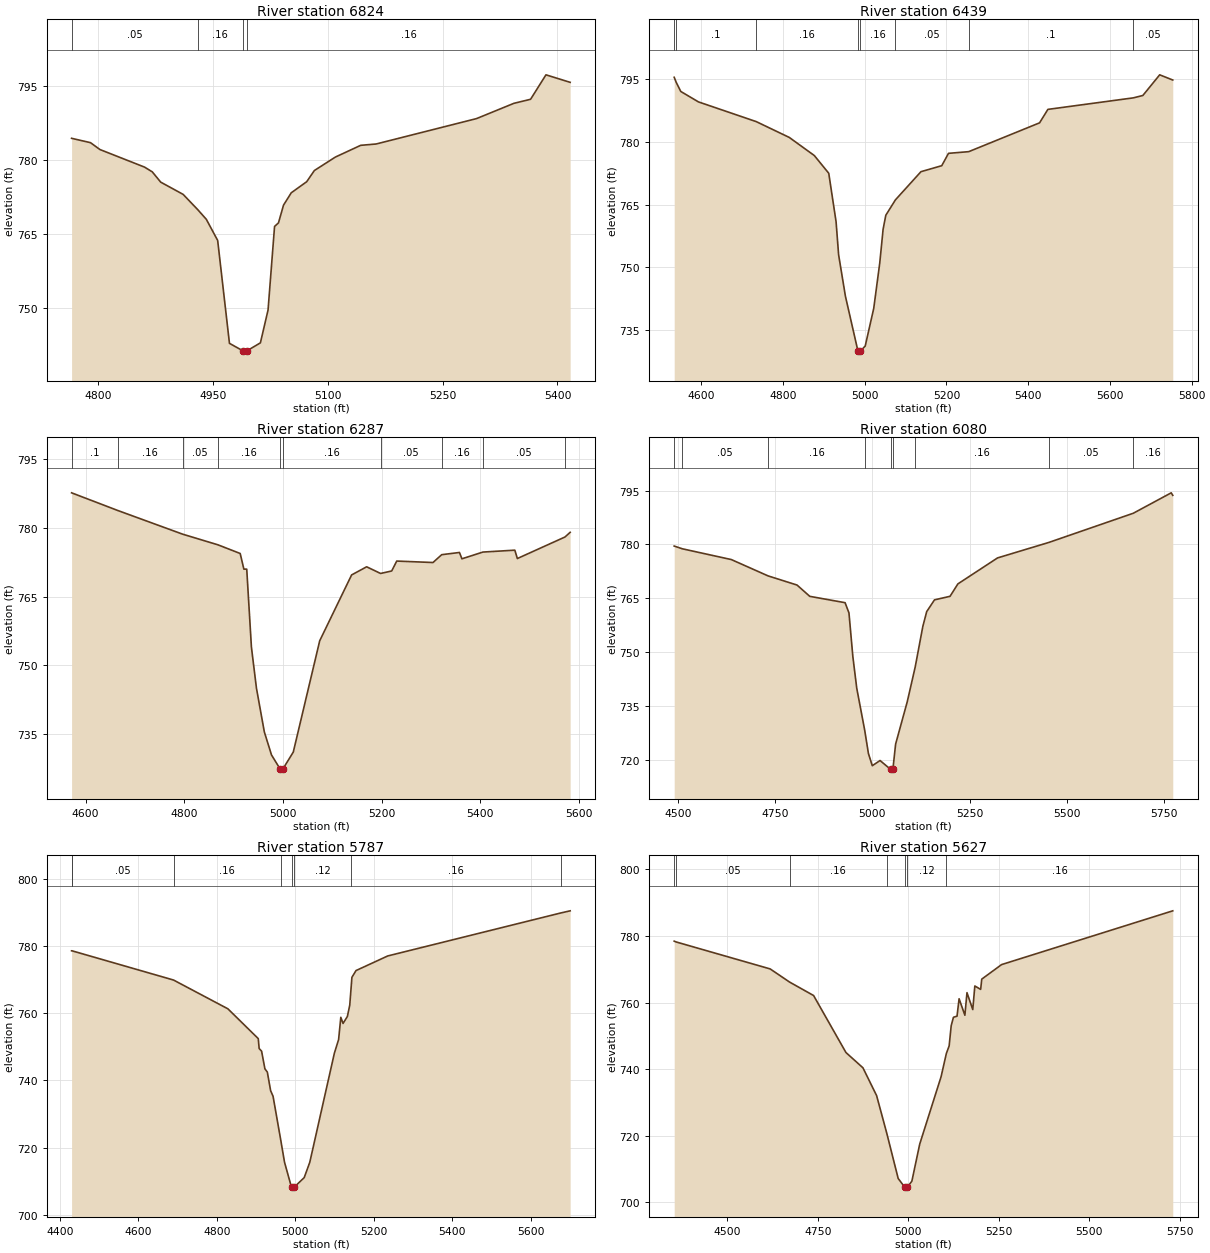
Type RM Length L Ch R = 1,6824,385,385,385
BEGIN DESCRIPTION:
PEDERNALES TRIB 4 16.0
END DESCRIPTION:
XS GIS Cut Line= 2
      2999073.00     10123933.10      2998427.15     10123849.77
#Sta/Elev= 30
  4765.4  784.43  4790.1  783.55  4802.4  782.16  4860.7  778.60  4870.8  777.64
  4881.8  775.56  4911.1  773.08  4930.3  769.97  4941.4  768.03  4956.2  763.76
  4971.6  742.93  4988.8  741.45  4991.5  740.95  4994.8  741.45  5012.0  743.03
  5022.0  749.67  5030.5  766.59  5035.6  767.31  5042.2  770.90  5052.3  773.40
  5072.5  775.65  5082.5  777.91  5109.9  780.63  5143.0  783.01  5163.2  783.28
  5294.3  788.42  5343.1  791.51  5364.9  792.33  5385.0  797.28  5416.6  795.76
#Mann=4,-1,0
  4765.4    0.05       0  4930.3    0.16       0  4988.8    0.07       0
  4994.8    0.16       0
Bank Sta=4988.8,4994.8
Exp/Cntr=0.3,0.1

Type RM Length L Ch R = 1,6439,152,152,152
BEGIN DESCRIPTION:
PEDERNALES TRIB 4 15.0
END DESCRIPTION:
XS GIS Cut Line= 4
      2999204.94     10124009.51      2999128.54     10123641.43
      2998934.10     10123502.54      2998336.84     10123599.77
#Sta/Elev= 30
  4533.8  795.37  4538.7  794.17  4549.9  791.99  4593.1  789.50  4734.6  784.79
  4815.5  781.01  4876.7  776.69  4912.0  772.46  4929.9  760.90  4936.1  753.02
  4952.8  743.10  4983.4  730.03  4986.2  729.53  4989.4  730.03  5001.2  731.22
  5022.1  740.23  5036.8  751.06  5045.0  759.11  5051.6  762.44  5075.2  766.12
  5137.6  772.84  5188.5  774.27  5205.0  777.22  5254.5  777.62  5427.9  784.50
  5448.2  787.71  5657.2  790.46  5680.6  791.03  5721.8  795.96  5753.8  794.72
#Mann=8,-1,0
  4533.8    0.16       0  4538.7     0.1       0  4734.6    0.16       0
  4983.4    0.07       0  4989.4    0.16       0  5075.2    0.05       0
  5254.5     0.1       0  5657.2    0.05       0
Bank Sta=4983.4,4989.4
Exp/Cntr=0.3,0.1

Type RM Length L Ch R = 1,6287,207,207,207
BEGIN DESCRIPTION:
Mapping XS d0ba2a2e
END DESCRIPTION:
XS GIS Cut Line= 3
      2999321.49     10123809.32      2999212.11     10123475.95
      2998562.30     10123358.99
#Sta/Elev= 30
  4571.5  787.58  4665.5  783.72  4796.6  778.58  4868.2  776.26  4913.4  774.37
  4920.9  770.96  4926.7  770.96  4936.2  753.97  4946.4  745.03  4962.4  735.50
  4976.9  730.50  4994.2  727.47  4996.9  726.97  5000.2  727.47  5021.1  731.12
  5074.7  755.36  5139.4  769.70  5169.9  771.47  5198.1  770.02  5220.7  770.56
  5230.9  772.72  5304.4  772.40  5322.1  774.11  5358.1  774.59  5363.1  773.21
  5405.7  774.68  5470.4  775.09  5475.5  773.27  5572.1  777.96  5582.6  778.98
#Mann=10,-1,0
  4571.5     0.1       0  4665.5    0.16       0  4796.6    0.05       0
  4868.2    0.16       0  4994.2    0.07       0  5000.2    0.16       0
  5198.1    0.05       0  5322.1    0.16       0  5405.7    0.05       0
  5572.1    0.16       0
Bank Sta=4994.2,5000.2
Exp/Cntr=0.3,0.1

Type RM Length L Ch R = 1,6080,293,293,293
BEGIN DESCRIPTION:
PEDERNALES TRIB 4 14.0
END DESCRIPTION:
XS GIS Cut Line= 4
      2999406.32     10123599.78      2999302.15     10123259.49
      2998941.04     10123259.49      2998386.42     10123148.56
#Sta/Elev= 30
  4490.2  779.55  4511.0  778.79  4637.2  775.78  4731.6  771.23  4806.2  768.67
  4839.0  765.52  4929.8  763.75  4939.8  760.89  4949.8  748.71  4959.8  739.90
  4980.4  728.10  4989.8  721.70  4999.8  718.27  5019.8  719.72  5046.8  717.26
  5049.5  716.76  5052.8  717.26  5059.8  724.30  5089.8  736.14  5110.2  745.82
  5129.8  757.13  5139.8  761.27  5159.8  764.54  5199.8  765.53  5220.0  768.99
  5322.0  776.24  5454.3  780.57  5671.2  788.70  5768.8  794.40  5772.8  793.70
#Mann=9,-1,0
  4490.2    0.16       0  4511.0    0.05       0  4731.6    0.16       0
  4980.4    0.12       0  5046.8    0.07       0  5052.8    0.12       0
  5110.2    0.16       0  5454.3    0.05       0  5671.2    0.16       0
Bank Sta=5046.8,5052.8
Exp/Cntr=0.3,0.1

Type RM Length L Ch R = 1,5787,160,160,160
BEGIN DESCRIPTION:
Mapping XS e4499b30
END DESCRIPTION:
XS GIS Cut Line= 4
      2999433.47     10123577.54      2999305.86     10123119.18
      2999193.88     10122968.14      2998644.37     10122710.31
#Sta/Elev= 30
  4430.0  778.54  4431.1  778.54  4689.8  769.85  4828.4  761.29  4905.8  752.43
  4908.1  749.48  4914.3  748.70  4922.7  743.46  4928.9  742.48  4937.3  736.95
  4943.5  735.30  4963.0  722.34  4972.8  715.64  4990.6  708.17  4993.4  707.67
  4996.6  708.17  5022.9  711.09  5037.1  715.64  5099.8  748.10  5110.6  752.15
  5116.2  758.77  5121.9  756.94  5132.9  759.00  5139.0  762.38  5142.3  767.34
  5144.5  770.65  5155.0  772.67  5235.8  777.01  5676.8  789.79  5700.8  790.43
#Mann=8,-1,0
  4430.0    0.16       0  4431.1    0.05       0  4689.8    0.16       0
  4963.0    0.12       0  4990.6    0.07       0  4996.6    0.12       0
  5142.3    0.16       0  5676.8    0.05       0
Bank Sta=4990.6,4996.6
Exp/Cntr=0.3,0.1

Type RM Length L Ch R = 1,5627,425,425,425
BEGIN DESCRIPTION:
PEDERNALES TRIB 4 13.0
END DESCRIPTION:
XS GIS Cut Line= 4
      2999461.88     10123578.91      2999461.88     10123099.77
      2999281.32     10122773.38      2998774.34     10122634.48
#Sta/Elev= 30
  4353.4  778.45  4358.8  778.21  4618.6  770.11  4672.3  766.16  4738.6  762.12
  4828.1  744.99  4875.0  740.41  4912.8  732.05  4941.0  720.69  4972.4  707.16
  4991.1  704.47  4993.9  703.97  4997.1  704.47  5010.2  706.36  5031.9  717.50
  5090.9  737.72  5105.5  744.71  5113.2  746.98  5118.9  753.08  5125.1  755.59
  5135.0  755.92  5140.7  761.15  5156.7  756.20  5162.5  762.98  5178.5  757.90
  5184.2  764.99  5200.3  763.96  5203.3  767.04  5258.1  771.41  5731.2  787.56
#Mann=7,-1,0
  4353.4    0.16       0  4358.8    0.05       0  4672.3    0.16       0
  4941.0    0.12       0  4991.1    0.07       0  4997.1    0.12       0
  5105.5    0.16       0
Bank Sta=4991.1,4997.1
Exp/Cntr=0.3,0.1

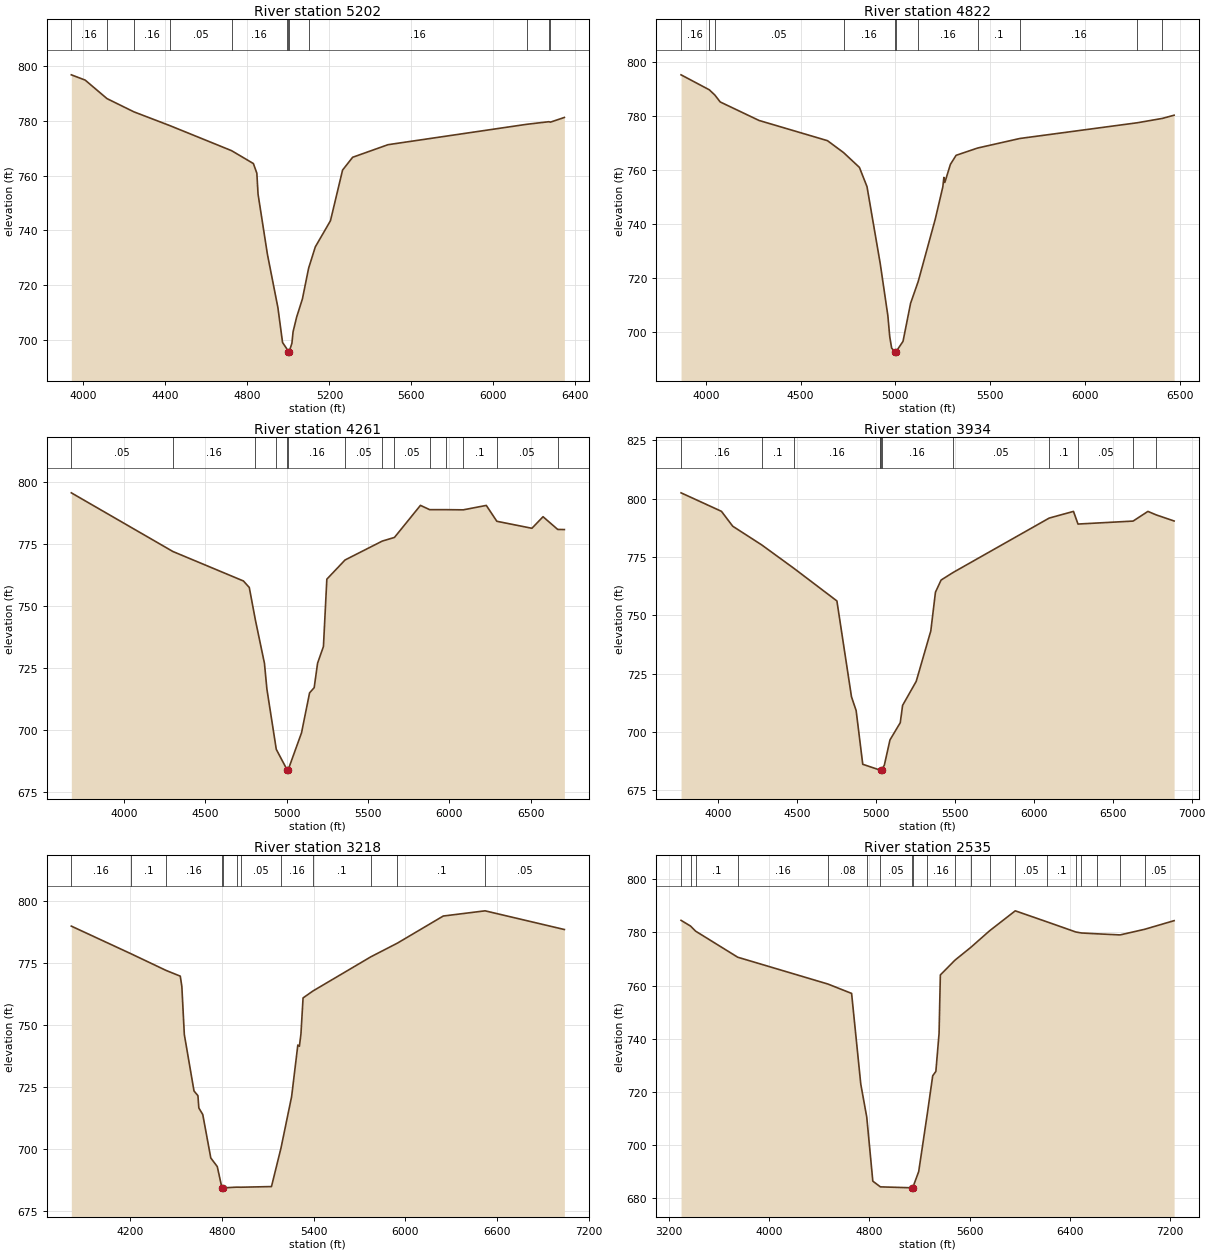
Type RM Length L Ch R = 1,5202,380,380,380
BEGIN DESCRIPTION:
PEDERNALES TRIB 4 12.0
END DESCRIPTION:
XS GIS Cut Line= 3
      2999316.06     10124002.51      2999857.71     10122849.77
      2999469.09     10121788.01
#Sta/Elev= 30
  3941.5  796.78  4009.0  794.86  4115.5  788.10  4246.5  783.28  4422.3  778.24
  4722.7  769.12  4829.3  764.41  4846.2  760.88  4852.1  753.23  4897.7  731.33
  4948.8  711.88  4971.6  699.11  4992.1  696.84  4997.8  695.74  5000.6  695.24
  5003.8  695.74  5017.2  698.86  5022.9  703.05  5040.1  708.35  5068.4  715.02
  5098.6  726.21  5131.3  734.01  5205.2  743.55  5264.2  762.03  5313.4  766.70
  5485.9  771.29  6162.2  778.73  6269.8  779.67  6278.0  779.52  6345.8  781.23
#Mann=12,-1,0
  3941.5    0.16       0  4115.5     0.1       0  4246.5    0.16       0
  4422.3    0.05       0  4722.7    0.16       0  4992.1    0.12       0
  4997.8    0.07       0  5003.8    0.12       0  5098.6    0.16       0
  6162.2     0.1       0  6269.8    0.05       0  6278.0     0.1       0
Bank Sta=4997.8,5003.8
Exp/Cntr=0.3,0.1

Type RM Length L Ch R = 1,4822,561,561,561
BEGIN DESCRIPTION:
PEDERNALES TRIB 4 11.0
END DESCRIPTION:
XS GIS Cut Line= 4
      2999475.76     10124023.38      3000121.60     10123391.43
      3000107.71     10122565.04      2999829.94     10121738.67
#Sta/Elev= 30
  3868.9  795.14  4018.1  789.60  4047.2  787.67  4075.6  785.11  4280.7  778.27
  4641.4  770.81  4726.4  766.41  4810.2  760.93  4850.2  753.81  4920.2  725.29
  4960.2  706.14  4970.2  698.37  4980.2  694.15  4997.2  692.79  5000.0  692.29
  5003.2  692.79  5040.2  696.64  5080.2  710.72  5120.1  718.71  5210.2  741.76
  5250.3  753.74  5255.8  757.23  5260.8  755.36  5290.3  762.05  5320.3  765.39
  5434.0  768.09  5657.2  771.62  6277.3  777.43  6408.7  779.03  6470.8  780.22
#Mann=11,-1,0
  3868.9    0.16       0  4018.1     0.1       0  4047.2    0.05       0
  4726.4    0.16       0  4997.2    0.07       0  5003.2    0.16       0
  5120.1    0.16       0  5434.0     0.1       0  5657.2    0.16       0
  6277.3     0.1       0  6408.7    0.05       0
Bank Sta=4997.2,5003.2
Exp/Cntr=0.3,0.1

Type RM Length L Ch R = 1,4261,327,327,327
BEGIN DESCRIPTION:
PEDERNALES TRIB 4 10.0
END DESCRIPTION:
XS GIS Cut Line= 4
      2999482.69     10124113.67      3000510.49     10123433.10
      3000822.99     10123078.93      3000468.81     10121801.13
#Sta/Elev= 30
  3675.9  795.69  4300.5  771.99  4733.8  760.10  4769.9  757.47  4807.6  744.28
  4863.2  726.85  4878.2  716.45  4935.9  692.10  5002.8  683.81  5005.5  683.31
  5008.8  683.81  5091.1  698.78  5140.5  714.90  5168.9  717.02  5189.8  726.91
  5225.8  733.64  5246.7  760.82  5358.6  768.57  5587.3  776.20  5662.4  777.68
  5822.2  790.63  5878.8  788.89  5982.1  788.89  6085.3  788.82  6226.9  790.61
  6291.8  784.20  6507.3  781.37  6575.8  786.04  6665.8  780.91  6706.9  780.86
#Mann=14,-1,0
  3675.9    0.05       0  4300.5    0.16       0  4807.6    0.12       0
  4935.9    0.16       0  5002.8    0.07       0  5008.8    0.16       0
  5358.6    0.05       0  5587.3     0.1       0  5662.4    0.05       0
  5878.8     0.1       0  5982.1    0.05       0  6085.3     0.1       0
  6291.8    0.05       0  6665.8     0.1       0
Bank Sta=5002.8,5008.8
Exp/Cntr=0.3,0.1

Type RM Length L Ch R = 1,3934,716,716,716
BEGIN DESCRIPTION:
PEDERNALES TRIB 4 9.0
END DESCRIPTION:
XS GIS Cut Line= 3
      3000072.98     10124613.66      3001059.10     10123217.82
      3000948.01     10121808.43
#Sta/Elev= 30
  3766.1  802.56  4022.0  794.63  4093.4  788.25  4277.2  780.23  4481.8  770.16
  4753.2  756.23  4845.5  715.18  4875.1  709.22  4916.9  686.24  5023.3  683.81
  5027.7  683.81  5029.7  683.80  5032.4  683.30  5035.7  683.80  5053.6  685.86
  5089.3  696.67  5154.5  704.06  5169.3  711.48  5255.5  721.77  5347.8  743.35
  5377.4  759.99  5413.1  765.18  5488.5  768.40  6097.8  791.74  6251.6  794.60
  6280.1  789.18  6629.1  790.45  6723.1  794.60  6774.8  793.12  6888.9  790.49
#Mann=12,-1,0
  3766.1    0.16       0  4277.2     0.1       0  4481.8    0.16       0
  5023.3     0.1       0  5027.7    0.16       0  5029.7    0.07       0
  5035.7    0.16       0  5488.5    0.05       0  6097.8     0.1       0
  6280.1    0.05       0  6629.1    0.08       0  6774.8    0.05       0
Bank Sta=5029.7,5035.7
Exp/Cntr=0.3,0.1

Type RM Length L Ch R = 1,3218,683,683,683
BEGIN DESCRIPTION:
PEDERNALES TRIB 4 8.0
END DESCRIPTION:
XS GIS Cut Line= 4
      3001191.05     10124870.58      3001489.65     10123967.82
      3001260.49     10122641.43      3001260.49     10121710.84
#Sta/Elev= 30
  3814.4  789.77  4205.5  778.61  4435.2  771.88  4527.6  769.59  4537.9  765.45
  4554.1  746.05  4617.5  723.28  4643.2  721.36  4649.2  716.41  4674.8  713.78
  4727.4  696.24  4769.9  692.76  4800.3  684.17  4803.0  683.67  4806.3  684.17
  4896.2  684.47  4924.0  684.44  5124.6  684.70  5186.8  700.22  5256.5  721.02
  5297.1  741.79  5307.3  741.31  5317.4  746.18  5331.4  760.81  5396.6  763.62
  5775.1  777.39  5949.3  782.92  6249.0  793.84  6522.9  795.94  7041.9  788.40
#Mann=12,-1,0
  3814.4    0.16       0  4205.5     0.1       0  4435.2    0.16       0
  4800.3   0.033       0  4806.3    0.16       0  4896.2     0.1       0
  4924.0    0.05       0  5186.8    0.16       0  5396.6     0.1       0
  5775.1    0.05       0  5949.3     0.1       0  6522.9    0.05       0
Bank Sta=4800.3,4806.3
Exp/Cntr=0.3,0.1

Type RM Length L Ch R = 1,2535,898,898,898
BEGIN DESCRIPTION:
PEDERNALES TRIB 4 6.0
END DESCRIPTION:
XS GIS Cut Line= 3
      3001392.45     10124988.63      3002156.32     10123856.71
      3001684.09     10121328.89
#Sta/Elev= 30
  3296.4  784.55  3372.5  782.39  3412.2  780.50  3749.0  770.68  4469.4  760.59
  4658.2  757.07  4731.5  722.96  4779.2  710.55  4827.7  686.46  4888.3  684.31
  5140.1  683.96  5142.9  683.46  5146.1  683.96  5194.0  690.05  5263.0  711.89
  5305.9  726.10  5331.1  727.73  5356.7  742.04  5366.9  764.01  5483.7  769.58
  5609.7  774.37  5759.5  780.60  5965.1  788.13  6216.5  784.02  6448.1  780.18
  6493.0  779.80  6619.6  779.48  6802.1  779.07  6997.1  781.17  7233.5  784.43
#Mann=20,-1,0
  3296.4     0.1       0  3372.5    0.16       0  3412.2     0.1       0
  3749.0    0.16       0  4469.4    0.08       0  4779.2    0.16       0
  4888.3    0.05       0  5140.1   0.033       0  5146.1    0.05       0
  5263.0    0.16       0  5483.7     0.1       0  5609.7    0.05       0
  5759.5     0.1       0  5965.1    0.05       0  6216.5     0.1       0
  6448.1    0.05       0  6493.0    0.16       0  6619.6     0.1       0
  6802.1     0.1       0  6997.1    0.05       0
Bank Sta=5140.1,5146.1
Exp/Cntr=0.3,0.1

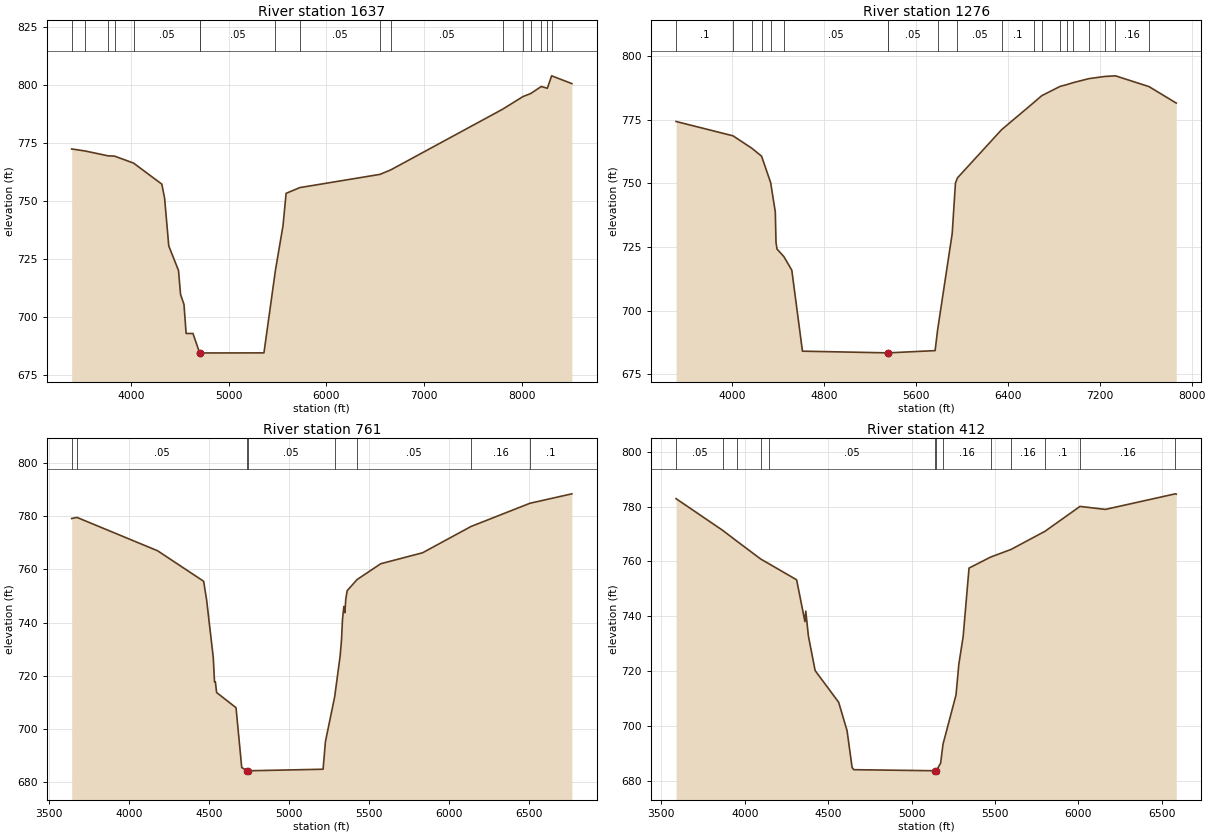
Type RM Length L Ch R = 1,1637,361,361,361
BEGIN DESCRIPTION:
PEDERNALES TRIB 4 4.0
END DESCRIPTION:
XS GIS Cut Line= 5
      3001836.88     10124995.60      3002447.99     10124342.82
      3003093.82     10123606.71      3003336.88     10122440.04
      3002607.73     10120523.42
#Sta/Elev= 30
  3394.8  772.37  3530.7  771.51  3768.5  769.39  3833.2  769.28  4027.6  766.27
  4316.7  757.19  4345.2  751.14  4387.9  730.50  4487.3  719.94  4508.4  709.56
  4543.5  705.25  4565.4  692.72  4635.6  692.70  4703.8  684.30  4706.5  683.80
  4709.8  684.30  5361.3  684.34  5479.2  720.11  5556.4  739.27  5587.9  753.21
  5728.4  755.69  6547.9  761.40  6657.0  763.30  7802.3  789.52  8010.0  794.97
  8090.1  796.31  8197.0  799.32  8259.8  798.58  8303.9  803.94  8510.6  800.58
#Mann=17,-1,0
  3394.8    0.16       0  3530.7     0.1       0  3768.5    0.16       0
  3833.2     0.1       0  4027.6    0.05       0  4703.8   0.033       0
  4709.8    0.05       0  5479.2    0.16       0  5728.4    0.05       0
  6547.9     0.1       0  6657.0    0.05       0  7802.3    0.16       0
  8010.0     0.1       0  8090.1    0.05       0  8197.0     0.1       0
  8259.8    0.05       0  8303.9    0.16       0
Bank Sta=4703.8,4709.8
Exp/Cntr=0.3,0.1

Type RM Length L Ch R = 1,1276,515,515,515
BEGIN DESCRIPTION:
PEDERNALES TRIB 4 3.0
END DESCRIPTION:
XS GIS Cut Line= 4
      3002024.40     10124919.20      3002954.93     10124280.32
      3003385.49     10123842.82      3005281.35     10122051.13
#Sta/Elev= 30
  3515.0  774.37  4010.4  768.74  4174.1  763.85  4258.6  760.75  4337.7  750.36
  4378.3  738.81  4384.4  726.83  4393.2  724.22  4452.1  721.30  4521.8  715.92
  4614.5  684.08  5355.0  683.42  5357.7  682.92  5361.0  683.42  5768.5  684.30
  5790.1  692.43  5917.0  730.29  5945.3  750.13  5962.9  752.20  6347.0  771.16
  6629.8  781.93  6695.9  784.51  6854.8  788.15  6912.7  788.85  6969.9  789.65
  7107.0  791.22  7244.0  792.07  7337.1  792.32  7628.9  788.09  7866.1  781.60
#Mann=20,-1,0
  3515.0     0.1       0  4010.4    0.08       0  4174.1    0.08       0
  4258.6    0.05       0  4337.7    0.08       0  4452.1    0.05       0
  5355.0   0.033       0  5361.0    0.05       0  5790.1    0.16       0
  5962.9    0.05       0  6347.0     0.1       0  6629.8    0.05       0
  6695.9    0.16       0  6854.8     0.1       0  6912.7    0.05       0
  6969.9     0.1       0  7107.0     0.1       0  7244.0     0.1       0
  7337.1    0.16       0  7628.9    0.05       0
Bank Sta=5355,5361
Exp/Cntr=0.3,0.1

Type RM Length L Ch R = 1,761,349,349,349
BEGIN DESCRIPTION:
PEDERNALES TRIB 4 2.0
END DESCRIPTION:
XS GIS Cut Line= 4
      3002246.58     10124926.16      3003114.65     10124717.82
      3003954.93     10124106.71      3004677.16     10123155.32
#Sta/Elev= 30
  3643.1  779.13  3676.1  779.55  4179.8  767.01  4467.8  755.53  4486.1  748.69
  4528.1  726.88  4535.8  717.71  4541.3  717.71  4549.0  713.67  4670.3  707.96
  4705.9  685.49  4738.4  684.22  4741.2  683.72  4744.4  684.22  5214.4  684.81
  5229.1  695.20  5286.7  712.00  5321.0  727.39  5329.5  733.41  5335.7  741.18
  5344.2  746.05  5350.4  743.67  5356.6  748.97  5365.1  751.99  5426.8  756.16
  5574.8  762.12  5836.5  766.25  6138.5  776.12  6507.4  784.87  6769.3  788.42
#Mann=8,-1,0
  3643.1     0.1       0  3676.1    0.05       0  4738.4   0.033       0
  4744.4    0.05       0  5286.7    0.16       0  5426.8    0.05       0
  6138.5    0.16       0  6507.4     0.1       0
Bank Sta=4738.4,4744.4
Exp/Cntr=0.3,0.1

Type RM Length L Ch R = 1,412,0,0,0
BEGIN DESCRIPTION:
PEDERNALES TRIB 4 1.0
END DESCRIPTION:
XS GIS Cut Line= 4
      3002350.76     10125030.32      3003461.88     10124898.38
      3003927.15     10124558.10      3004753.49     10123551.22
#Sta/Elev= 30
  3588.0  782.90  3867.7  771.33  3953.8  767.34  4095.5  760.88  4142.8  759.23
  4310.7  753.31  4360.4  738.06  4365.4  741.88  4381.2  732.81  4421.5  720.21
  4562.5  708.67  4612.9  698.31  4643.1  684.88  4653.1  684.08  5141.6  683.69
  5144.4  683.19  5147.6  683.69  5173.5  686.44  5188.1  693.41  5265.9  711.34
  5282.8  722.56  5308.7  732.60  5343.9  757.59  5472.6  761.58  5596.2  764.40
  5799.1  771.00  6009.0  780.07  6161.2  778.98  6580.3  784.66  6585.9  784.55
#Mann=13,-1,0
  3588.0    0.05       0  3867.7     0.1       0  3953.8    0.05       0
  4095.5     0.1       0  4142.8    0.05       0  5141.6   0.033       0
  5147.6    0.05       0  5188.1    0.16       0  5472.6    0.05       0
  5596.2    0.16       0  5799.1     0.1       0  6009.0    0.16       0
  6580.3     0.1       0
Bank Sta=5141.6,5147.6
Exp/Cntr=0.3,0.1

Chan Stop Cuts=-1