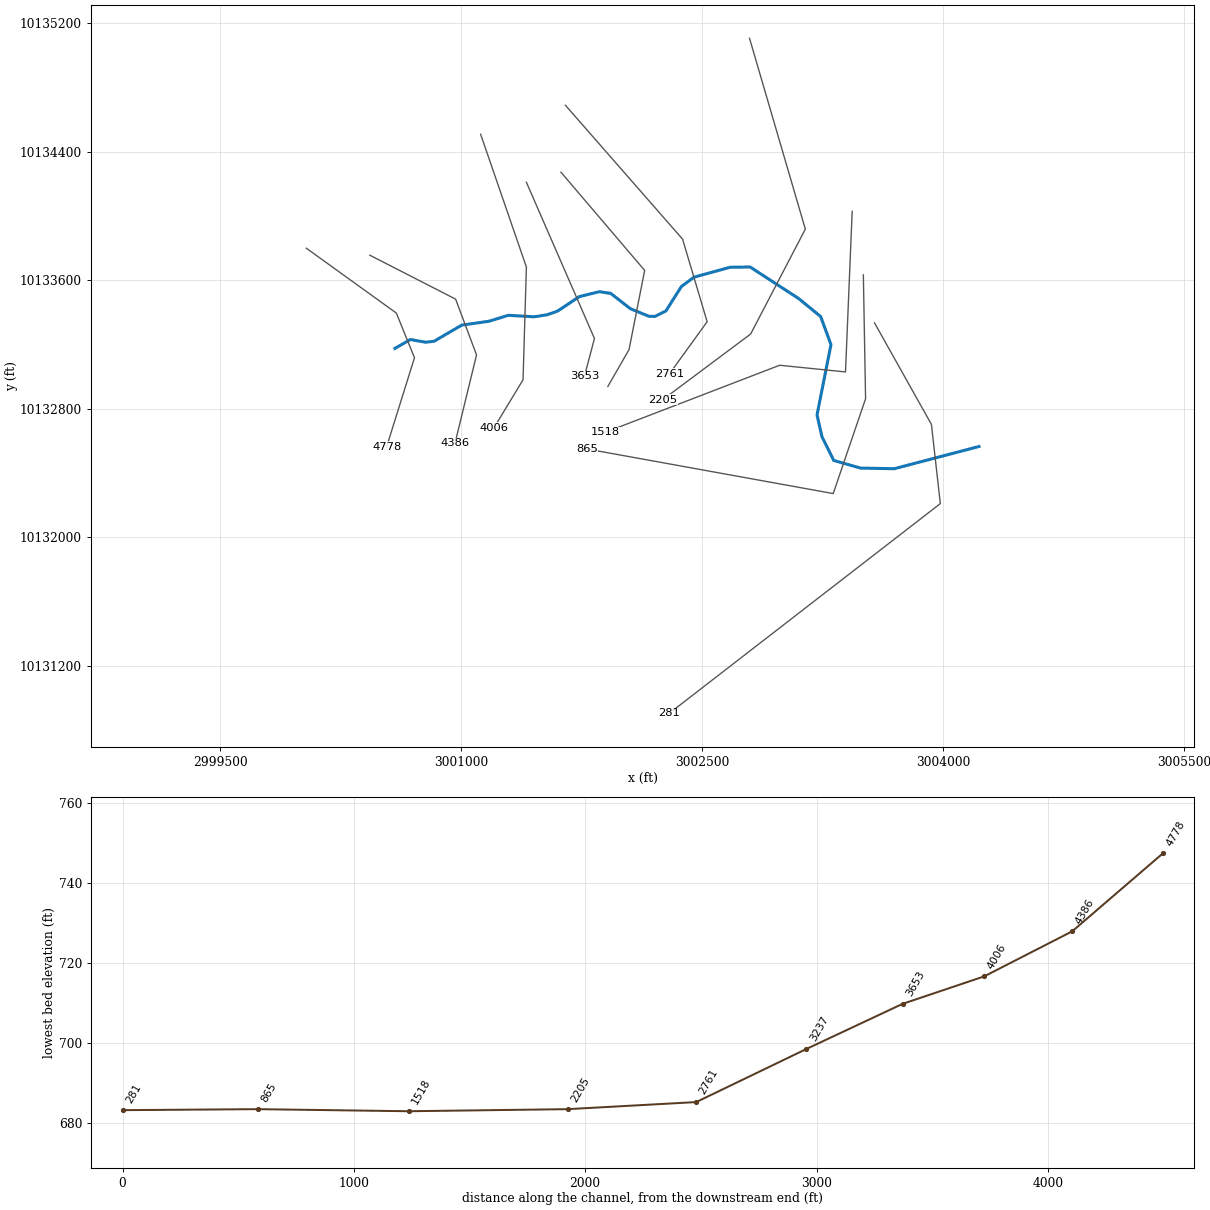
--- PEDERNALES TRIB 5.prj (project) ---

Proj Title=PEDERNALES TRIB 5 Base Level Engineering
Current Plan=p01
Default Exp/Contr=0.3,0.1
English Units
Geom File=g01
Flow File=f01
Plan File=p01
BEGIN DESCRIPTION:
PEDERNALES TRIB 5
END DESCRIPTION:

--- PEDERNALES TRIB 5.p01 (plan) ---

Plan Title=Multiple Run
Short Identifier=Multiple
Geom File=g01
Flow File=f01
Subcritical Flow
K Sum by GR= 0
Std Step Tol= 0.01
Critical Tol= 0.01
Num of Std Step Trials= 20
Max Error Tol= 0.3
Flow Tol Ratio= 0.001
Split Flow NTrial= 30
Split Flow Tol= 0.02
Split Flow Ratio= 0.02
Log Output Level= 0
Friction Slope Method= 1
Unsteady Friction Slope Method= 2
Unsteady Bridges Friction Slope Method= 1
Parabolic Critical Depth
Global Vel Dist=  1 , 1 , 1
Global Log Level= 0
CheckData=True
Encroach Param= -1, 0, 0, 0
BEGIN DESCRIPTION:
Multiple Run
END DESCRIPTION:

--- PEDERNALES TRIB 5.f01 (steady flow) ---

Flow Title=Multiple
Number of Profiles=7
Profile Names=10-year,25-year,50-year,1pct_min,100-year,1pct_plu,500-year
River Rch & RM= PEDERNALES TRIB ,Reach-1,4778
    1033    1524    1959    1843    2493    3372    4055
Boundary for River Rch & Prof#=PEDERNALES TRIB ,Reach-1,1
Up Type=0
Dn Type=3
Dn Slope=0.005
Boundary for River Rch & Prof#=PEDERNALES TRIB ,Reach-1,2
Up Type=0
Dn Type=3
Dn Slope=0.005
Boundary for River Rch & Prof#=PEDERNALES TRIB ,Reach-1,3
Up Type=0
Dn Type=3
Dn Slope=0.005
Boundary for River Rch & Prof#=PEDERNALES TRIB ,Reach-1,4
Up Type=0
Dn Type=3
Dn Slope=0.005
Boundary for River Rch & Prof#=PEDERNALES TRIB ,Reach-1,5
Up Type=0
Dn Type=3
Dn Slope=0.005
Boundary for River Rch & Prof#=PEDERNALES TRIB ,Reach-1,6
Up Type=0
Dn Type=3
Dn Slope=0.005
Boundary for River Rch & Prof#=PEDERNALES TRIB ,Reach-1,7
Up Type=0
Dn Type=3
Dn Slope=0.005

--- PEDERNALES TRIB 5.g01 (geometry) ---

Geom Title=Existing Conditions

River Reach=PEDERNALES TRIB ,Reach-1
Reach XY= 30
      3000588.12     10133177.00      3000684.29     10133232.15
      3000778.95     10133215.19      3000831.67     10133221.33
      3001004.19     10133321.97      3001173.20     10133345.73
      3001293.59     10133382.95      3001454.64     10133373.60
      3001537.27     10133386.62      3001600.89     10133409.25
      3001735.66     10133499.14      3001859.18     10133529.72
      3001931.26     10133519.24      3002053.52     10133424.04
      3002169.85     10133376.52      3002207.28     10133376.09
      3002274.93     10133410.37      3002371.01     10133562.19
      3002449.84     10133620.36      3002674.05     10133681.87
      3002798.47     10133683.73      3003101.39     10133486.84
      3003237.80     10133375.17      3003302.13     10133200.41
      3003215.16     10132762.16      3003246.50     10132625.60
      3003319.26     10132479.36      3003485.43     10132432.07
      3003695.35     10132427.95      3004223.01     10132566.24

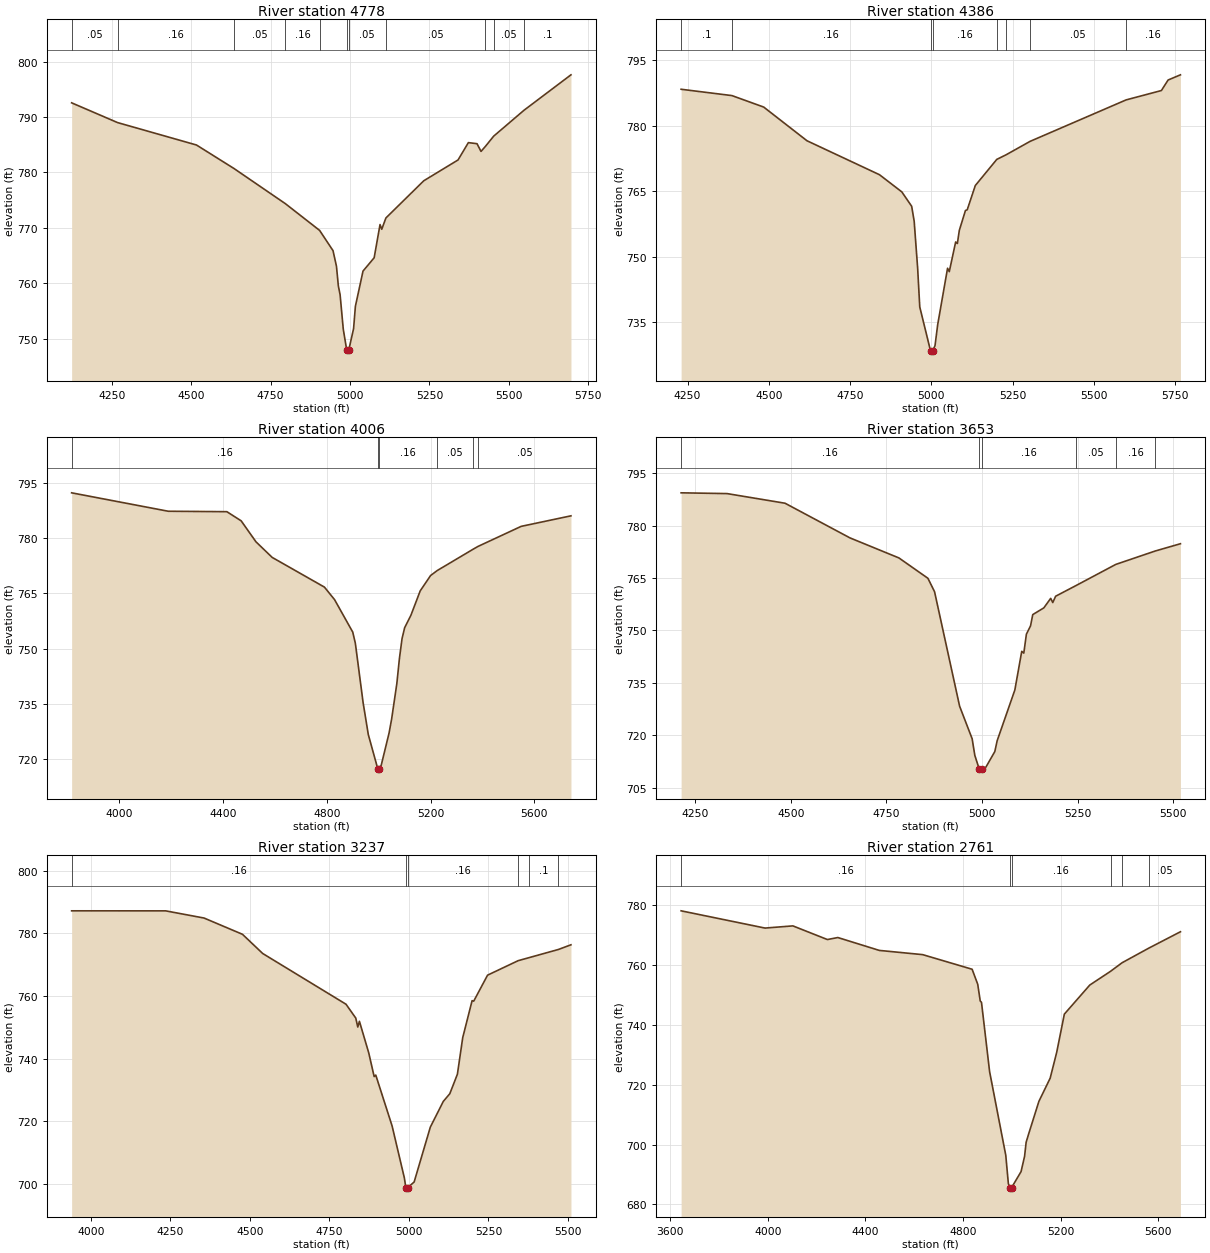
Type RM Length L Ch R = 1,4778,392,392,392
BEGIN DESCRIPTION:
PEDERNALES TRIB 5 10.0
END DESCRIPTION:
XS GIS Cut Line= 4
      3000037.01     10133800.34      3000596.94     10133396.67
      3000709.79     10133118.89      3000536.19     10132563.38
#Sta/Elev= 30
  4123.6  792.58  4268.3  789.01  4516.7  784.96  4634.1  780.74  4796.6  774.36
  4904.4  769.53  4946.6  765.87  4957.4  763.05  4963.4  759.48  4968.8  757.94
  4978.9  751.66  4989.9  747.86  4992.6  747.36  4995.9  747.86  5011.3  751.78
  5017.0  755.82  5041.0  762.18  5076.1  764.59  5094.6  770.59  5100.0  769.74
  5113.1  771.78  5232.3  778.50  5340.2  782.26  5372.7  785.39  5399.9  785.20
  5412.5  783.80  5426.2  784.70  5452.4  786.56  5547.9  791.24  5695.7  797.64
#Mann=11,-1,0
  4123.6    0.05       0  4268.3    0.16       0  4634.1    0.05       0
  4796.6    0.16       0  4904.4    0.05       0  4989.9    0.07       0
  4995.9    0.05       0  5113.1    0.05       0  5426.2     0.1       0
  5452.4    0.05       0  5547.9     0.1       0
Bank Sta=4989.9,4995.9
Exp/Cntr=0.3,0.1

Type RM Length L Ch R = 1,4386,380,380,380
BEGIN DESCRIPTION:
Mapping XS e179df10
END DESCRIPTION:
XS GIS Cut Line= 4
      3000431.99     10133756.92      3000965.87     10133483.47
      3001096.08     10133136.25      3000961.97     10132586.85
#Sta/Elev= 30
  4230.3  788.35  4386.6  786.90  4484.3  784.27  4617.6  776.54  4840.5  768.76
  4909.3  764.82  4939.6  761.52  4947.3  758.11  4958.0  747.32  4964.5  738.44
  4997.7  728.35  5000.5  727.85  5003.7  728.35  5011.4  729.55  5019.7  734.40
  5050.0  747.31  5055.3  746.53  5074.9  753.33  5080.2  752.99  5086.2  756.00
  5105.1  760.56  5110.5  760.71  5135.4  766.28  5201.5  772.27  5230.5  773.34
  5303.8  776.40  5599.3  785.91  5707.9  788.06  5728.5  790.47  5766.5  791.66
#Mann=8,-1,0
  4230.3     0.1       0  4386.6    0.16       0  4997.7    0.07       0
  5003.7    0.16       0  5201.5    0.05       0  5230.5    0.16       0
  5303.8    0.05       0  5599.3    0.16       0
Bank Sta=4997.7,5003.7
Exp/Cntr=0.3,0.1

Type RM Length L Ch R = 1,4006,353,353,353
BEGIN DESCRIPTION:
PEDERNALES TRIB 5 9.0
END DESCRIPTION:
XS GIS Cut Line= 4
      3001121.58     10134509.53      3001406.32     10133683.10
      3001385.49     10132981.71      3001204.91     10132683.06
#Sta/Elev= 30
  3816.4  792.43  4189.0  787.41  4414.8  787.29  4469.9  784.80  4527.1  779.07
  4589.5  774.83  4790.8  766.74  4829.9  763.33  4900.0  754.48  4910.0  751.47
  4940.0  735.25  4960.0  726.56  4997.0  717.09  4999.8  716.59  5003.0  717.09
  5010.0  718.25  5040.0  726.95  5050.0  730.82  5070.0  740.45  5080.0  747.31
  5090.1  752.71  5100.1  755.67  5124.3  759.07  5160.1  765.71  5200.1  769.89
  5225.7  771.25  5363.8  777.05  5382.5  777.81  5549.2  783.29  5741.2  786.16
#Mann=6,-1,0
  3816.4    0.16       0  4997.0    0.07       0  5003.0    0.16       0
  5225.7    0.05       0  5363.8    0.16       0  5382.5    0.05       0
Bank Sta=4997,5003
Exp/Cntr=0.3,0.1

Type RM Length L Ch R = 1,3653,416,416,416
BEGIN DESCRIPTION:
PEDERNALES TRIB 5 8.0
END DESCRIPTION:
XS GIS Cut Line= 3
      3001406.34     10134210.84      3001829.93     10133238.66
      3001767.43     10133002.54
#Sta/Elev= 30
  4213.7  789.38  4333.8  789.16  4485.3  786.40  4654.7  776.49  4782.8  770.74
  4858.5  764.92  4875.9  761.08  4941.4  728.29  4974.1  718.99  4981.1  714.23
  4992.9  710.21  4995.7  709.71  4998.9  710.21  5010.0  710.84  5033.4  715.32
  5039.5  718.41  5085.7  732.94  5103.7  744.00  5109.1  743.50  5115.9  748.92
  5126.8  751.32  5132.5  754.52  5161.4  756.44  5179.4  759.17  5184.8  757.97
  5192.3  759.78  5246.0  762.86  5349.5  768.89  5452.4  772.72  5518.4  774.81
#Mann=6,-1,0
  4213.7    0.16       0  4992.9    0.07       0  4998.9    0.16       0
  5246.0    0.05       0  5349.5    0.16       0  5452.4    0.05       0
Bank Sta=4992.9,4998.9
Exp/Cntr=0.3,0.1

Type RM Length L Ch R = 1,3237,476,476,476
BEGIN DESCRIPTION:
PEDERNALES TRIB 5 7.0
END DESCRIPTION:
XS GIS Cut Line= 4
      3001621.60     10134273.38      3002142.43     10133662.27
      3002045.21     10133169.21      3001913.38     10132940.25
#Sta/Elev= 30
  3939.6  787.16  4235.1  787.15  4355.9  784.86  4476.7  779.67  4540.3  773.55
  4802.2  757.37  4832.8  752.96  4839.2  750.10  4844.3  751.93  4873.6  741.87
  4890.6  734.31  4895.7  734.78  4947.0  718.57  4985.7  701.93  4990.2  698.91
  4993.0  698.41  4996.2  698.91  5016.3  700.68  5067.2  718.18  5108.0  726.39
  5128.4  728.83  5152.3  735.05  5169.1  746.75  5198.5  758.51  5203.6  758.35
  5247.1  766.64  5343.2  771.26  5376.6  772.20  5470.0  774.84  5509.3  776.33
#Mann=6,-1,0
  3939.6    0.16       0  4990.2    0.07       0  4996.2    0.16       0
  5343.2    0.05       0  5376.6     0.1       0  5470.0    0.05       0
Bank Sta=4990.2,4996.2
Exp/Cntr=0.3,0.1

Type RM Length L Ch R = 1,2761,556,556,556
BEGIN DESCRIPTION:
PEDERNALES TRIB 5 6.0
END DESCRIPTION:
XS GIS Cut Line= 4
      3001649.40     10134690.02      3002378.54     10133856.71
      3002531.32     10133342.82      3002296.05     10133017.59
#Sta/Elev= 30
  3645.5  778.07  3989.2  772.31  4103.1  773.04  4244.5  768.48  4287.3  769.15
  4457.1  764.85  4634.6  763.44  4837.2  758.56  4860.2  753.53  4870.4  747.97
  4875.6  747.50  4908.8  724.37  4975.0  696.44  4985.6  686.95  4992.8  685.63
  4995.6  685.13  4998.8  685.63  5037.6  690.98  5052.0  696.08  5058.4  700.78
  5068.9  703.62  5110.6  714.43  5156.8  722.18  5183.6  730.83  5214.9  743.58
  5319.0  753.28  5404.0  757.87  5451.3  760.73  5561.4  765.64  5690.3  771.08
#Mann=6,-1,0
  3645.5    0.16       0  4992.8    0.07       0  4998.8    0.16       0
  5404.0    0.05       0  5451.3    0.16       0  5561.4    0.05       0
Bank Sta=4992.8,4998.8
Exp/Cntr=0.3,0.1

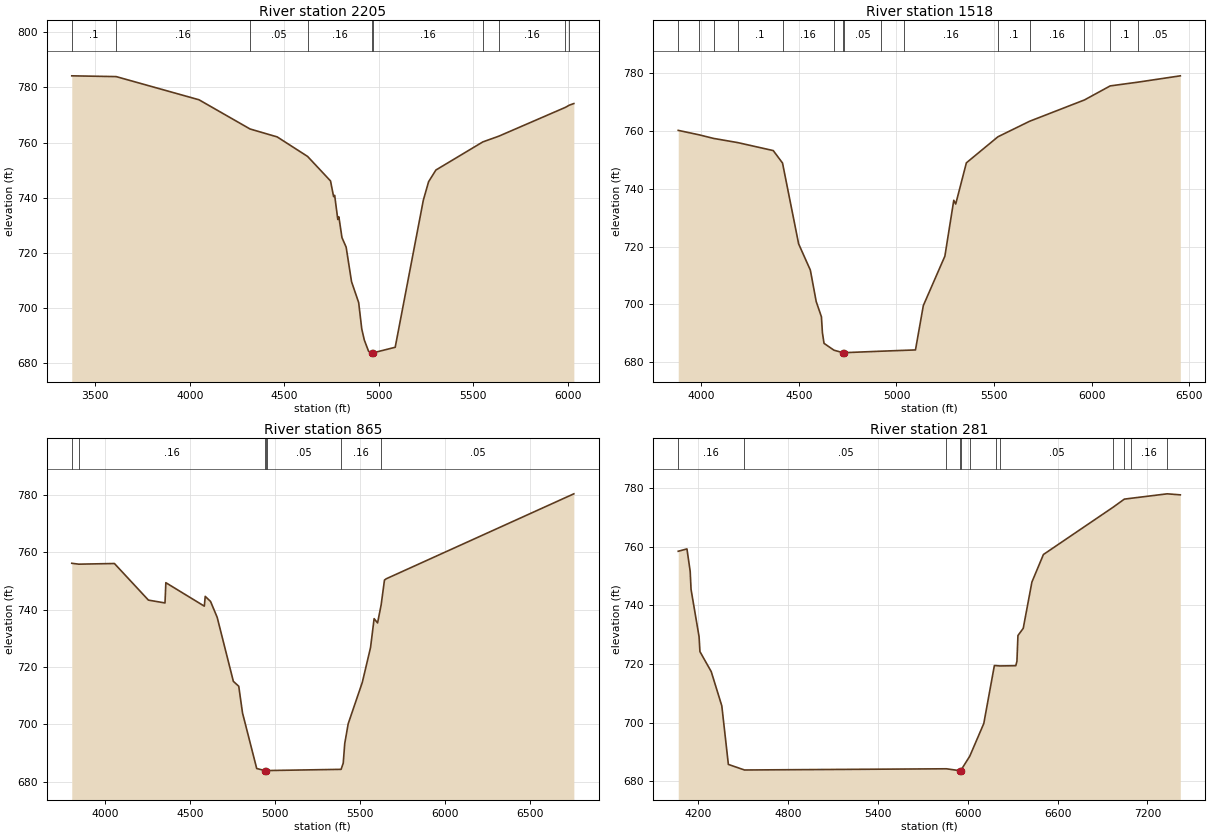
Type RM Length L Ch R = 1,2205,687,687,687
BEGIN DESCRIPTION:
PEDERNALES TRIB 5 5.0
END DESCRIPTION:
XS GIS Cut Line= 4
      3002795.20     10135106.73      3003142.43     10133919.21
      3002802.15     10133266.43      3002254.91     10132857.73
#Sta/Elev= 30
  3376.1  784.16  3611.0  783.88  4049.1  775.49  4319.2  764.91  4462.8  762.04
  4623.9  754.96  4745.1  746.09  4761.5  740.41  4767.1  740.86  4783.6  732.14
  4789.2  733.10  4805.7  725.57  4827.8  722.10  4856.3  709.61  4894.1  702.02
  4910.5  692.44  4924.0  688.45  4946.6  684.36  4966.1  683.86  4968.9  683.36
  4972.1  683.86  5087.3  685.84  5236.3  739.17  5264.0  745.81  5302.6  750.04
  5551.1  760.23  5635.6  762.30  5987.9  772.74  6008.3  773.53  6032.5  774.12
#Mann=10,-1,0
  3376.1     0.1       0  3611.0    0.16       0  4319.2    0.05       0
  4623.9    0.16       0  4966.1    0.07       0  4972.1    0.16       0
  5551.1     0.1       0  5635.6    0.16       0  5987.9    0.05       0
  6008.3     0.1       0
Bank Sta=4966.1,4972.1
Exp/Cntr=0.3,0.1

Type RM Length L Ch R = 1,1518,653,653,653
BEGIN DESCRIPTION:
PEDERNALES TRIB 5 4.0
END DESCRIPTION:
XS GIS Cut Line= 4
      3003434.10     10134030.34      3003392.43     10133030.32
      3002982.71     10133071.99      3001899.39     10132655.33
#Sta/Elev= 30
  3881.6  760.10  3989.9  758.54  4062.8  757.32  4187.0  755.87  4368.6  753.12
  4416.1  748.83  4498.7  720.92  4558.8  711.84  4588.8  700.98  4615.6  695.72
  4620.6  690.23  4628.9  686.56  4679.9  684.19  4725.9  683.34  4728.7  682.84
  4731.9  683.34  4920.7  683.85  5036.7  684.14  5097.6  684.29  5137.8  699.60
  5248.3  716.67  5293.9  735.96  5303.8  734.66  5358.5  748.89  5520.1  757.88
  5682.5  763.24  5963.9  770.61  6095.7  775.45  6240.5  776.77  6455.0  778.93
#Mann=15,-1,0
  3881.6    0.16       0  3989.9     0.1       0  4062.8    0.16       0
  4187.0     0.1       0  4416.1    0.16       0  4679.9    0.05       0
  4725.9    0.07       0  4731.9    0.05       0  4920.7     0.1       0
  5036.7    0.16       0  5520.1     0.1       0  5682.5    0.16       0
  5963.9    0.05       0  6095.7     0.1       0  6240.5    0.05       0
Bank Sta=4725.9,4731.9
Exp/Cntr=0.3,0.1

Type RM Length L Ch R = 1,865,584,584,584
BEGIN DESCRIPTION:
PEDERNALES TRIB 5 3.0
END DESCRIPTION:
XS GIS Cut Line= 4
      3003503.54     10133634.50      3003517.43     10132863.66
      3003316.04     10132273.38      3001782.42     10132550.96
#Sta/Elev= 30
  3804.6  756.19  3845.5  755.88  4055.4  756.11  4255.4  743.35  4353.0  742.35
  4358.0  749.42  4584.3  741.24  4589.6  744.65  4620.9  742.88  4660.0  737.33
  4755.1  715.02  4786.8  713.30  4808.9  704.00  4892.4  684.63  4942.3  683.86
  4945.1  683.36  4948.3  683.86  4953.0  683.91  5388.8  684.33  5401.4  686.50
  5410.2  693.33  5430.5  700.22  5513.5  714.66  5561.9  726.78  5583.0  736.88
  5603.3  735.39  5624.3  741.66  5643.9  750.33  5654.1  750.78  6757.8  780.41
#Mann=7,-1,0
  3804.6     0.1       0  3845.5    0.16       0  4942.3   0.033       0
  4948.3    0.16       0  4953.0    0.05       0  5388.8    0.16       0
  5624.3    0.05       0
Bank Sta=4942.3,4948.3
Exp/Cntr=0.3,0.1

Type RM Length L Ch R = 1,281,0,0,0
BEGIN DESCRIPTION:
PEDERNALES TRIB 5 1.0
END DESCRIPTION:
XS GIS Cut Line= 4
      3003572.99     10133335.88      3003927.15     10132703.93
      3003982.71     10132210.88      3002295.18     10130905.30
#Sta/Elev= 30
  4065.2  758.49  4123.4  759.29  4145.1  751.61  4150.8  745.49  4204.4  729.33
  4210.2  724.24  4285.5  717.43  4356.3  705.74  4400.1  685.74  4507.8  683.84
  5856.1  684.25  5946.0  683.61  5948.7  683.11  5952.0  683.61  6012.7  688.54
  6106.5  699.70  6177.2  719.47  6187.5  719.47  6213.2  719.35  6320.2  719.43
  6327.9  720.94  6334.7  729.74  6370.0  732.18  6428.0  747.99  6504.9  757.38
  6969.4  773.48  7045.4  776.28  7090.3  776.57  7332.0  778.09  7419.4  777.74
#Mann=12,-1,0
  4065.2    0.16       0  4507.8    0.05       0  5856.1     0.1       0
  5946.0   0.033       0  5952.0     0.1       0  6012.7    0.05       0
  6187.5     0.1       0  6213.2    0.05       0  6969.4     0.1       0
  7045.4    0.05       0  7090.3    0.16       0  7332.0    0.05       0
Bank Sta=5946,5952
Exp/Cntr=0.3,0.1

Chan Stop Cuts=-1