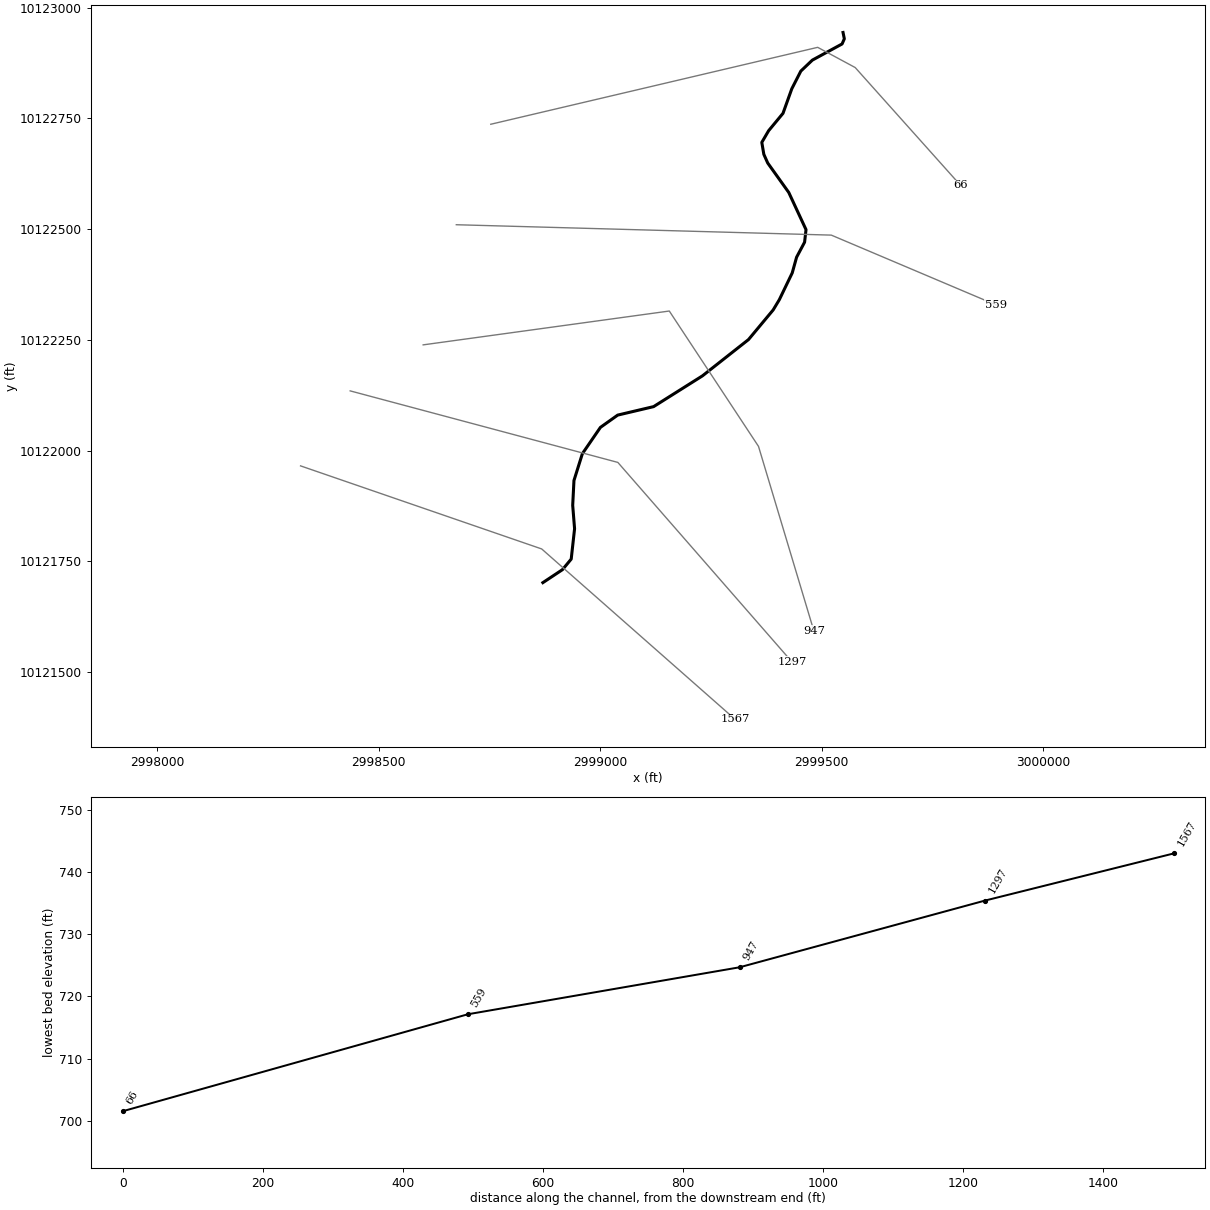
--- PERDANALES TRIB 4 1.prj (project) ---

Proj Title=PERDANALES TRIB 4 1 Base Level Engineering
Current Plan=p01
Default Exp/Contr=0.3,0.1
English Units
Geom File=g01
Flow File=f01
Plan File=p01
Y Axis Title=Elevation
X Axis Title(PF)=Main Channel Distance
X Axis Title(XS)=Station
BEGIN DESCRIPTION:
PERDANALES TRIB 4 1
END DESCRIPTION:
DSS Export Rating Curves= 0
DSS Export Rating Curve Sorted= 0
DSS Export Volume Flow Curves= 0
DXF OffsetX= 0
DXF OffsetY= 0
DXF ScaleX= 1
DXF ScaleY= 10

--- PERDANALES TRIB 4 1.p01 (plan) ---

Plan Title=Multiple Run
Short Identifier=Multiple
Geom File=g01
Flow File=f01
Subcritical Flow
K Sum by GR= 0
Std Step Tol= 0.01
Critical Tol= 0.01
Num of Std Step Trials= 20
Max Error Tol= 0.3
Flow Tol Ratio= 0.001
Split Flow NTrial= 30
Split Flow Tol= 0.02
Split Flow Ratio= 0.02
Log Output Level= 0
Friction Slope Method= 1
Unsteady Friction Slope Method= 2
Unsteady Bridges Friction Slope Method= 1
Parabolic Critical Depth
Global Vel Dist=  1 , 1 , 1
Global Log Level= 0
CheckData=True
Encroach Param= -1, 0, 0, 0
BEGIN DESCRIPTION:
Multiple Run
END DESCRIPTION:

--- PERDANALES TRIB 4 1.f01 (steady flow) ---

Flow Title=Multiple
Number of Profiles=7
Profile Names=10-year,25-year,50-year,1pct_min,100-year,1pct_plu,500-year
River Rch & RM= PERDANALES TRIB ,Reach-1,1567
     788    1137    1439    1335    1806    2442    2850
Boundary for River Rch & Prof#=PERDANALES TRIB ,Reach-1,1
Up Type=0
Dn Type=3
Dn Slope=0.005
Boundary for River Rch & Prof#=PERDANALES TRIB ,Reach-1,2
Up Type=0
Dn Type=3
Dn Slope=0.005
Boundary for River Rch & Prof#=PERDANALES TRIB ,Reach-1,3
Up Type=0
Dn Type=3
Dn Slope=0.005
Boundary for River Rch & Prof#=PERDANALES TRIB ,Reach-1,4
Up Type=0
Dn Type=3
Dn Slope=0.005
Boundary for River Rch & Prof#=PERDANALES TRIB ,Reach-1,5
Up Type=0
Dn Type=3
Dn Slope=0.005
Boundary for River Rch & Prof#=PERDANALES TRIB ,Reach-1,6
Up Type=0
Dn Type=3
Dn Slope=0.005
Boundary for River Rch & Prof#=PERDANALES TRIB ,Reach-1,7
Up Type=0
Dn Type=3
Dn Slope=0.005

--- PERDANALES TRIB 4 1.g01 (geometry) ---

Geom Title=Existing Conditions

River Reach=PERDANALES TRIB ,Reach-1
Reach XY= 30
      2998870.98     10121701.98      2998915.16     10121731.26
      2998934.95     10121755.15      2998942.55     10121823.64
      2998938.31     10121876.55      2998941.18     10121932.58
      2998960.15     10121993.08      2999000.88     10122052.41
      2999039.85     10122080.13      2999120.89     10122099.25
      2999231.13     10122168.68      2999335.08     10122250.59
      2999390.76     10122317.48      2999404.66     10122340.59
      2999433.79     10122401.02      2999443.65     10122436.51
      2999461.70     10122470.38      2999464.93     10122498.73
      2999425.95     10122582.67      2999378.49     10122649.08
      2999369.71     10122668.74      2999365.14     10122695.71
      2999380.54     10122722.05      2999412.96     10122761.23
      2999432.83     10122816.67      2999453.25     10122856.63
      2999479.27     10122881.37      2999546.31     10122917.81
      2999551.41     10122929.45      2999548.47     10122943.73

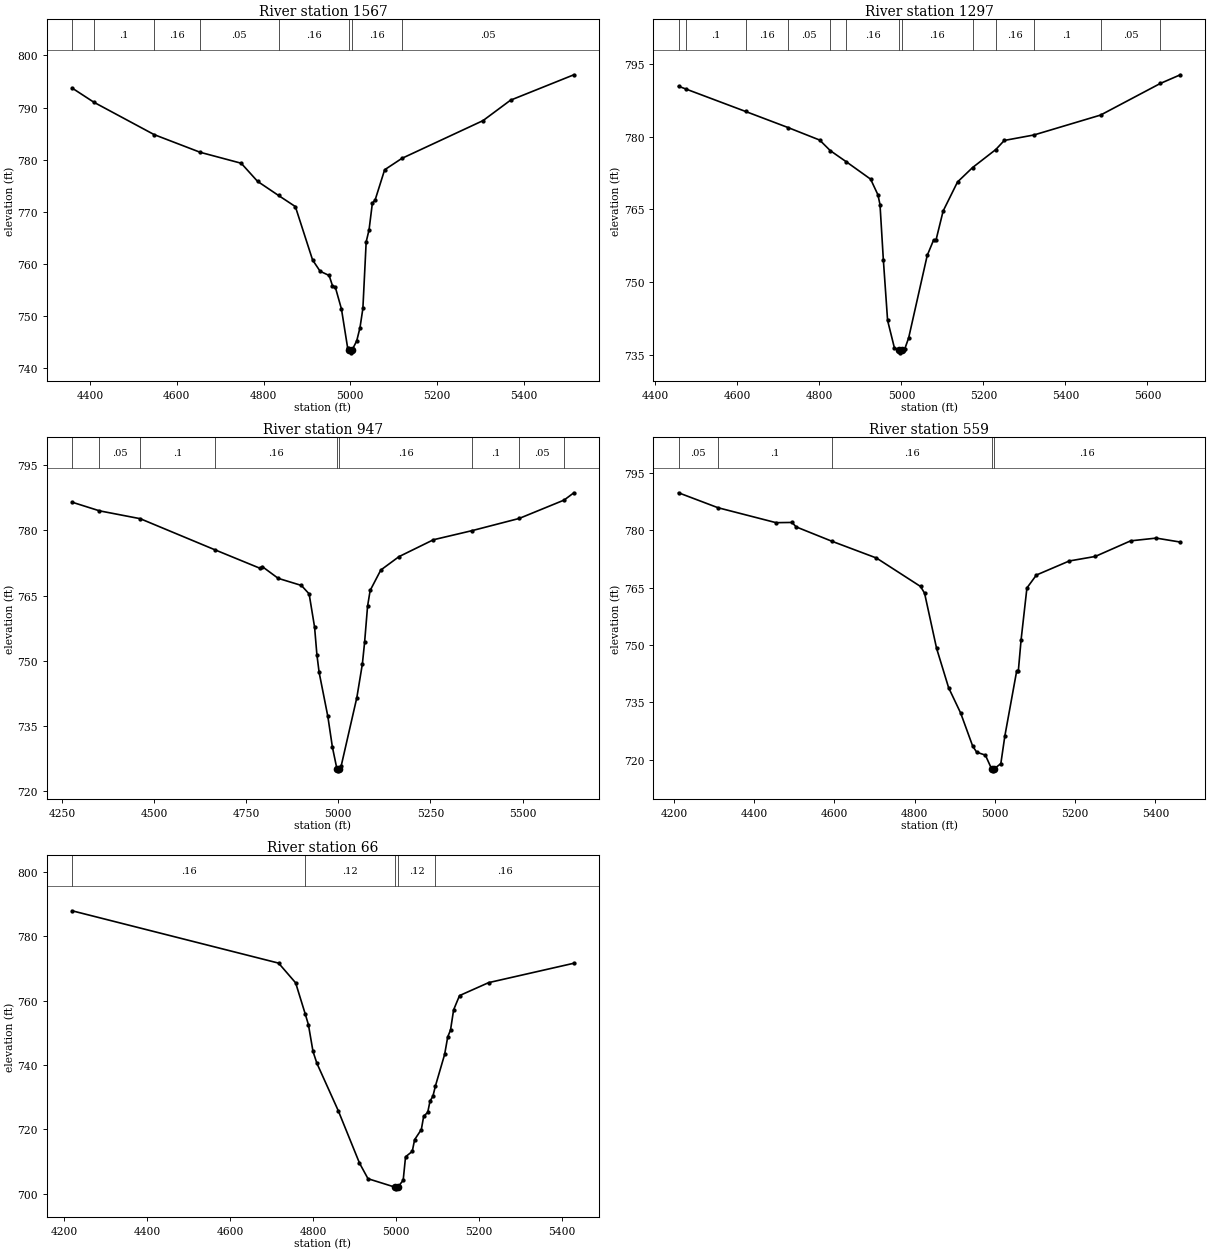
Type RM Length L Ch R = 1,1567,270,270,270
BEGIN DESCRIPTION:
PERDANALES TRIB 4 1 3.0
END DESCRIPTION:
XS GIS Cut Line= 3
      2998324.06     10121965.54      2998868.36     10121778.03
      2999304.63     10121393.70
#Sta/Elev= 30
  4358.4  793.76  4409.0  791.02  4547.9  784.82  4653.8  781.44  4748.4  779.34
  4786.1  775.87  4834.5  773.16  4873.3  771.03  4913.0  760.80  4930.4  758.63
  4951.2  757.82  4958.8  755.88  4965.4  755.59  4979.6  751.39  4993.9  743.91
  4997.9  743.49  5000.6  742.99  5003.9  743.49  5014.8  745.29  5022.3  747.80
  5029.0  751.50  5036.6  764.28  5043.2  766.55  5050.8  771.64  5057.4  772.34
  5079.2  778.09  5119.1  780.28  5306.0  787.51  5369.5  791.43  5515.5  796.30
#Mann=8,-1,0
  4358.4    0.16       0  4409.0     0.1       0  4547.9    0.16       0
  4653.8    0.05       0  4834.5    0.16       0  4997.9    0.07       0
  5003.9    0.16       0  5119.1    0.05       0
Bank Sta=4997.9,5003.9
Exp/Cntr=0.3,0.1

Type RM Length L Ch R = 1,1297,350,350,350
BEGIN DESCRIPTION:
Mapping XS f9cb1877
END DESCRIPTION:
XS GIS Cut Line= 3
      2998436.07     10122134.80      2999040.23     10121973.35
      2999433.49     10121522.79
#Sta/Elev= 30
  4456.7  790.37  4474.5  789.80  4620.1  785.17  4723.4  781.86  4800.8  779.27
  4826.8  777.08  4865.6  774.80  4925.0  771.21  4942.8  767.99  4947.9  765.96
  4956.0  754.64  4966.4  742.08  4982.8  736.49  4994.4  735.90  4997.2  735.40
  5000.4  735.90  5007.8  736.10  5017.7  738.46  5063.0  755.48  5078.6  758.67
  5084.5  758.67  5101.8  764.64  5136.9  770.63  5173.7  773.61  5230.1  777.31
  5250.9  779.19  5323.3  780.32  5485.6  784.42  5631.3  790.94  5680.1  792.73
#Mann=13,-1,0
  4456.7    0.16       0  4474.5     0.1       0  4620.1    0.16       0
  4723.4    0.05       0  4826.8     0.1       0  4865.6    0.16       0
  4994.4    0.07       0  5000.4    0.16       0  5173.7     0.1       0
  5230.1    0.16       0  5323.3     0.1       0  5485.6    0.05       0
  5631.3     0.1       0
Bank Sta=4994.4,5000.4
Exp/Cntr=0.3,0.1

Type RM Length L Ch R = 1,947,388,388,388
BEGIN DESCRIPTION:
PERDANALES TRIB 4 1 2.0
END DESCRIPTION:
XS GIS Cut Line= 4
      2998600.79     10122238.66      2999156.32     10122315.04
      2999357.71     10122009.49      2999482.70     10121592.84
#Sta/Elev= 30
  4277.4  786.46  4351.7  784.47  4462.4  782.66  4664.5  775.53  4788.3  771.23
  4793.4  771.66  4836.7  768.95  4899.6  767.32  4920.7  765.37  4935.5  757.73
  4941.8  751.39  4947.8  747.34  4971.5  737.19  4983.9  730.12  4996.0  725.19
  4998.7  724.69  5002.0  725.19  5007.4  725.70  5050.2  741.54  5065.2  749.27
  5071.2  754.20  5079.3  762.55  5086.3  766.16  5115.2  770.86  5164.6  773.94
  5258.0  777.82  5363.6  779.93  5490.8  782.72  5612.6  786.94  5639.1  788.62
#Mann=9,-1,0
  4277.4     0.1       0  4351.7    0.05       0  4462.4     0.1       0
  4664.5    0.16       0  4996.0    0.07       0  5002.0    0.16       0
  5363.6     0.1       0  5490.8    0.05       0  5612.6     0.1       0
Bank Sta=4996,5002
Exp/Cntr=0.3,0.1

Type RM Length L Ch R = 1,559,493,493,493
BEGIN DESCRIPTION:
Mapping XS 8785408d
END DESCRIPTION:
XS GIS Cut Line= 3
      2998675.61     10122509.81      2999522.00     10122486.37
      2999893.80     10122328.87
#Sta/Elev= 30
  4211.6  789.79  4309.8  785.89  4454.6  781.98  4494.6  782.04  4504.6  780.88
  4593.9  777.12  4704.7  772.75  4814.7  765.31  4824.7  763.57  4854.7  749.14
  4884.7  738.85  4914.7  732.23  4944.7  723.58  4954.7  722.01  4976.3  721.24
  4991.8  717.64  4994.5  717.14  4997.8  717.64  5014.8  719.03  5024.8  726.24
  5054.1  743.12  5058.3  743.12  5065.3  751.40  5079.8  764.92  5103.4  768.30
  5185.3  771.97  5250.0  773.15  5338.3  777.23  5402.0  777.95  5462.1  776.91
#Mann=5,-1,0
  4211.6    0.05       0  4309.8     0.1       0  4593.9    0.16       0
  4991.8    0.07       0  4997.8    0.16       0
Bank Sta=4991.8,4997.8
Exp/Cntr=0.3,0.1

Type RM Length L Ch R = 1,66,0,0,0
BEGIN DESCRIPTION:
PERDANALES TRIB 4 1 1.0
END DESCRIPTION:
XS GIS Cut Line= 4
      2998753.42     10122736.59      2999491.25     10122910.20
      2999575.89     10122864.62      2999813.60     10122598.82
#Sta/Elev= 30
  4218.6  787.99  4716.9  771.72  4758.0  765.59  4781.1  755.94  4788.8  752.61
  4799.9  744.27  4809.3  740.58  4860.7  725.89  4912.1  709.55  4932.6  704.70
  4998.3  702.05  5001.0  701.55  5004.3  702.05  5017.5  704.21  5023.2  711.50
  5039.4  713.20  5045.1  716.84  5061.3  719.99  5067.0  724.14  5076.7  725.32
  5082.3  728.86  5089.1  730.28  5095.3  733.54  5117.5  743.34  5125.0  748.80
  5131.7  750.90  5139.2  757.20  5153.4  761.62  5223.6  765.65  5429.3  771.68
#Mann=5,-1,0
  4218.6    0.16       0  4781.1    0.12       0  4998.3    0.07       0
  5004.3    0.12       0  5095.3    0.16       0
Bank Sta=4998.3,5004.3
Exp/Cntr=0.3,0.1

Chan Stop Cuts=-1