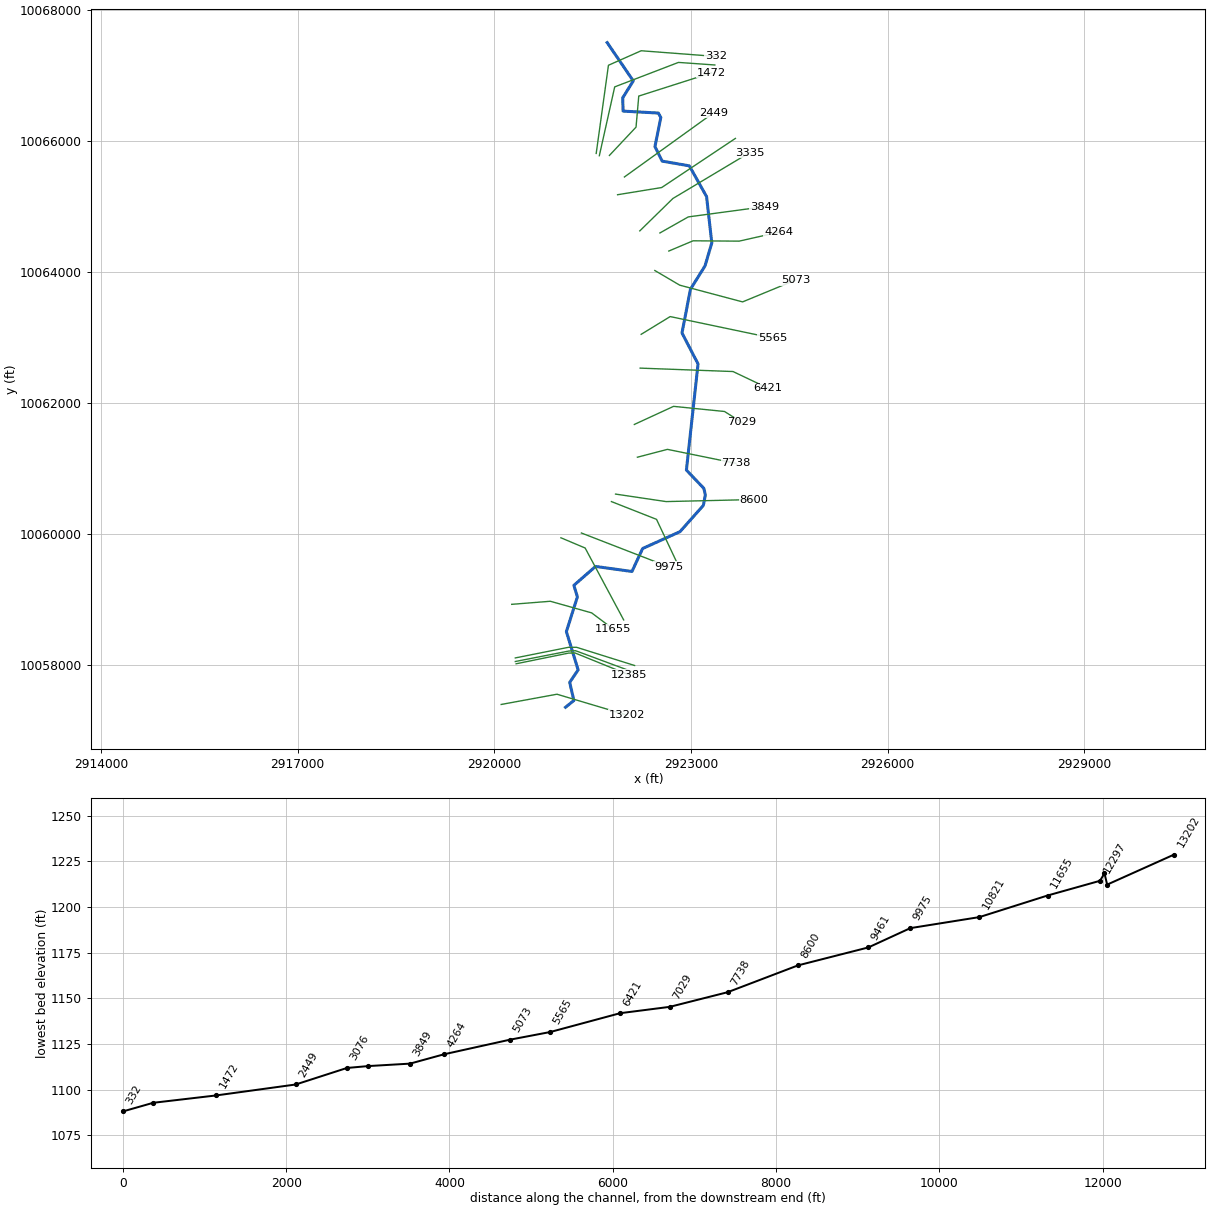
--- ROUGH HOLLOW.prj (project) ---

Proj Title=ROUGH HOLLOW Base Level Engineering
Current Plan=p01
Default Exp/Contr=0.3,0.1
English Units
Geom File=g01
Flow File=f01
Plan File=p01
BEGIN DESCRIPTION:
ROUGH HOLLOW
END DESCRIPTION:

--- ROUGH HOLLOW.p01 (plan) ---

Plan Title=Multiple Run
Short Identifier=Multiple
Geom File=g01
Flow File=f01
Subcritical Flow
K Sum by GR= 0
Std Step Tol= 0.01
Critical Tol= 0.01
Num of Std Step Trials= 20
Max Error Tol= 0.3
Flow Tol Ratio= 0.001
Split Flow NTrial= 30
Split Flow Tol= 0.02
Split Flow Ratio= 0.02
Log Output Level= 0
Friction Slope Method= 1
Unsteady Friction Slope Method= 2
Unsteady Bridges Friction Slope Method= 1
Parabolic Critical Depth
Global Vel Dist=  1 , 1 , 1
Global Log Level= 0
CheckData=True
Encroach Param= -1, 0, 0, 0
BEGIN DESCRIPTION:
Multiple Run
END DESCRIPTION:

--- ROUGH HOLLOW.f01 (steady flow) ---

Flow Title=Multiple
Number of Profiles=7
Profile Names=10-year,25-year,50-year,1pct_min,100-year,1pct_plu,500-year
River Rch & RM= ROUGH HOLLOW,Reach-1,13202
    1020    1496    1915    1797    2430    3286    3922
River Rch & RM= ROUGH HOLLOW,Reach-1,12297
    1660    2494    3244    3086    4173    5644    6933
River Rch & RM= ROUGH HOLLOW,Reach-1,8600
    1953    2940    3829    3642    4925    6660    8182
Boundary for River Rch & Prof#=ROUGH HOLLOW,Reach-1,1
Up Type=0
Dn Type=3
Dn Slope=0.005
Boundary for River Rch & Prof#=ROUGH HOLLOW,Reach-1,2
Up Type=0
Dn Type=3
Dn Slope=0.005
Boundary for River Rch & Prof#=ROUGH HOLLOW,Reach-1,3
Up Type=0
Dn Type=3
Dn Slope=0.005
Boundary for River Rch & Prof#=ROUGH HOLLOW,Reach-1,4
Up Type=0
Dn Type=3
Dn Slope=0.005
Boundary for River Rch & Prof#=ROUGH HOLLOW,Reach-1,5
Up Type=0
Dn Type=3
Dn Slope=0.005
Boundary for River Rch & Prof#=ROUGH HOLLOW,Reach-1,6
Up Type=0
Dn Type=3
Dn Slope=0.005
Boundary for River Rch & Prof#=ROUGH HOLLOW,Reach-1,7
Up Type=0
Dn Type=3
Dn Slope=0.005

--- ROUGH HOLLOW.g01 (geometry) ---

Geom Title=Existing Conditions

River Reach=ROUGH HOLLOW,Reach-1
Reach XY= 30
      2921085.91     10057354.53      2921213.44     10057457.73
      2921149.54     10057734.15      2921278.28     10057925.48
      2921099.07     10058508.90      2921267.12     10059039.63
      2921213.18     10059214.55      2921543.60     10059503.43
      2922099.14     10059426.50      2922262.08     10059776.91
      2922831.90     10060034.03      2923187.75     10060434.63
      2923218.53     10060594.02      2923195.05     10060695.24
      2922929.53     10060973.51      2923106.99     10062593.40
      2922862.27     10063065.34      2922990.90     10063732.73
      2923213.31     10064089.25      2923316.62     10064439.30
      2923237.06     10065146.78      2922974.24     10065615.60
      2922559.26     10065687.93      2922449.75     10065910.72
      2922539.29     10066353.34      2922502.10     10066421.22
      2921963.88     10066451.01      2921958.15     10066653.76
      2922119.15     10066912.27      2921721.59     10067495.61

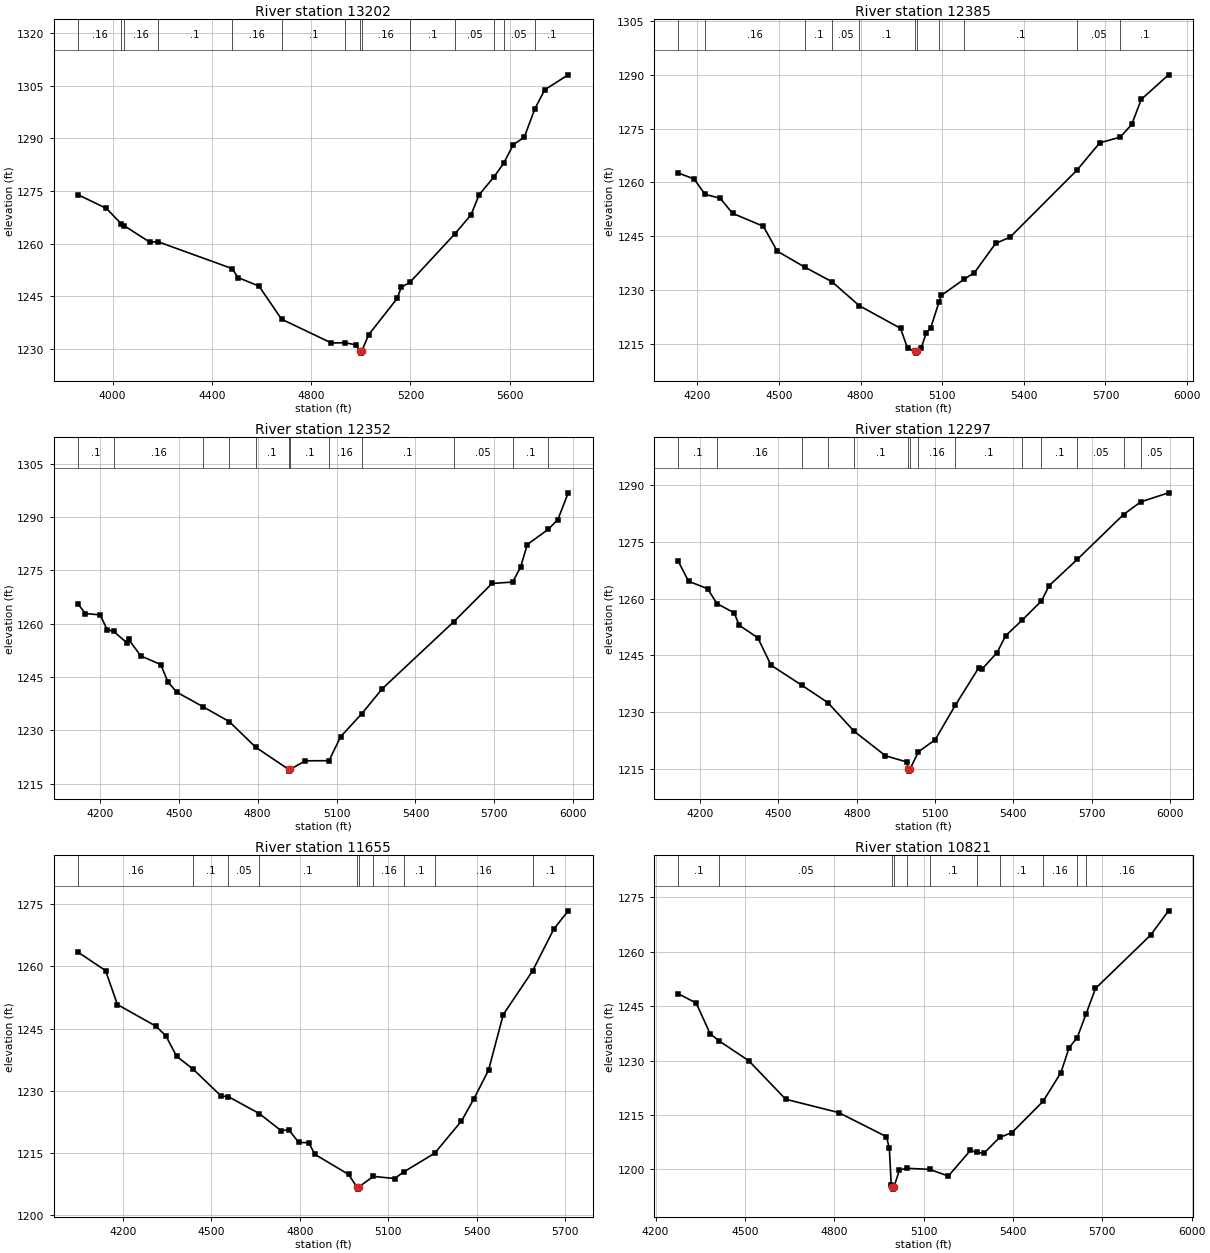
Type RM Length L Ch R = 1,13202,817,817,817
BEGIN DESCRIPTION:
ROUGH HOLLOW 27.0
END DESCRIPTION:
XS GIS Cut Line= 3
      2920104.82     10057397.37      2920955.55     10057553.63
      2922018.89     10057236.79
#Sta/Elev= 30
  3861.2 1273.93  3975.6 1270.02  4036.2 1265.56  4046.9 1265.10  4150.1 1260.40
  4183.1 1260.52  4481.7 1252.86  4505.4 1250.30  4590.1 1247.86  4680.8 1238.43
  4881.9 1231.63  4937.5 1231.71  4979.6 1231.09  4997.5 1229.24  5000.2 1228.74
  5003.5 1229.24  5031.8 1233.99  5146.6 1244.35  5162.9 1247.48  5200.0 1249.09
  5378.6 1262.74  5443.8 1268.17  5477.0 1273.95  5537.6 1279.11  5574.9 1282.86
  5614.9 1288.26  5658.5 1290.34  5701.1 1298.43  5741.3 1303.90  5835.7 1308.14
#Mann=14,-1,0
  3861.2    0.16       0  4036.2     0.1       0  4046.9    0.16       0
  4183.1     0.1       0  4481.7    0.16       0  4680.8     0.1       0
  4937.5    0.16       0  4997.5    0.07       0  5003.5    0.16       0
  5200.0     0.1       0  5378.6    0.05       0  5537.6     0.1       0
  5574.9    0.05       0  5701.1     0.1       0
Bank Sta=4997.5,5003.5
Exp/Cntr=0.3,0.1

Type RM Length L Ch R = 1,12385,33,33,33
BEGIN DESCRIPTION:
Mapping XS 06483bf9
END DESCRIPTION:
XS GIS Cut Line= 4
      2920332.28     10058018.03      2921132.64     10058181.23
      2921231.60     10058182.97      2922052.82     10057849.61
#Sta/Elev= 30
  4129.8 1262.60  4187.8 1260.95  4227.6 1256.68  4283.8 1255.54  4329.2 1251.35
  4442.3 1247.74  4493.3 1240.80  4595.0 1236.31  4694.9 1232.24  4794.7 1225.58
  4946.6 1219.25  4972.5 1213.67  4999.5 1212.82  5002.2 1212.32  5005.5 1212.82
  5022.5 1213.70  5041.5 1218.04  5057.6 1219.38  5088.8 1226.71  5096.2 1228.41
  5181.2 1232.99  5218.3 1234.78  5296.0 1242.93  5349.6 1244.71  5595.4 1263.42
  5679.0 1271.02  5754.5 1272.63  5796.8 1276.20  5831.7 1283.17  5931.9 1290.02
#Mann=11,-1,0
  4129.8     0.1       0  4227.6    0.16       0  4595.0     0.1       0
  4694.9    0.05       0  4794.7     0.1       0  4999.5    0.07       0
  5005.5     0.1       0  5088.8    0.16       0  5181.2     0.1       0
  5595.4    0.05       0  5754.5     0.1       0
Bank Sta=4999.5,5005.5
Exp/Cntr=0.3,0.1

Type RM Length L Ch R = 1,12352,55,55,55
BEGIN DESCRIPTION:
ROUGH HOLLOW 26.0
END DESCRIPTION:
XS GIS Cut Line= 4
      2920320.10     10058052.75      2921136.11     10058212.48
      2921238.54     10058217.69      2922110.08     10057894.77
#Sta/Elev= 30
  4117.3 1265.52  4144.8 1262.84  4201.4 1262.45  4227.7 1258.34  4252.7 1257.81
  4304.4 1254.50  4309.5 1255.56  4355.9 1250.90  4431.5 1248.49  4458.9 1243.62
  4492.7 1240.70  4592.8 1236.59  4692.5 1232.41  4792.2 1225.24  4917.6 1218.99
  4920.4 1218.49  4923.6 1218.99  4981.2 1221.39  5071.4 1221.43  5115.3 1228.15
  5195.1 1234.59  5274.3 1241.71  5545.8 1260.55  5691.1 1271.30  5769.6 1271.69
  5799.9 1275.95  5825.0 1282.25  5904.1 1286.49  5941.2 1289.25  5980.8 1296.80
#Mann=12,-1,0
  4117.3     0.1       0  4252.7    0.16       0  4592.8     0.1       0
  4692.5    0.05       0  4792.2     0.1       0  4917.6    0.07       0
  4923.6     0.1       0  5071.4    0.16       0  5195.1     0.1       0
  5545.8    0.05       0  5769.6     0.1       0  5904.1    0.05       0
Bank Sta=4917.6,4923.6
Exp/Cntr=0.3,0.1

Type RM Length L Ch R = 1,12297,642,642,642
BEGIN DESCRIPTION:
ROUGH HOLLOW 25.0
END DESCRIPTION:
XS GIS Cut Line= 4
      2920320.11     10058107.44      2921132.64     10058269.77
      2921254.17     10058269.77      2922139.60     10057991.99
#Sta/Elev= 30
  4116.6 1269.80  4155.7 1264.56  4228.7 1262.58  4264.8 1258.65  4330.8 1256.21
  4349.5 1252.95  4420.9 1249.64  4471.8 1242.38  4590.0 1237.08  4689.8 1232.49
  4789.5 1224.98  4910.3 1218.46  4991.0 1216.85  4998.0 1214.91  5000.8 1214.41
  5004.0 1214.91  5036.7 1219.53  5100.5 1222.69  5177.4 1231.75  5267.9 1241.75
  5280.8 1241.39  5338.0 1245.73  5370.4 1250.14  5434.8 1254.35  5507.8 1259.36
  5537.7 1263.42  5645.6 1270.36  5822.2 1282.17  5888.2 1285.52  5994.7 1287.91
#Mann=14,-1,0
  4116.6     0.1       0  4264.8    0.16       0  4590.0     0.1       0
  4689.8    0.05       0  4789.5     0.1       0  4998.0    0.07       0
  5004.0     0.1       0  5036.7    0.16       0  5177.4     0.1       0
  5434.8    0.05       0  5507.8     0.1       0  5645.6    0.05       0
  5822.2     0.1       0  5888.2    0.05       0
Bank Sta=4998,5004
Exp/Cntr=0.3,0.1

Type RM Length L Ch R = 1,11655,834,834,834
BEGIN DESCRIPTION:
ROUGH HOLLOW 23.0
END DESCRIPTION:
XS GIS Cut Line= 4
      2920265.47     10058925.16      2920853.99     10058972.03
      2921484.20     10058794.95      2921817.56     10058544.92
#Sta/Elev= 30
  4048.6 1263.41  4141.9 1258.97  4182.0 1250.80  4312.4 1245.59  4346.5 1243.25
  4382.6 1238.34  4437.8 1235.30  4533.1 1228.80  4558.4 1228.61  4662.9 1224.55
  4737.1 1220.42  4762.6 1220.68  4796.6 1217.60  4830.6 1217.53  4851.4 1214.72
  4965.6 1209.90  4993.8 1206.85  4996.5 1206.35  4999.8 1206.85  5049.8 1209.42
  5121.4 1208.90  5153.5 1210.53  5257.3 1214.98  5348.3 1222.74  5390.0 1228.05
  5440.0 1234.97  5490.0 1248.38  5589.4 1258.91  5661.4 1268.98  5710.3 1273.37
#Mann=10,-1,0
  4048.6    0.16       0  4437.8     0.1       0  4558.4    0.05       0
  4662.9     0.1       0  4993.8    0.07       0  4999.8     0.1       0
  5049.8    0.16       0  5153.5     0.1       0  5257.3    0.16       0
  5589.4     0.1       0
Bank Sta=4993.8,4999.8
Exp/Cntr=0.3,0.1

Type RM Length L Ch R = 1,10821,846,846,846
BEGIN DESCRIPTION:
ROUGH HOLLOW 22.0
END DESCRIPTION:
XS GIS Cut Line= 3
      2921015.47     10059940.77      2921385.24     10059784.53
      2921972.76     10058687.48
#Sta/Elev= 30
  4276.4 1248.42  4336.2 1245.86  4383.6 1237.35  4413.5 1235.40  4513.0 1229.94
  4636.9 1219.32  4814.9 1215.64  4975.0 1209.00  4985.0 1205.79  4991.2 1195.78
  4993.9 1195.02  4996.7 1194.52  4999.9 1195.02  5019.0 1199.80  5042.7 1200.27
  5120.1 1199.97  5183.0 1198.13  5257.3 1205.21  5278.6 1204.64  5302.6 1204.44
  5355.1 1208.77  5396.7 1210.13  5501.4 1218.77  5560.8 1226.64  5588.4 1233.51
  5615.9 1236.35  5645.4 1242.83  5677.0 1249.88  5862.2 1264.61  5922.3 1271.30
#Mann=11,-1,0
  4276.4     0.1       0  4413.5    0.05       0  4993.9    0.07       0
  4999.9    0.05       0  5042.7    0.05       0  5120.1     0.1       0
  5278.6    0.16       0  5355.1     0.1       0  5501.4    0.16       0
  5615.9     0.1       0  5645.4    0.16       0
Bank Sta=4993.9,4999.9
Exp/Cntr=0.3,0.1

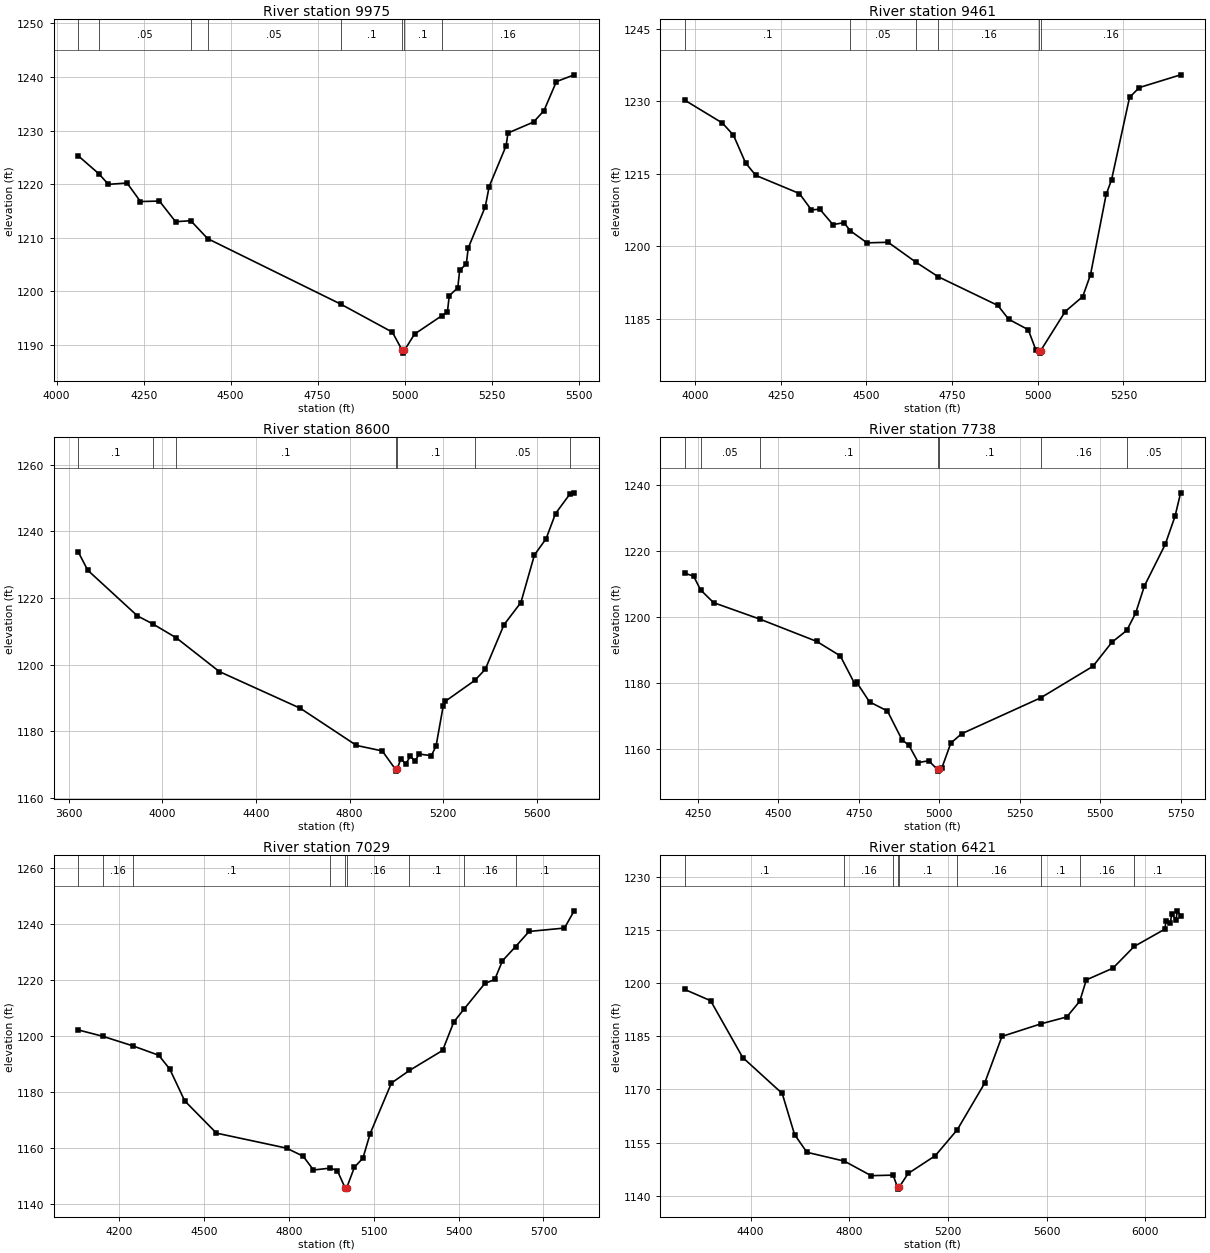
Type RM Length L Ch R = 1,9975,514,514,514
BEGIN DESCRIPTION:
ROUGH HOLLOW 20.0
END DESCRIPTION:
XS GIS Cut Line= 2
      2921327.97     10060013.69      2922656.09     10059498.07
#Sta/Elev= 30
  4062.3 1225.28  4121.5 1221.93  4148.7 1219.97  4202.3 1220.22  4240.8 1216.76
  4295.3 1216.85  4341.7 1213.00  4385.5 1213.18  4433.8 1209.84  4816.5 1197.61
  4964.7 1192.38  4993.1 1188.97  4995.9 1188.47  4999.1 1188.97  5028.3 1192.02
  5106.9 1195.46  5122.7 1196.09  5128.1 1199.19  5152.6 1200.66  5158.0 1203.93
  5177.2 1205.12  5182.5 1208.07  5231.6 1215.79  5242.8 1219.56  5291.4 1227.16
  5296.8 1229.55  5370.4 1231.60  5400.3 1233.73  5435.9 1239.14  5487.0 1240.41
#Mann=8,-1,0
  4062.3     0.1       0  4121.5    0.05       0  4385.5     0.1       0
  4433.8    0.05       0  4816.5     0.1       0  4993.1    0.07       0
  4999.1     0.1       0  5106.9    0.16       0
Bank Sta=4993.1,4999.1
Exp/Cntr=0.3,0.1

Type RM Length L Ch R = 1,9461,861,861,861
BEGIN DESCRIPTION:
ROUGH HOLLOW 19.0
END DESCRIPTION:
XS GIS Cut Line= 3
      2921786.27     10060492.87      2922473.78     10060222.03
      2922775.86     10059581.41
#Sta/Elev= 30
  3969.7 1230.23  4079.5 1225.50  4111.8 1222.98  4147.0 1217.26  4176.8 1214.68
  4304.1 1210.92  4339.3 1207.52  4363.7 1207.68  4402.0 1204.49  4434.2 1204.88
  4453.2 1203.18  4501.7 1200.71  4563.2 1200.83  4644.5 1196.70  4709.4 1193.70
  4883.6 1187.75  4915.1 1184.90  4972.1 1182.74  4994.5 1178.53  5002.3 1178.39
  5005.0 1177.89  5008.3 1178.39  5080.1 1186.50  5131.2 1189.59  5153.9 1194.13
  5199.5 1210.72  5215.3 1213.76  5267.8 1230.81  5296.1 1232.84  5416.9 1235.48
#Mann=6,-1,0
  3969.7     0.1       0  4453.2    0.05       0  4644.5     0.1       0
  4709.4    0.16       0  5002.3    0.07       0  5008.3    0.16       0
Bank Sta=5002.3,5008.3
Exp/Cntr=0.3,0.1

Type RM Length L Ch R = 1,8600,862,862,862
BEGIN DESCRIPTION:
ROUGH HOLLOW 17.0
END DESCRIPTION:
XS GIS Cut Line= 3
      2921848.77     10060607.45      2922619.62     10060492.86
      2923958.14     10060524.11
#Sta/Elev= 30
  3641.1 1233.78  3681.2 1228.34  3893.5 1214.64  3959.4 1212.22  4059.8 1208.04
  4243.4 1197.93  4589.3 1186.92  4829.4 1175.77  4939.4 1174.12  4996.4 1168.56
  4999.2 1168.06  5002.4 1168.56  5019.4 1171.83  5039.4 1170.17  5059.4 1172.52
  5079.4 1171.09  5097.4 1173.18  5149.5 1172.70  5169.5 1175.65  5199.5 1187.47
  5209.5 1189.05  5334.6 1195.27  5379.5 1198.60  5459.5 1211.98  5531.7 1218.64
  5589.6 1232.91  5639.6 1237.81  5679.6 1245.33  5742.4 1251.32  5759.3 1251.56
#Mann=7,-1,0
  3641.1     0.1       0  3959.4    0.05       0  4059.8     0.1       0
  4996.4    0.07       0  5002.4     0.1       0  5334.6    0.05       0
  5742.4    0.16       0
Bank Sta=4996.4,5002.4
Exp/Cntr=0.3,0.1

Type RM Length L Ch R = 1,7738,709,709,709
BEGIN DESCRIPTION:
ROUGH HOLLOW 15.0
END DESCRIPTION:
XS GIS Cut Line= 3
      2922182.09     10061169.94      2922640.45     10061289.74
      2923685.38     10061076.59
#Sta/Elev= 30
  4209.5 1213.25  4236.8 1212.38  4258.6 1208.20  4298.8 1204.35  4442.7 1199.36
  4619.2 1192.62  4692.4 1188.24  4737.8 1179.72  4742.9 1180.29  4783.3 1174.31
  4838.9 1171.55  4884.3 1162.83  4905.8 1161.16  4934.9 1155.95  4967.0 1156.48
  4994.6 1153.85  4997.4 1153.35  5000.6 1153.85  5007.8 1154.27  5035.9 1161.83
  5069.1 1164.65  5315.0 1175.54  5477.3 1185.08  5536.1 1192.35  5582.5 1195.95
  5610.0 1201.19  5637.2 1209.40  5701.8 1221.96  5732.4 1230.51  5749.7 1237.59
#Mann=7,-1,0
  4209.5     0.1       0  4258.6    0.05       0  4442.7     0.1       0
  4994.6    0.07       0  5000.6     0.1       0  5315.0    0.16       0
  5582.5    0.05       0
Bank Sta=4994.6,5000.6
Exp/Cntr=0.3,0.1

Type RM Length L Ch R = 1,7029,608,608,608
BEGIN DESCRIPTION:
ROUGH HOLLOW 13.0
END DESCRIPTION:
XS GIS Cut Line= 4
      2922135.28     10061669.96      2922734.20     10061945.99
      2923510.24     10061867.86      2923774.67     10061701.95
#Sta/Elev= 30
  4056.8 1202.15  4142.9 1199.90  4249.4 1196.47  4340.8 1193.12  4379.6 1188.22
  4432.6 1176.84  4544.8 1165.31  4792.3 1159.96  4851.2 1157.06  4887.5 1152.16
  4947.0 1152.82  4971.8 1151.91  4999.0 1145.82  5001.7 1145.32  5005.0 1145.82
  5032.1 1153.13  5062.3 1156.42  5087.8 1165.16  5162.8 1183.20  5226.7 1187.70
  5343.7 1194.85  5383.3 1205.02  5420.0 1209.68  5492.8 1218.75  5527.9 1220.17
  5555.0 1226.84  5601.7 1231.95  5649.3 1237.33  5774.2 1238.54  5808.4 1244.69
#Mann=9,-1,0
  4056.8     0.1       0  4142.9    0.16       0  4249.4     0.1       0
  4947.0    0.16       0  4999.0    0.07       0  5005.0    0.16       0
  5226.7     0.1       0  5420.0    0.16       0  5601.7     0.1       0
Bank Sta=4999,5005
Exp/Cntr=0.3,0.1

Type RM Length L Ch R = 1,6421,856,856,856
BEGIN DESCRIPTION:
ROUGH HOLLOW 12.0
END DESCRIPTION:
XS GIS Cut Line= 3
      2922223.79     10062529.32      2923640.45     10062477.24
      2924175.21     10062222.84
#Sta/Elev= 30
  4133.4 1198.23  4238.1 1195.05  4368.2 1179.01  4528.3 1168.85  4578.4 1157.24
  4628.4 1152.24  4780.1 1149.75  4888.6 1145.64  4977.8 1145.79  4995.7 1142.34
  4998.4 1141.84  5001.7 1142.34  5038.7 1146.26  5148.8 1151.28  5238.0 1158.63
  5348.9 1171.77  5418.9 1184.97  5578.4 1188.55  5681.7 1190.47  5734.4 1194.91
  5760.9 1200.93  5868.9 1204.25  5954.8 1210.37  6078.9 1215.25  6084.4 1217.64
  6101.6 1216.97  6107.1 1219.68  6124.3 1217.78  6129.8 1220.44  6143.2 1218.96
#Mann=9,-1,0
  4133.4     0.1       0  4780.1    0.16       0  4977.8     0.1       0
  4995.7    0.07       0  5001.7     0.1       0  5238.0    0.16       0
  5578.4     0.1       0  5734.4    0.16       0  5954.8     0.1       0
Bank Sta=4995.7,5001.7
Exp/Cntr=0.3,0.1

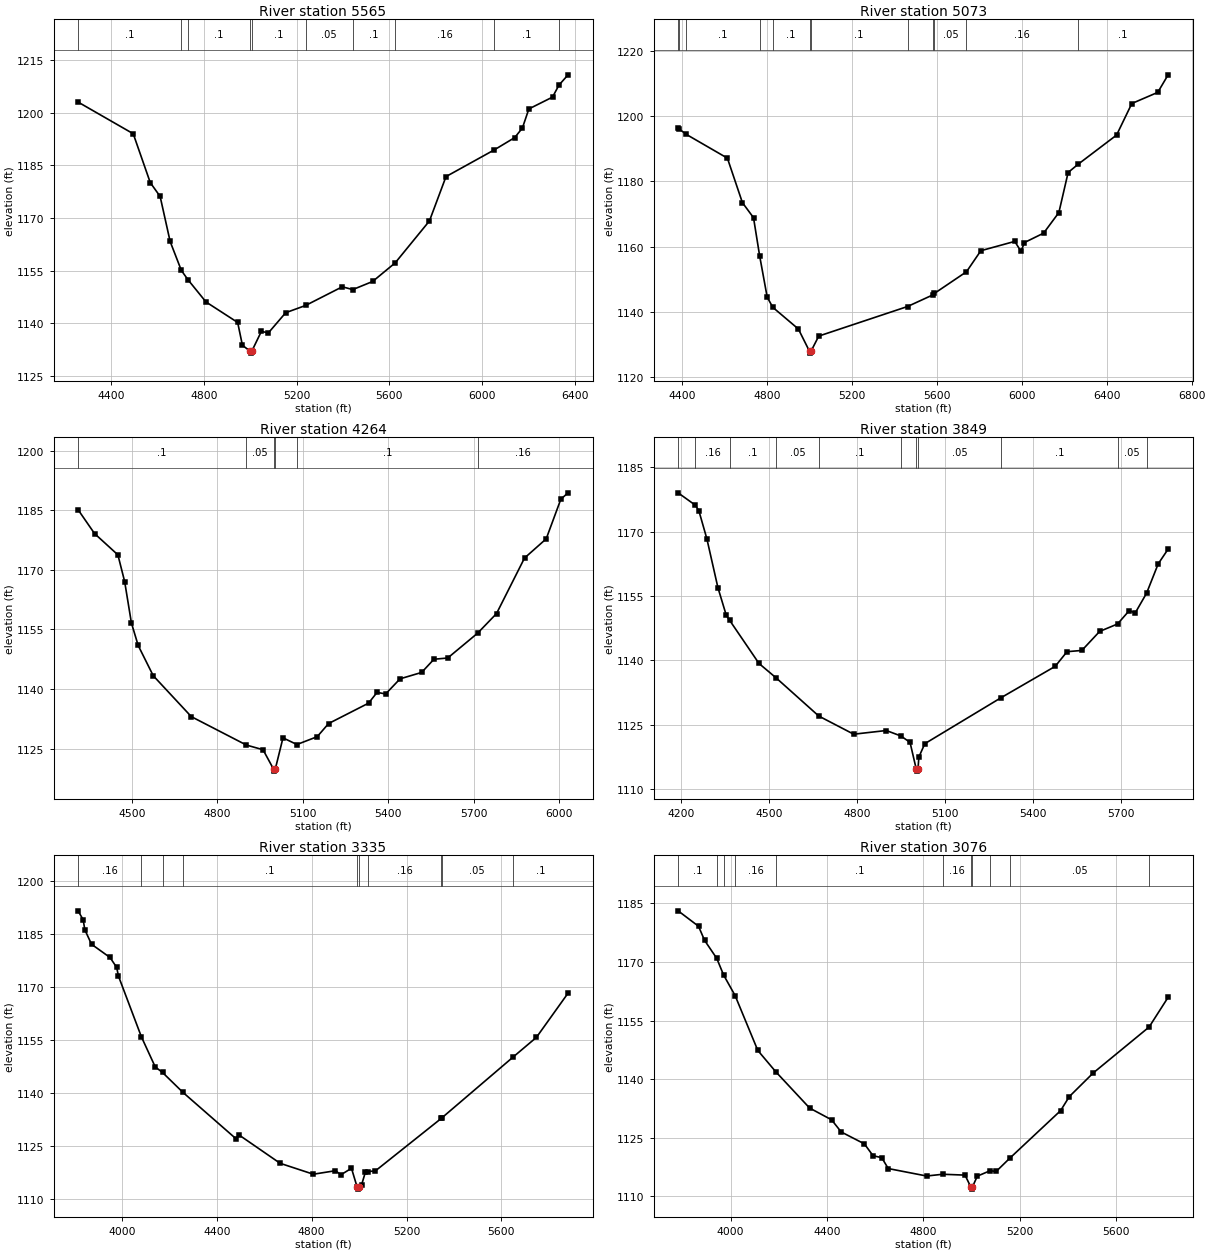
Type RM Length L Ch R = 1,5565,492,492,492
BEGIN DESCRIPTION:
ROUGH HOLLOW 10.0
END DESCRIPTION:
XS GIS Cut Line= 3
      2922239.38     10063044.93      2922682.12     10063315.78
      2924244.03     10062987.78
#Sta/Elev= 30
  4256.2 1202.99  4494.4 1193.97  4567.9 1180.06  4610.5 1176.12  4653.7 1163.30
  4702.0 1155.07  4730.7 1152.41  4808.4 1146.09  4945.2 1140.25  4965.6 1133.77
  4999.8 1132.02  5002.5 1131.52  5005.8 1132.02  5047.4 1137.70  5078.0 1137.30
  5152.4 1143.02  5238.5 1145.09  5396.7 1150.40  5442.0 1149.61  5527.6 1151.91
  5625.0 1157.21  5772.9 1169.15  5844.4 1181.77  6052.4 1189.36  6140.7 1192.86
  6174.2 1195.60  6202.0 1201.03  6304.2 1204.40  6331.9 1207.81  6371.2 1210.74
#Mann=10,-1,0
  4256.2     0.1       0  4702.0    0.16       0  4730.7     0.1       0
  4999.8    0.07       0  5005.8     0.1       0  5238.5    0.05       0
  5442.0     0.1       0  5625.0    0.16       0  6052.4     0.1       0
  6331.9    0.16       0
Bank Sta=4999.8,5005.8
Exp/Cntr=0.3,0.1

Type RM Length L Ch R = 1,5073,809,809,809
BEGIN DESCRIPTION:
ROUGH HOLLOW 9.0
END DESCRIPTION:
XS GIS Cut Line= 4
      2922447.72     10064018.91      2922827.95     10063794.95
      2923786.28     10063539.74      2924593.56     10063873.06
#Sta/Elev= 30
  4382.8 1196.34  4387.2 1196.11  4420.4 1194.46  4614.8 1187.13  4685.4 1173.49
  4737.7 1168.87  4766.5 1157.19  4802.1 1144.49  4828.6 1141.37  4948.8 1134.73
  5001.7 1127.83  5004.4 1127.33  5007.7 1127.83  5044.8 1132.56  5462.7 1141.63
  5581.8 1145.19  5589.4 1145.66  5740.1 1152.29  5807.7 1158.74  5967.3 1161.60
  5996.6 1158.55  6012.9 1161.25  6103.1 1164.13  6174.9 1170.44  6218.5 1182.73
  6264.3 1185.20  6446.6 1194.21  6518.3 1203.89  6640.4 1207.31  6689.2 1212.69
#Mann=12,-1,0
  4382.8     0.1       0  4387.2    0.05       0  4420.4     0.1       0
  4766.5    0.05       0  4828.6     0.1       0  5001.7    0.07       0
  5007.7     0.1       0  5462.7    0.05       0  5581.8     0.1       0
  5589.4    0.05       0  5740.1    0.16       0  6264.3     0.1       0
Bank Sta=5001.7,5007.7
Exp/Cntr=0.3,0.1

Type RM Length L Ch R = 1,4264,415,415,415
BEGIN DESCRIPTION:
ROUGH HOLLOW 7.0
END DESCRIPTION:
XS GIS Cut Line= 4
      2922661.28     10064315.78      2923031.08     10064472.03
      2923734.20     10064466.82      2924333.19     10064602.24
#Sta/Elev= 30
  4311.7 1185.14  4369.5 1179.13  4451.5 1173.76  4475.2 1167.03  4498.9 1156.62
  4522.6 1150.95  4575.4 1143.34  4709.0 1133.03  4902.3 1125.87  4960.5 1124.70
  4997.5 1119.81  5000.3 1119.31  5003.5 1119.81  5030.5 1127.69  5079.4 1126.01
  5150.5 1127.98  5190.5 1131.29  5330.6 1136.42  5360.6 1139.14  5390.6 1138.74
  5441.2 1142.55  5516.9 1144.16  5560.0 1147.48  5608.3 1147.79  5713.3 1154.05
  5779.5 1158.98  5877.7 1172.96  5953.8 1177.80  6005.1 1187.78  6030.4 1189.38
#Mann=6,-1,0
  4311.7     0.1       0  4902.3    0.05       0  4997.5   0.035       0
  5003.5    0.05       0  5079.4     0.1       0  5713.3    0.16       0
Bank Sta=4997.5,5003.5
Exp/Cntr=0.3,0.1

Type RM Length L Ch R = 1,3849,514,514,514
BEGIN DESCRIPTION:
ROUGH HOLLOW 6.0
END DESCRIPTION:
XS GIS Cut Line= 3
      2922525.83     10064591.80      2922958.16     10064836.61
      2924119.66     10064992.87
#Sta/Elev= 30
  4190.4 1179.09  4248.8 1176.22  4261.0 1174.93  4288.4 1168.35  4325.9 1157.00
  4354.3 1150.56  4366.0 1149.35  4465.9 1139.30  4525.2 1135.88  4669.5 1127.04
  4788.4 1122.81  4899.4 1123.67  4948.6 1122.41  4980.2 1120.92  5001.3 1114.70
  5004.0 1114.20  5007.3 1114.70  5010.4 1117.50  5030.6 1120.60  5291.0 1131.35
  5474.6 1138.63  5514.9 1142.05  5565.4 1142.34  5625.9 1146.77  5686.9 1148.51
  5726.8 1151.63  5747.0 1151.07  5785.9 1155.70  5825.4 1162.53  5859.2 1165.97
#Mann=11,-1,0
  4190.4     0.1       0  4248.8    0.16       0  4366.0     0.1       0
  4525.2    0.05       0  4669.5     0.1       0  4948.6    0.05       0
  5001.3   0.035       0  5007.3    0.05       0  5291.0     0.1       0
  5686.9    0.05       0  5785.9    0.16       0
Bank Sta=5001.3,5007.3
Exp/Cntr=0.3,0.1

Type RM Length L Ch R = 1,3335,259,259,259
BEGIN DESCRIPTION:
ROUGH HOLLOW 5.0
END DESCRIPTION:
XS GIS Cut Line= 3
      2922218.58     10064623.07      2922723.78     10065117.86
      2923890.43     10065815.76
#Sta/Elev= 30
  3814.7 1191.45  3836.3 1188.94  3843.3 1186.10  3871.6 1182.01  3949.5 1178.27
  3977.8 1175.46  3984.8 1173.08  4082.1 1155.83  4140.3 1147.36  4170.9 1145.80
  4256.2 1140.23  4479.8 1127.14  4494.0 1128.13  4667.1 1120.14  4807.0 1117.06
  4900.2 1118.05  4923.5 1116.91  4967.9 1118.74  4992.1 1113.35  4994.9 1112.85
  4998.1 1113.35  5010.7 1114.09  5026.3 1117.60  5039.4 1117.81  5069.1 1118.02
  5346.2 1132.80  5348.3 1132.93  5648.5 1150.09  5747.9 1155.71  5881.3 1168.20
#Mann=10,-1,0
  3814.7    0.16       0  4082.1     0.1       0  4170.9    0.16       0
  4256.2     0.1       0  4992.1    0.07       0  4998.1     0.1       0
  5039.4    0.16       0  5346.2     0.1       0  5348.3    0.05       0
  5648.5     0.1       0
Bank Sta=4992.1,4998.1
Exp/Cntr=0.3,0.1

Type RM Length L Ch R = 1,3076,627,627,627
BEGIN DESCRIPTION:
ROUGH HOLLOW 4.0
END DESCRIPTION:
XS GIS Cut Line= 3
      2921880.00     10065175.15      2922551.91     10065284.53
      2923676.88     10066034.51
#Sta/Elev= 30
  3782.4 1183.12  3867.0 1179.17  3892.3 1175.54  3942.6 1170.95  3971.1 1166.68
  4018.9 1161.40  4113.0 1147.35  4187.4 1141.90  4328.0 1132.59  4419.1 1129.58
  4458.9 1126.47  4555.0 1123.42  4591.1 1120.38  4627.1 1119.88  4654.2 1117.09
  4813.4 1115.18  4880.3 1115.63  4972.7 1115.41  4996.9 1112.32  4999.6 1111.82
  5002.9 1112.32  5023.7 1115.15  5076.5 1116.53  5101.9 1116.35  5157.6 1119.70
  5369.3 1131.94  5405.3 1135.53  5504.6 1141.59  5736.3 1153.35  5815.2 1160.97
#Mann=11,-1,0
  3782.4     0.1       0  3942.6    0.16       0  3971.1     0.1       0
  4018.9    0.16       0  4187.4     0.1       0  4880.3    0.16       0
  4996.9    0.07       0  5002.9    0.16       0  5076.5     0.1       0
  5157.6    0.05       0  5736.3     0.1       0
Bank Sta=4996.9,5002.9
Exp/Cntr=0.3,0.1

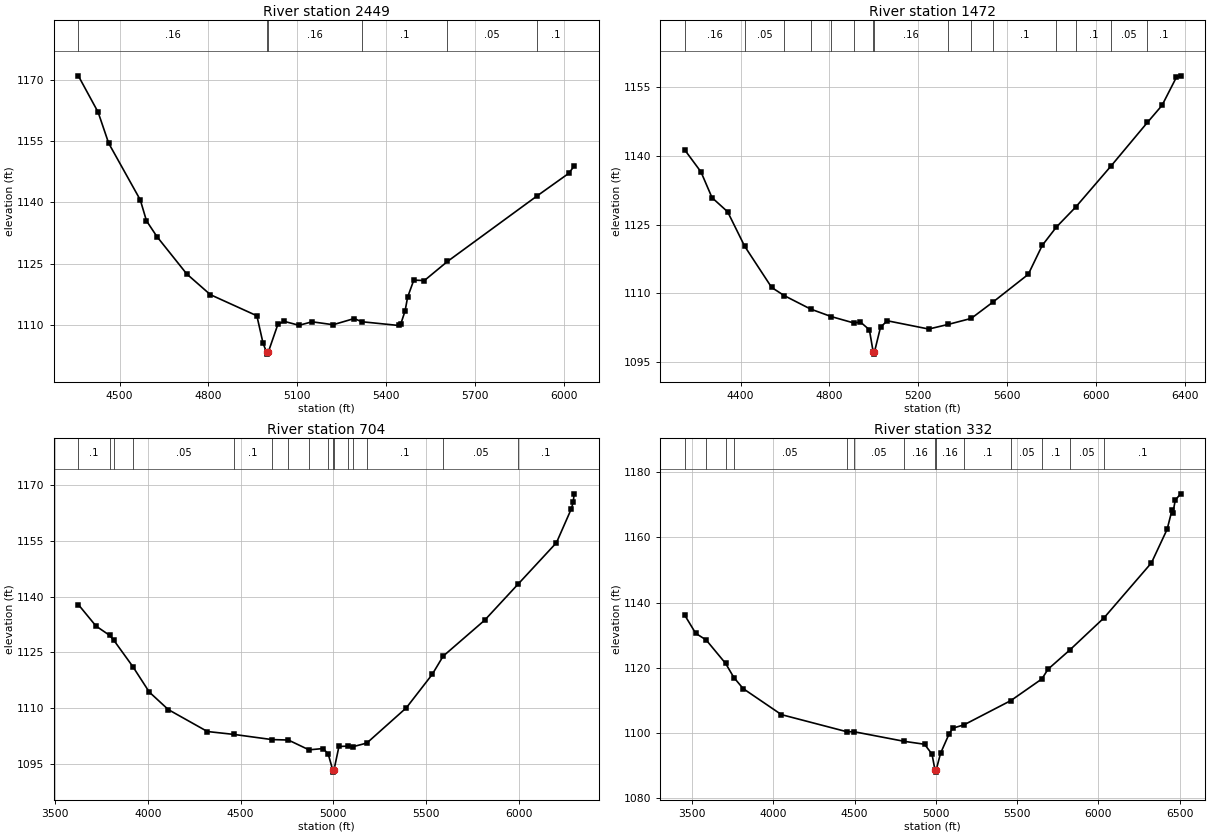
Type RM Length L Ch R = 1,2449,977,977,977
BEGIN DESCRIPTION:
ROUGH HOLLOW 3.0
END DESCRIPTION:
XS GIS Cut Line= 2
      2921984.21     10065446.00      2923343.50     10066425.10
#Sta/Elev= 30
  4360.6 1171.10  4427.5 1162.16  4463.1 1154.55  4569.9 1140.63  4590.8 1135.50
  4626.4 1131.60  4727.0 1122.44  4806.7 1117.36  4963.8 1112.18  4984.7 1105.44
  4996.4 1103.26  4999.2 1102.76  5002.4 1103.26  5035.0 1110.12  5056.0 1110.81
  5106.2 1109.84  5150.4 1110.70  5221.6 1109.98  5292.8 1111.50  5317.6 1110.72
  5443.7 1109.79  5450.4 1110.24  5464.6 1113.39  5473.1 1116.74  5494.0 1120.94
  5529.6 1120.82  5607.6 1125.51  5909.6 1141.56  6017.3 1147.14  6035.8 1148.94
#Mann=6,-1,0
  4360.6    0.16       0  4996.4    0.07       0  5002.4    0.16       0
  5317.6     0.1       0  5607.6    0.05       0  5909.6     0.1       0
Bank Sta=4996.4,5002.4
Exp/Cntr=0.3,0.1

Type RM Length L Ch R = 1,1472,768,768,768
BEGIN DESCRIPTION:
ROUGH HOLLOW 2.0
END DESCRIPTION:
XS GIS Cut Line= 4
      2921755.04     10065774.12      2922161.28     10066206.40
      2922202.95     10066680.36      2923312.29     10067034.52
#Sta/Elev= 30
  4148.8 1141.34  4221.6 1136.56  4271.4 1130.93  4341.8 1127.84  4418.2 1120.34
  4540.1 1111.31  4597.2 1109.52  4715.2 1106.60  4809.2 1104.94  4910.1 1103.56
  4940.1 1103.75  4980.3 1102.07  4997.3 1097.25  5000.1 1096.75  5003.3 1097.25
  5030.4 1102.62  5060.6 1104.04  5247.6 1102.23  5335.2 1103.24  5438.9 1104.55
  5538.0 1108.16  5696.0 1114.18  5758.9 1120.50  5822.9 1124.52  5909.7 1128.87
  6069.3 1137.87  6232.9 1147.37  6298.5 1151.08  6362.9 1157.19  6382.3 1157.54
#Mann=15,-1,0
  4148.8    0.16       0  4418.2    0.05       0  4597.2     0.1       0
  4715.2    0.05       0  4809.2     0.1       0  4910.1    0.16       0
  4997.3    0.07       0  5003.3    0.16       0  5335.2     0.1       0
  5438.9    0.05       0  5538.0     0.1       0  5822.9    0.05       0
  5909.7     0.1       0  6069.3    0.05       0  6232.9     0.1       0
Bank Sta=4997.3,5003.3
Exp/Cntr=0.3,0.1

Type RM Length L Ch R = 1,704,372,372,372
BEGIN DESCRIPTION:
Mapping XS e84e635b
END DESCRIPTION:
XS GIS Cut Line= 4
      2921601.61     10065770.24      2921836.00     10066820.62
      2922808.22     10067193.89      2923363.61     10067154.83
#Sta/Elev= 30
  3624.6 1137.83  3720.1 1132.04  3793.2 1129.56  3816.8 1128.17  3918.5 1121.14
  4007.3 1114.28  4109.7 1109.57  4320.8 1103.66  4463.9 1102.88  4668.9 1101.49
  4757.4 1101.37  4868.6 1098.73  4945.6 1099.08  4972.6 1097.57  4997.2 1093.23
  5000.0 1092.73  5003.2 1093.23  5030.3 1099.63  5076.6 1099.73  5105.2 1099.57
  5180.6 1100.55  5393.7 1110.04  5533.1 1119.01  5592.2 1123.94  5816.7 1133.64
  5996.1 1143.31  6203.6 1154.49  6283.8 1163.62  6293.8 1165.37  6299.0 1167.64
#Mann=16,-1,0
  3624.6     0.1       0  3793.2    0.16       0  3816.8     0.1       0
  3918.5    0.05       0  4463.9     0.1       0  4668.9    0.05       0
  4757.4     0.1       0  4868.6    0.05       0  4972.6     0.1       0
  4997.2    0.07       0  5003.2     0.1       0  5076.6    0.16       0
  5105.2    0.05       0  5180.6     0.1       0  5592.2    0.05       0
  5996.1     0.1       0
Bank Sta=4997.2,5003.2
Exp/Cntr=0.3,0.1

Type RM Length L Ch R = 1,332,0,0,0
BEGIN DESCRIPTION:
ROUGH HOLLOW 1.0
END DESCRIPTION:
XS GIS Cut Line= 4
      2921553.88     10065805.00      2921740.51     10067150.48
      2922239.64     10067371.84      2923381.17     10067285.03
#Sta/Elev= 30
  3456.2 1136.08  3523.3 1130.55  3587.8 1128.50  3707.4 1121.30  3758.0 1116.99
  3815.2 1113.59  4050.6 1105.61  4451.9 1100.38  4498.3 1100.36  4806.1 1097.42
  4930.4 1096.53  4976.4 1093.51  4995.3 1088.48  4998.0 1087.98  5001.3 1088.48
  5028.9 1093.74  5081.0 1099.64  5104.2 1101.47  5172.1 1102.45  5462.0 1109.94
  5651.8 1116.55  5690.4 1119.56  5822.1 1125.36  6034.4 1135.30  6325.9 1152.16
  6422.5 1162.46  6452.1 1168.29  6457.1 1167.30  6472.6 1171.41  6505.4 1173.33
#Mann=14,-1,0
  3456.2     0.1       0  3587.8    0.16       0  3707.4     0.1       0
  3758.0    0.05       0  4451.9     0.1       0  4498.3    0.05       0
  4806.1    0.16       0  4995.3    0.07       0  5001.3    0.16       0
  5172.1     0.1       0  5462.0    0.05       0  5651.8     0.1       0
  5822.1    0.05       0  6034.4     0.1       0
Bank Sta=4995.3,5001.3
Exp/Cntr=0.3,0.1

Chan Stop Cuts=-1