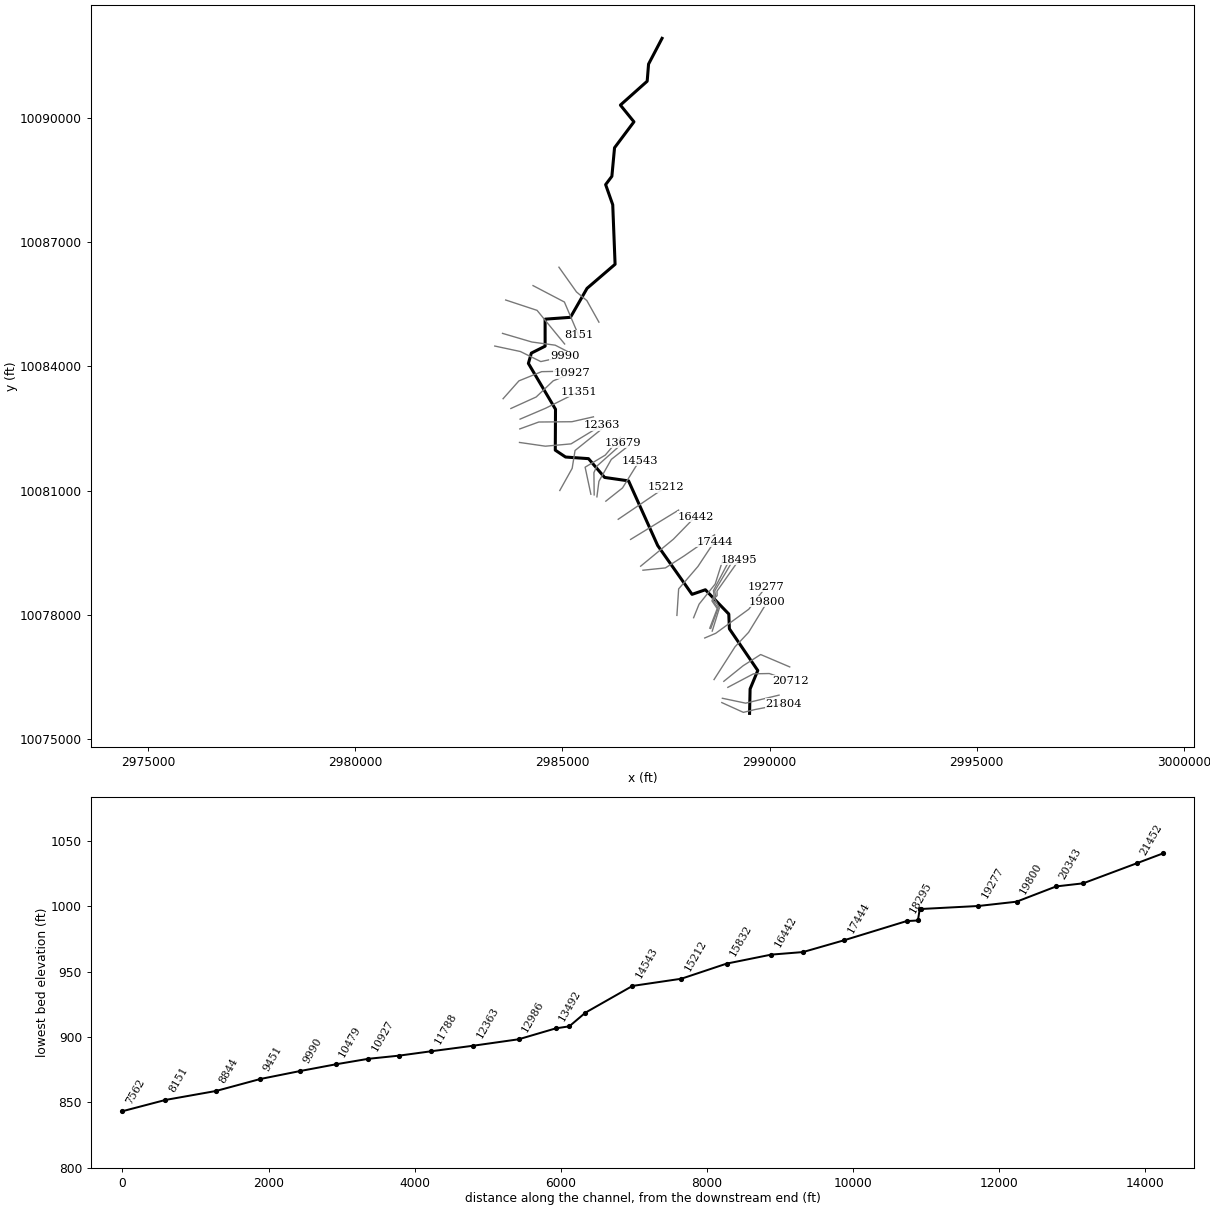
--- ROY CREEK.prj (project) ---

Proj Title=ROY CREEK Base Level Engineering
Current Plan=p01
Default Exp/Contr=0.3,0.1
English Units
Geom File=g01
Flow File=f01
Plan File=p01
Y Axis Title=Elevation
X Axis Title(PF)=Main Channel Distance
X Axis Title(XS)=Station
BEGIN DESCRIPTION:
ROY CREEK
END DESCRIPTION:
DSS Export Rating Curves= 0
DSS Export Rating Curve Sorted= 0
DSS Export Volume Flow Curves= 0
DXF OffsetX= 0
DXF OffsetY= 0
DXF ScaleX= 1
DXF ScaleY= 10

--- ROY CREEK.p01 (plan) ---

Plan Title=Multiple Run
Short Identifier=Multiple
Geom File=g01
Flow File=f01
Subcritical Flow
K Sum by GR= 0
Std Step Tol= 0.01
Critical Tol= 0.01
Num of Std Step Trials= 20
Max Error Tol= 0.3
Flow Tol Ratio= 0.001
Split Flow NTrial= 30
Split Flow Tol= 0.02
Split Flow Ratio= 0.02
Log Output Level= 0
Friction Slope Method= 1
Unsteady Friction Slope Method= 2
Unsteady Bridges Friction Slope Method= 1
Parabolic Critical Depth
Global Vel Dist=  1 , 1 , 1
Global Log Level= 0
CheckData=True
Encroach Param= -1, 0, 0, 0
BEGIN DESCRIPTION:
Multiple Run
END DESCRIPTION:

--- ROY CREEK.f01 (steady flow) ---

Flow Title=Multiple
Program Version=4.10
Number of Profiles= 7
Profile Names=10-year,25-year,50-year,1pct_min,100-year,1pct_plu,500-year
River Rch & RM=ROY CREEK,Reach-1         ,21804
    1541    2306    2992    2839    3839    5192    6347
River Rch & RM=ROY CREEK,Reach-1         ,18495
    1957    2957    3862    3684    4982    6737    8326
River Rch & RM=ROY CREEK,Reach-1         ,12363
    2207    3346    4379    4183    5657    7651    9484
River Rch & RM=ROY CREEK,Reach-1         ,6266
    2772    4253    5610    5398    7301    9873   12422
River Rch & RM=ROY CREEK,Reach-1         ,5790
    2772    4253    5610    5398    7301    9873   12422
Boundary for River Rch & Prof#=ROY CREEK,Reach-1         , 1
Up Type= 0
Dn Type= 3
Dn Slope=0.005
Boundary for River Rch & Prof#=ROY CREEK,Reach-1         , 2
Up Type= 0
Dn Type= 3
Dn Slope=0.005
Boundary for River Rch & Prof#=ROY CREEK,Reach-1         , 3
Up Type= 0
Dn Type= 3
Dn Slope=0.005
Boundary for River Rch & Prof#=ROY CREEK,Reach-1         , 4
Up Type= 0
Dn Type= 3
Dn Slope=0.005
Boundary for River Rch & Prof#=ROY CREEK,Reach-1         , 5
Up Type= 0
Dn Type= 3
Dn Slope=0.005
Boundary for River Rch & Prof#=ROY CREEK,Reach-1         , 6
Up Type= 0
Dn Type= 3
Dn Slope=0.005
Boundary for River Rch & Prof#=ROY CREEK,Reach-1         , 7
Up Type= 0
Dn Type= 3
Dn Slope=0.005
DSS Import GetInterval= 0
DSS Import GetPeak= 0
DSS Import FillOption= 0

--- ROY CREEK.g01 (geometry) ---

Geom Title=Existing Conditions
Program Version=4.10

River Reach=ROY CREEK       ,Reach-1
Reach XY= 30
      2989518.47     10075623.73      2989531.41     10076212.73
      2989716.67     10076657.94      2989031.61     10077664.97
      2989017.11     10078021.37      2988452.02     10078606.86
      2988130.72     10078495.94      2987301.12     10079674.83
       2986598.6     10081234.03      2986020.19     10081317.58
      2985631.69      10081770.7      2985078.16     10081809.78
      2984830.19     10081975.24      2984835.52     10082962.48
      2984180.97     10084069.19      2984252.84     10084317.86
      2984585.04     10084485.22       2984584.5     10085136.98
      2985196.21       10085181.      2985596.19     10085879.98
      2986273.22     10086461.48      2986216.46     10087897.85
      2986045.04     10088383.55      2986195.89     10088584.85
      2986260.03     10089273.09       2986728.5     10089899.09
      2986401.38     10090302.71       2987047.9     10090879.21
      2987081.12     10091292.55      2987406.66     10091913.64

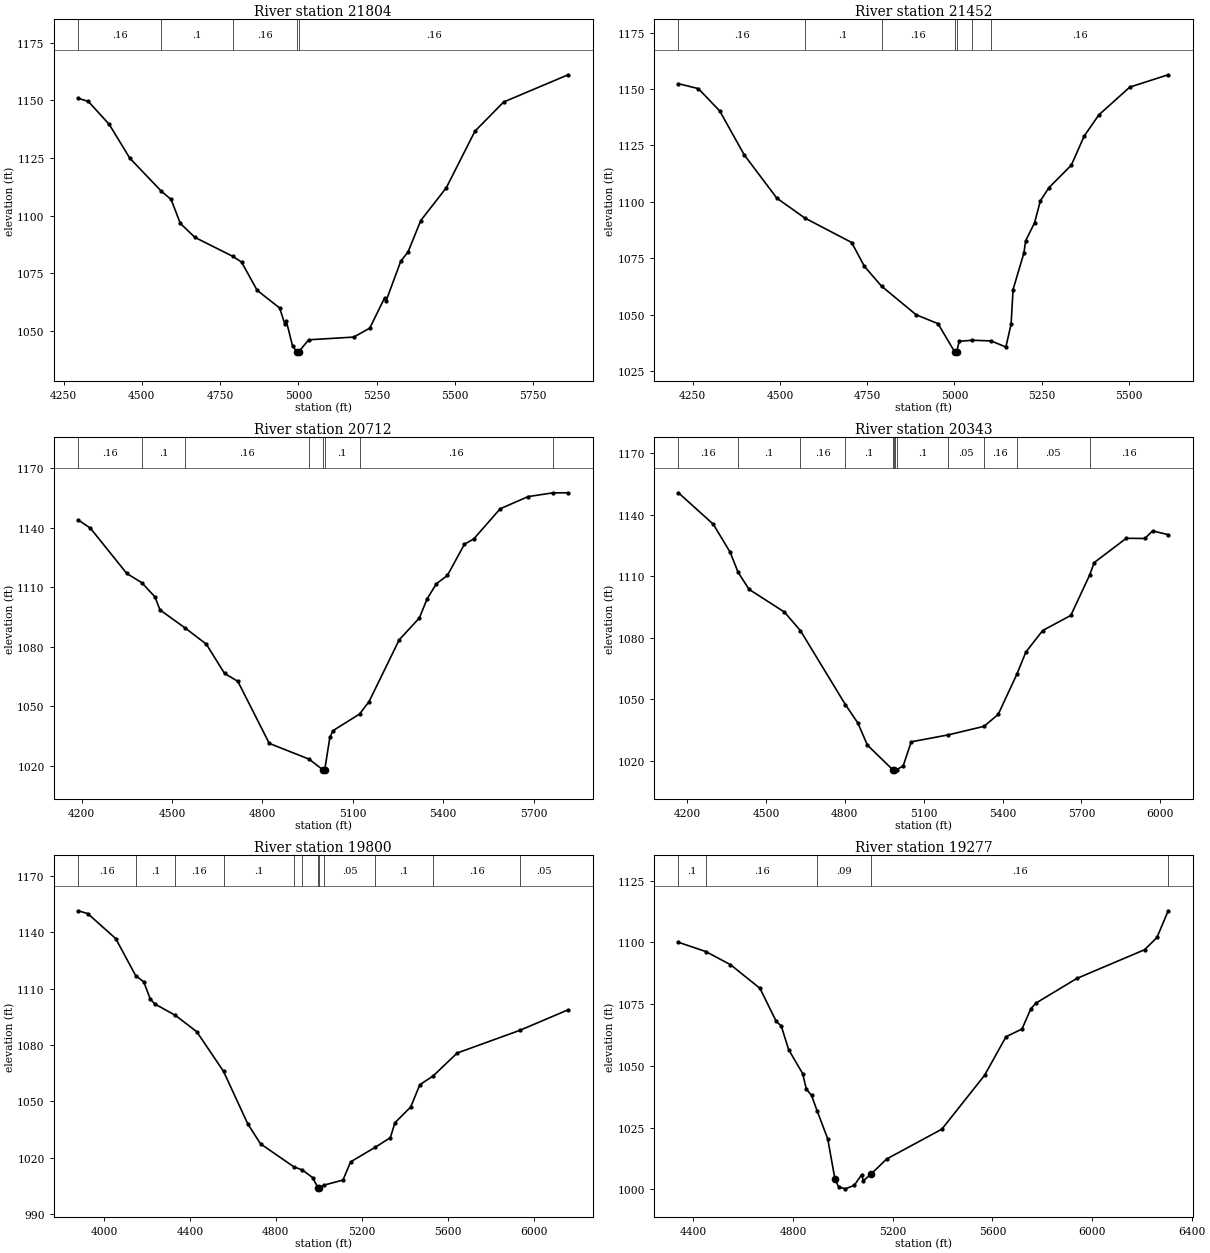
Type RM Length L Ch R = 1 ,21804   ,352,352,352
BEGIN DESCRIPTION:
ROY CREEK 49.0
END DESCRIPTION:
XS GIS Cut Line= 4
      2988848.66     10075883.96      2989369.52     10075647.84
      2989654.24     10075717.28      2990340.47     10075848.98
#Sta/Elev= 30
  4297.2 1150.85  4329.3 1149.48  4395.8 1139.54  4461.7 1124.84  4561.7 1110.63
  4593.4 1106.96  4622.8  1096.6    4669 1090.55    4790 1082.32  4818.5 1079.78
    4868 1067.57    4940 1059.89  4956.4 1052.93  4961.5 1054.08  4981.2 1043.38
  4995.1 1040.94  4997.8 1040.44  5001.1 1040.94  5032.7  1046.1  5176.6 1047.27
  5227.8 1051.18  5274.7  1064.2  5279.8 1062.98  5326.7 1080.21  5349.7 1084.14
  5390.5 1097.84  5471.9 1112.03  5563.6 1136.62  5655.2 1149.25  5860.9 1161.06
#Mann= 5 ,-1 , 0
  4297.2     .16       0  4561.7      .1       0    4790     .16       0
  4995.1     .07       0  5001.1     .16       0
Bank Sta=4995.1,5001.1
XS Rating Curve= 0 ,0
Exp/Cntr=0.3,0.1

Type RM Length L Ch R = 1 ,21452   ,740,740,740
BEGIN DESCRIPTION:
ROY CREEK 48.0
END DESCRIPTION:
XS GIS Cut Line= 3
      2988862.55     10075988.12      2989425.07     10075870.06
      2990230.65     10076064.51
#Sta/Elev= 30
  4209.1 1152.37  4266.2 1150.18  4327.5 1140.25  4397.4 1120.86    4491 1101.62
    4571 1092.82  4705.6 1081.94  4741.5 1071.46    4791  1062.6  4890.2  1049.9
  4952.9 1045.96  5000.4 1033.52  5003.2 1033.02  5006.4 1033.52  5013.7 1038.15
  5051.7  1038.6  5104.9 1038.31  5147.4  1035.6  5162.3 1045.71    5168 1061.08
  5198.9 1077.22  5204.2 1082.76  5229.7 1090.72  5246.1 1100.39  5270.9 1106.27
    5335 1116.25  5371.7 1129.12  5413.6 1138.49  5502.5 1150.86  5612.6 1156.32
#Mann= 7 ,-1 , 0
  4209.1     .16       0    4571      .1       0    4791     .16       0
  5000.4     .07       0  5006.4     .16       0  5051.7      .1       0
  5104.9     .16       0
Bank Sta=5000.4,5006.4
XS Rating Curve= 0 ,0
Exp/Cntr=0.3,0.1

Type RM Length L Ch R = 1 ,20712   ,369,369,369
BEGIN DESCRIPTION:
ROY CREEK 47.0
END DESCRIPTION:
XS GIS Cut Line= 4
      2988994.53     10076252.01      2989612.57     10076578.39
      2989994.52     10076585.34      2990508.39     10076404.79
#Sta/Elev= 30
  4189.1  1143.8    4229 1139.69  4349.8  1116.9  4399.7 1112.24  4443.5 1105.07
  4459.9 1098.57    4544 1089.39    4614 1081.29  4674.4 1066.56  4718.4  1062.6
  4822.8 1031.36  4955.2 1023.41  5000.9 1018.04  5003.7 1017.54  5006.9 1018.04
  5023.9 1034.37  5033.9 1037.72  5122.5 1046.13    5154 1052.38    5254 1083.48
    5321 1094.48  5346.7 1104.12  5377.7 1111.74    5414 1115.87  5470.6 1131.61
  5501.6 1134.28  5589.3 1149.45  5682.2 1155.59  5763.9 1157.46  5814.7  1157.5
#Mann= 8 ,-1 , 0
  4189.1     .16       0  4399.7      .1       0    4544     .16       0
  4955.2      .1       0  5000.9     .07       0  5006.9      .1       0
  5122.5     .16       0  5763.9     .05       0
Bank Sta=5000.9,5006.9
XS Rating Curve= 0 ,0
Exp/Cntr=0.3,0.1

Type RM Length L Ch R = 1 ,20343   ,543,543,543
BEGIN DESCRIPTION:
ROY CREEK 46.0
END DESCRIPTION:
XS GIS Cut Line= 4
       2988897.3     10076397.84      2989362.57     10076772.84
      2989786.19     10077043.67      2990487.59     10076745.05
#Sta/Elev= 30
  4167.3 1150.77  4299.9 1135.42  4363.9 1121.79  4394.3 1111.95  4435.9 1103.69
  4570.2 1092.62    4631 1083.58  4802.1 1047.51  4849.6 1038.51  4885.9 1027.74
  4982.7 1015.68  4985.5 1015.18  4988.7 1015.68  4990.2  1015.7  4997.5 1015.76
  5022.1  1017.6  5052.5 1029.33    5193  1032.7  5329.6 1036.89  5383.3 1042.69
    5454  1062.2  5488.7 1073.11  5552.7 1083.61  5659.6 1090.97  5731.5 1110.72
  5748.4 1116.72  5870.4 1128.58  5941.3 1128.48  5970.4  1132.2    6030 1130.33
#Mann= 12 ,-1 , 0
  4167.3     .16       0  4394.3      .1       0    4631     .16       0
  4802.1      .1       0  4982.7     .07       0  4988.7      .1       0
  4990.2     .16       0  4997.5      .1       0    5193     .05       0
  5329.6     .16       0    5454     .05       0  5731.5     .16       0
Bank Sta=4982.7,4988.7
XS Rating Curve= 0 ,0
Exp/Cntr=0.3,0.1

Type RM Length L Ch R = 1 ,19800   ,523,523,523
BEGIN DESCRIPTION:
ROY CREEK 45.0
END DESCRIPTION:
XS GIS Cut Line= 4
       2988661.2     10076439.52      2989168.13     10077231.17
      2989494.52     10077578.39      2989945.92     10078314.52
#Sta/Elev= 30
  3880.6 1151.51  3924.5    1150  4054.7 1136.69  4147.6 1116.98    4185 1113.67
  4215.4 1104.57  4236.5 1101.92  4331.8 1095.87  4431.8 1087.14  4556.6    1066
  4669.5 1038.04  4728.7 1027.46  4883.4 1015.24    4924 1013.47  4971.4 1009.46
  4996.7 1003.98  4999.4 1003.48  5002.7 1003.98  5023.9 1005.44  5112.5 1008.15
  5148.2 1017.84  5263.5 1025.66  5333.1 1030.73  5354.4 1038.65  5427.9 1047.04
  5470.4  1058.9  5531.8 1063.53  5644.5 1075.79  5936.6 1087.89  6160.7 1098.79
#Mann= 12 ,-1 , 0
  3880.6     .16       0  4147.6      .1       0  4331.8     .16       0
  4556.6      .1       0  4883.4     .05       0    4924     .16       0
  4996.7     .07       0  5002.7     .16       0  5023.9     .05       0
  5263.5      .1       0  5531.8     .16       0  5936.6     .05       0
Bank Sta=4996.7,5002.7
XS Rating Curve= 0 ,0
Exp/Cntr=0.3,0.1

Type RM Length L Ch R = 1 ,19277   ,782,782,782
BEGIN DESCRIPTION:
ROY CREEK 44.0
END DESCRIPTION:
XS GIS Cut Line= 4
      2988436.52     10077443.04      2988701.23     10077555.87
      2989499.84     10078137.47      2989920.87     10078684.37
#Sta/Elev= 30
  4339.7 1100.02  4449.5 1096.27  4548.4 1090.97  4666.8 1081.39  4731.7 1068.11
  4752.6 1066.07  4781.9 1056.57  4838.3 1046.85    4853 1040.62  4873.9    1038
  4896.2 1031.79  4938.8 1020.47  4968.1 1004.05  4982.8    1001  5009.6 1000.19
  5045.4 1001.61  5074.8 1005.88  5081.8 1003.44  5112.7 1006.17  5175.2 1012.25
    5397 1024.36  5568.5 1046.16  5654.5 1061.77  5718.8 1064.92  5754.2 1073.12
    5775 1075.42    5939 1085.39  6210.8 1097.01  6260.6    1102  6305.6 1112.78
#Mann= 5 ,-1 , 0
  4339.7      .1       0  4449.5     .16       0  4896.2     .09       0
  5112.7     .16       0  6305.6     .16       0
Bank Sta=4968.1,5112.7
XS Rating Curve= 0 ,0
Exp/Cntr=0.3,0.1

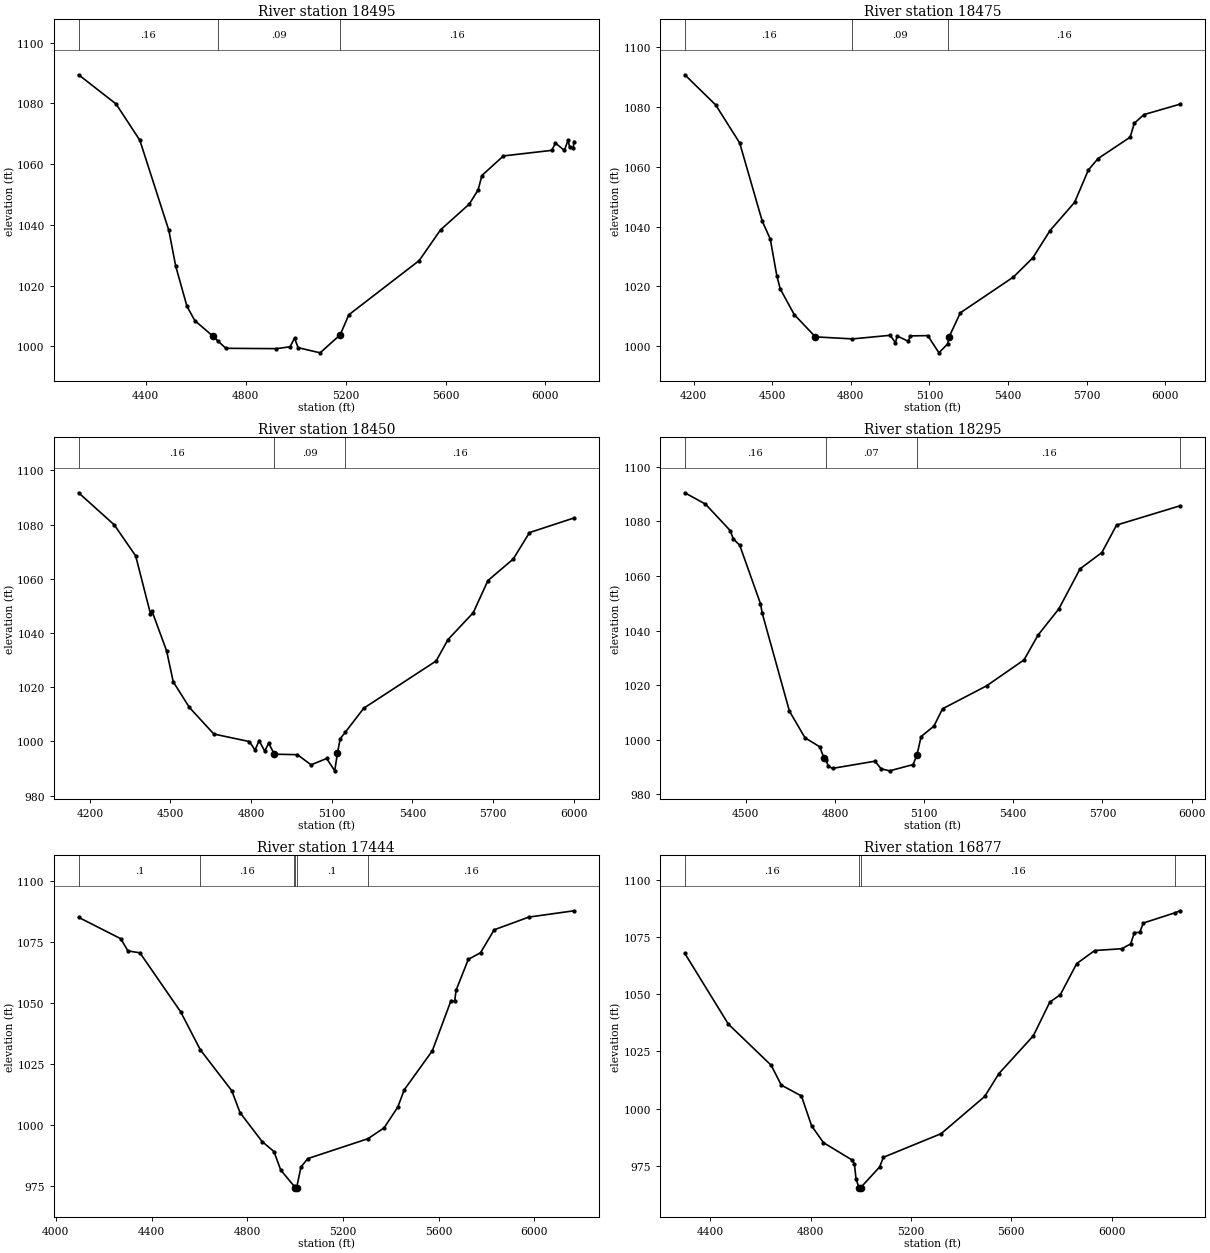
Type RM Length L Ch R = 1 ,18495   ,20,20,20
BEGIN DESCRIPTION:
Mapping XS 95b6d3ae
END DESCRIPTION:
XS GIS Cut Line= 6
      2988617.91     10077609.73      2988789.77     10078164.38
      2988667.38     10078403.96      2988735.08     10078463.86
      2988732.48     10078573.23      2989265.52     10079329.89
#Sta/Elev= 30
  4132.3 1089.43    4282 1079.83  4377.3 1067.85  4493.3 1038.18  4520.7 1026.44
  4565.7 1013.22  4597.1 1008.52  4670.4 1003.32  4688.9 1001.84  4721.3  999.39
  4923.2  999.28  4978.2  999.89  4996.1 1002.77  5010.3   999.6  5098.5   997.9
  5178.7 1003.84  5213.4 1010.44  5494.7 1028.27  5580.3  1038.4    5695 1046.85
  5730.7 1051.57  5745.5 1056.27  5831.7 1062.72  6025.1 1064.55  6039.9 1066.94
  6075.6 1064.53  6090.4 1067.95  6096.5 1065.57  6111.3 1065.43  6113.8 1067.42
#Mann= 3 ,-1 , 0
  4132.3     .16       0  4688.9     .09       0  5178.7     .16       0
Bank Sta=4670.4,5178.7
XS Rating Curve= 0 ,0
Exp/Cntr=0.3,0.1

Type RM Length L Ch R = 1 ,18475   ,25,25,25
BEGIN DESCRIPTION:
Mapping XS e1c7b70b
END DESCRIPTION:
XS GIS Cut Line= 6
      2988581.45     10077672.23      2988761.13     10078161.77
      2988636.13     10078338.86      2988696.02     10078463.86
      2988677.79     10078578.44      2989132.66     10079340.02
#Sta/Elev= 30
  4166.9 1090.73  4284.6 1080.64  4376.1 1067.94  4462.2 1041.79  4492.7 1035.86
  4517.9 1023.51  4530.7 1019.18  4584.2 1010.57    4665 1003.11  4806.4 1002.43
    4950 1003.63  4970.4 1001.18  4977.2 1003.41  5019.8  1001.6  5026.6 1003.43
  5093.9 1003.53  5136.2  997.77  5169.5 1000.74  5175.2 1003.12    5218 1011.15
  5420.4 1023.11  5494.3 1029.51  5560.1 1038.64  5653.8 1048.06  5706.4 1058.89
  5743.4 1062.72  5865.9 1069.87  5881.5 1074.51  5918.5 1077.42  6056.6 1080.91
#Mann= 3 ,-1 , 0
  4166.9     .16       0  4806.4     .09       0  5169.5     .16       0
Bank Sta=4665,5175.2
XS Rating Curve= 0 ,0
Exp/Cntr=0.3,0.1

Type RM Length L Ch R = 1 ,18450   ,155,155,155
BEGIN DESCRIPTION:
ROY CREEK 42.0
END DESCRIPTION:
XS GIS Cut Line= 6
      2988557.98     10077679.96      2988737.69     10078151.36
      2988610.08     10078338.86      2988662.17     10078471.67
      2988646.54     10078586.25      2989039.77     10079336.25
#Sta/Elev= 30
  4158.2 1091.72  4290.9 1079.88  4370.5 1068.42  4425.3 1047.15  4430.7 1048.21
  4485.5 1033.39  4510.3 1021.96  4570.4  1012.5  4661.3  1002.7  4793.6  999.92
  4814.6  996.78  4829.5 1000.27  4850.5  996.42  4865.4  999.31  4886.4  995.27
  4972.3  995.08    5023  991.34    5081  993.68    5111  989.12  5121.3  995.77
  5131.4 1000.96  5150.4 1003.37  5219.1 1012.23  5488.3 1029.65  5532.4 1037.55
  5626.3 1047.46  5681.1 1059.35    5775 1067.25  5835.6 1077.03    6001 1082.42
#Mann= 3 ,-1 , 0
  4158.2     .16       0  4886.4     .09       0  5150.4     .16       0
Bank Sta=4886.4,5121.3
XS Rating Curve= 0 ,0
Exp/Cntr=0.3,0.1

Type RM Length L Ch R = 1 ,18295   ,851,851,851
BEGIN DESCRIPTION:
ROY CREEK 41.0
END DESCRIPTION:
XS GIS Cut Line= 4
      2988168.14     10077932.58      2988300.07     10078258.95
      2988688.96     10078745.06       2988897.3     10079404.79
#Sta/Elev= 30
    4295 1090.49  4364.5 1086.33  4447.6 1076.65    4458  1073.6  4479.6 1071.27
  4549.5 1049.85  4555.1 1046.47  4646.9  1010.5  4699.2 1000.74  4748.9  997.43
  4763.3  993.23  4769.7  992.68  4777.7  990.24  4792.1  989.54  4934.5  992.16
  4955.4  989.39  4983.9  988.63  5062.6  990.91  5075.8  994.34  5089.8 1001.18
    5133 1005.01  5161.9 1011.36  5310.1 1019.76    5436 1029.26  5483.4 1038.38
  5553.4 1047.99  5624.7 1062.63  5698.1  1068.6  5747.4 1078.66  5961.4 1085.73
#Mann= 4 ,-1 , 0
    4295     .16       0  4769.7     .07       0  5075.8     .16       0
  5961.4      .1       0
Bank Sta=4763.3,5075.8
XS Rating Curve= 0 ,0
Exp/Cntr=0.3,0.1

Type RM Length L Ch R = 1 ,17444   ,567,567,567
BEGIN DESCRIPTION:
ROY CREEK 39.0
END DESCRIPTION:
XS GIS Cut Line= 4
      2987765.35     10077988.12      2987807.02       10078627.
       2988272.3     10079168.67      2988668.13     10079765.89
#Sta/Elev= 30
  4095.1 1085.07  4271.1 1076.33  4301.2 1071.33  4351.3 1070.56  4521.6 1046.44
  4603.8 1030.92  4735.3 1014.18    4770 1005.19  4862.1  993.39  4911.5   989.3
  4940.1  981.73  4996.3  975.09  5000.7  974.53  5003.5  974.03  5006.7  974.53
  5024.6  982.95  5053.1   986.4  5304.7  994.53  5372.4  998.98  5429.5 1007.48
  5456.5 1014.54  5573.8 1030.48    5652 1051.02  5667.1 1050.66  5673.1 1055.24
  5724.2 1067.86  5775.4 1070.61  5832.5 1079.97  5976.9 1085.16  6165.9 1087.75
#Mann= 6 ,-1 , 0
  4095.1      .1       0  4603.8     .16       0  4996.3      .1       0
  5000.7     .07       0  5006.7      .1       0  5304.7     .16       0
Bank Sta=5000.7,5006.7
XS Rating Curve= 0 ,0
Exp/Cntr=0.3,0.1

Type RM Length L Ch R = 1 ,16877   ,435,435,435
BEGIN DESCRIPTION:
ROY CREEK 38.0
END DESCRIPTION:
XS GIS Cut Line= 4
      2986945.93     10079078.39      2987487.57     10079133.95
      2987932.02     10079418.67      2988674.29     10079932.01
#Sta/Elev= 30
  4298.3 1067.77  4471.7 1036.91  4642.6 1018.91  4682.8 1010.26  4763.3  1005.5
  4803.5   992.5  4850.7  985.13  4965.7  977.48  4974.5  975.73  4980.9  969.14
  4993.1  965.43  4995.9  964.93  4999.1  965.43  5074.8  974.48    5090  978.72
    5320  989.03  5493.9  1005.3  5550.6 1015.31  5687.8 1031.81  5753.4 1046.51
  5795.3 1049.75  5860.8 1063.37  5932.5 1069.05  6039.9 1069.84  6075.8 1071.93
  6090.6  1076.9  6111.6 1076.96  6126.4 1081.07  6252.1 1085.53  6273.1 1086.42
#Mann= 4 ,-1 , 0
  4298.3     .16       0  4993.1     .07       0  4999.1     .16       0
  6252.1      .1       0
Bank Sta=4993.1,4999.1
XS Rating Curve= 0 ,0
Exp/Cntr=0.3,0.1

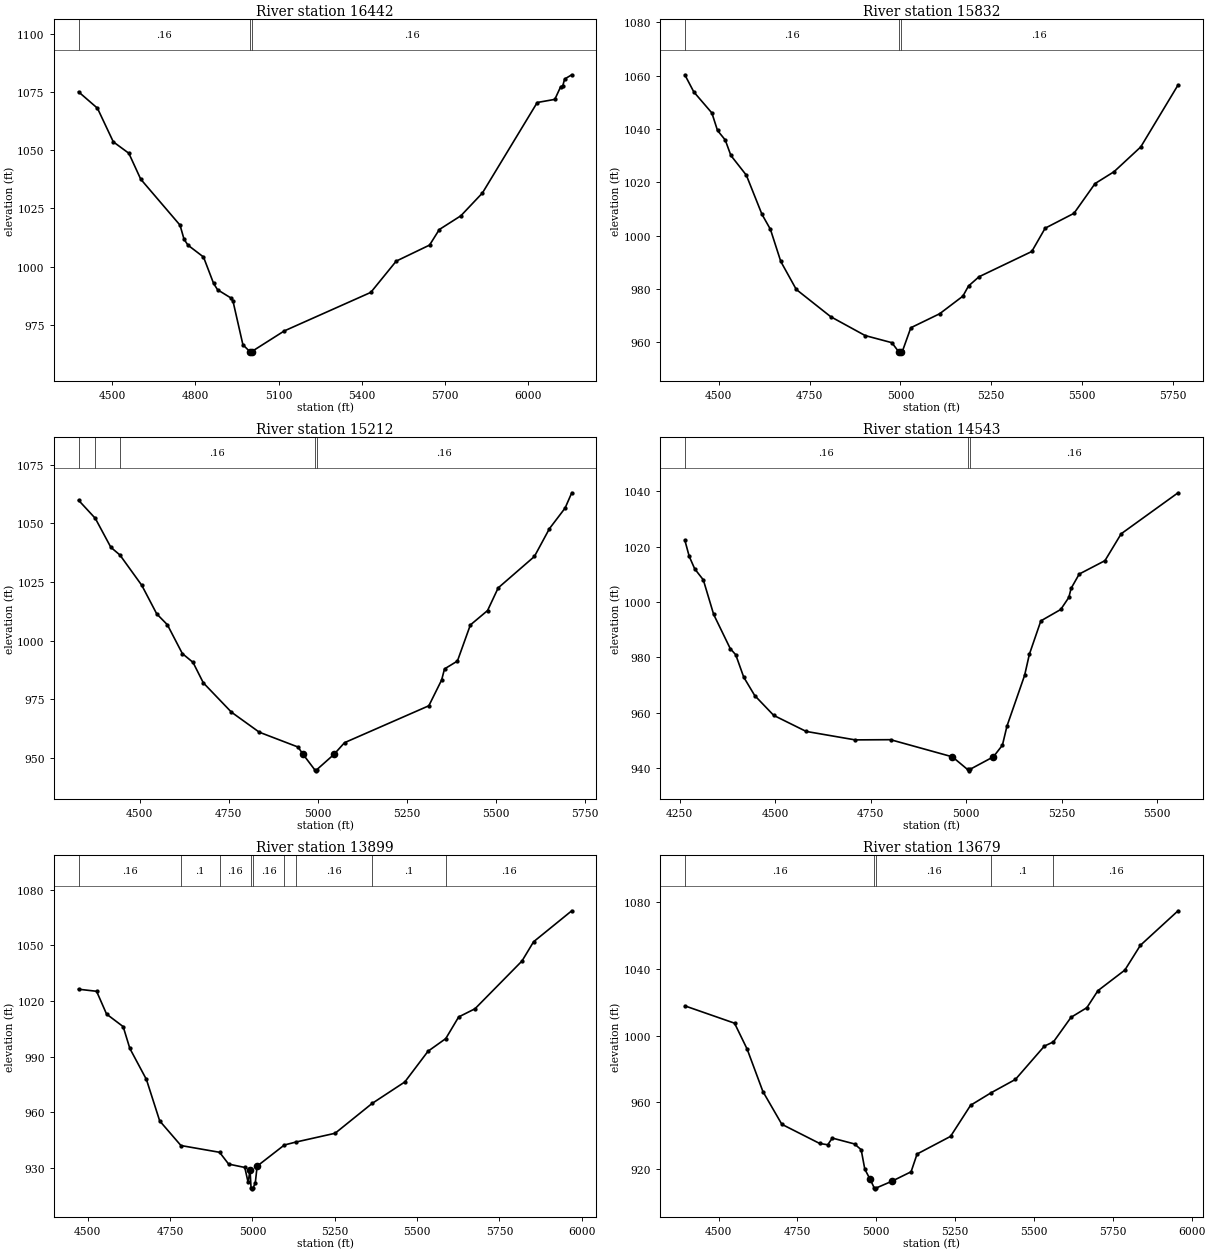
Type RM Length L Ch R = 1 ,16442   ,610,610,610
BEGIN DESCRIPTION:
ROY CREEK 37.0
END DESCRIPTION:
XS GIS Cut Line= 3
      2986890.33      10079175.6      2987682.02     10079828.39
      2988209.18     10080369.42
#Sta/Elev= 30
  4377.6  1075.1  4445.9 1068.07  4503.3  1053.6  4559.3 1048.71  4602.3 1037.57
  4744.3 1017.81  4758.7 1011.77    4773 1009.22    4829 1004.14  4865.5  992.78
  4879.9  990.06  4929.4  986.44  4935.8  985.03  4971.4  966.43  4996.7  963.47
  4999.4  962.97  5002.7  963.47  5120.9  972.39  5433.3  988.94  5525.1 1002.37
  5645.5 1009.26  5680.7 1015.94  5758.6 1021.85  5836.3 1031.62  6034.4 1070.51
  6097.9 1071.85  6119.3 1077.37  6126.2  1077.5  6133.4 1080.59  6159.1 1082.42
#Mann= 3 ,-1 , 0
  4377.6     .16       0  4996.7     .07       0  5002.7     .16       0
Bank Sta=4996.7,5002.7
XS Rating Curve= 0 ,0
Exp/Cntr=0.3,0.1

Type RM Length L Ch R = 1 ,15832   ,620,620,620
BEGIN DESCRIPTION:
ROY CREEK 35.0
END DESCRIPTION:
XS GIS Cut Line= 2
      2986647.29     10079821.44      2987806.13     10080529.24
#Sta/Elev= 30
  4406.3 1060.37  4431.1 1053.93  4480.8 1046.05  4496.3 1039.48  4517.6 1035.91
  4533.1 1030.11  4575.7 1022.71  4618.6 1008.06    4642 1002.39  4670.5  990.35
  4713.1  979.86    4808  969.63  4902.8  962.56  4976.3  959.89  4994.6  956.58
  4997.4  956.08  5000.6  956.58  5005.3  956.66  5028.5  965.49  5107.9  970.74
  5171.8  977.34  5187.3  981.15  5216.2  984.61  5361.5  994.09  5398.3 1002.83
  5477.7 1008.41  5535.7 1019.57  5587.9 1024.01  5661.5 1033.31  5764.2 1056.54
#Mann= 3 ,-1 , 0
  4406.3     .16       0  4994.6     .07       0  5000.6     .16       0
Bank Sta=4994.6,5000.6
XS Rating Curve= 0 ,0
Exp/Cntr=0.3,0.1

Type RM Length L Ch R = 1 ,15212   ,669,669,669
BEGIN DESCRIPTION:
ROY CREEK 34.0
END DESCRIPTION:
XS GIS Cut Line= 2
      2986348.69     10080307.56      2987493.97     10081084.96
#Sta/Elev= 30
  4328.7 1059.94  4375.8 1052.19  4419.4 1039.85  4444.9 1036.56  4506.3 1023.62
  4548.2 1011.45  4578.1 1006.81  4620.1  994.51    4650  990.78  4678.9  982.05
  4757.8  969.54    4836  960.99  4944.8  954.66  4958.5  951.62  4991.4  945.01
  4994.1  944.51  4997.4  945.01  5045.3  951.48  5075.2  956.52  5311.8  972.26
  5347.7  983.25  5355.8  987.98    5392  991.33  5428.3 1006.72  5476.6 1012.87
  5506.4 1022.53  5608.1 1035.94  5650.1 1047.77  5694.2 1056.58  5712.9  1063.1
#Mann= 5 ,-1 , 0
  4328.7     .16       0  4375.8      .1       0  4444.9     .16       0
  4991.4     .07       0  4997.4     .16       0
Bank Sta=4958.5,5045.3
XS Rating Curve= 0 ,0
Exp/Cntr=0.3,0.1

Type RM Length L Ch R = 1 ,14543   ,644,644,644
BEGIN DESCRIPTION:
ROY CREEK 32.0
END DESCRIPTION:
XS GIS Cut Line= 3
      2986050.11     10080745.09      2986452.85      10081064.5
      2986862.56      10081724.2
#Sta/Elev= 30
  4263.7 1022.41  4275.2 1016.54  4289.6 1012.01  4312.1 1008.04  4339.2  995.54
  4382.5  983.21    4397  980.95  4417.8  972.88  4446.6  966.22  4496.3  959.05
  4581.2  953.25  4709.4  950.19    4802  950.26  4963.9  944.06  5003.4   939.5
  5006.1     939  5009.4   939.5  5071.1  944.07  5094.7  948.27  5106.7   955.2
  5152.8  973.52  5165.3  981.16  5195.3  993.21  5247.3  997.33  5268.5 1001.69
  5274.4 1004.95  5295.7 1010.14    5363 1014.98  5405.5  1024.7  5554.3 1039.52
#Mann= 3 ,-1 , 0
  4263.7     .16       0  5003.4     .07       0  5009.4     .16       0
Bank Sta=4963.9,5071.1
XS Rating Curve= 0 ,0
Exp/Cntr=0.3,0.1

Type RM Length L Ch R = 1 ,13899   ,220,220,220
BEGIN DESCRIPTION:
ROY CREEK 31.0
END DESCRIPTION:
XS GIS Cut Line= 4
       2985834.8     10080849.26      2985883.41     10081224.22
      2986182.02       10081752.      2986584.11      10082070.9
#Sta/Elev= 30
    4472 1026.37  4526.9 1025.25  4557.2 1012.93  4607.6 1006.16  4627.8  994.39
  4678.2   977.6  4718.5  955.22    4783  941.92  4900.3  938.27  4927.8   931.9
  4976.9  930.08    4987  921.99  4992.8  928.74  4995.9  919.03  4998.7  918.53
  5001.9  919.03  5008.7  921.61  5014.4  930.79    5097  942.21  5131.8  943.79
  5251.1  948.55  5363.3  964.64  5462.8  976.27  5533.3  992.87  5587.1  999.69
  5626.3 1011.39  5675.9 1015.81  5818.5 1041.59  5853.8 1052.01  5969.7 1068.74
#Mann= 9 ,-1 , 0
    4472     .16       0    4783      .1       0  4900.3     .16       0
  4995.9     .07       0  5001.9     .16       0    5097      .1       0
  5131.8     .16       0  5363.3      .1       0  5587.1     .16       0
Bank Sta=4992.8,5014.4
XS Rating Curve= 0 ,0
Exp/Cntr=0.3,0.1

Type RM Length L Ch R = 1 ,13679   ,187,187,187
BEGIN DESCRIPTION:
Mapping XS 2a5d86be
END DESCRIPTION:
XS GIS Cut Line= 4
      2985768.96     10080896.03      2985762.45     10081434.23
      2985836.23     10081592.65      2986471.91      10082158.9
#Sta/Elev= 30
  4392.7 1017.79  4550.4  1007.4  4590.4  991.85  4640.4  966.41  4700.4  946.79
  4820.4   935.3    4846  934.52  4860.4  938.53  4930.9  935.01    4952  931.55
  4963.5   919.9  4980.4   913.8  4993.6   908.6  4996.3   908.1  4999.6   908.6
    5049  912.62  5110.3  918.32  5129.3  928.97  5235.5  939.55  5299.1   958.2
  5364.4  965.72  5441.2  973.69  5533.2  993.69  5561.9   996.2  5617.6 1010.92
  5667.8  1016.7  5702.9  1026.9  5788.2 1039.21  5837.5 1054.08    5957 1074.78
#Mann= 5 ,-1 , 0
  4392.7     .16       0  4993.6     .07       0  4999.6     .16       0
  5364.4      .1       0  5561.9     .16       0
Bank Sta=4980.4,5049
XS Rating Curve= 0 ,0
Exp/Cntr=0.3,0.1

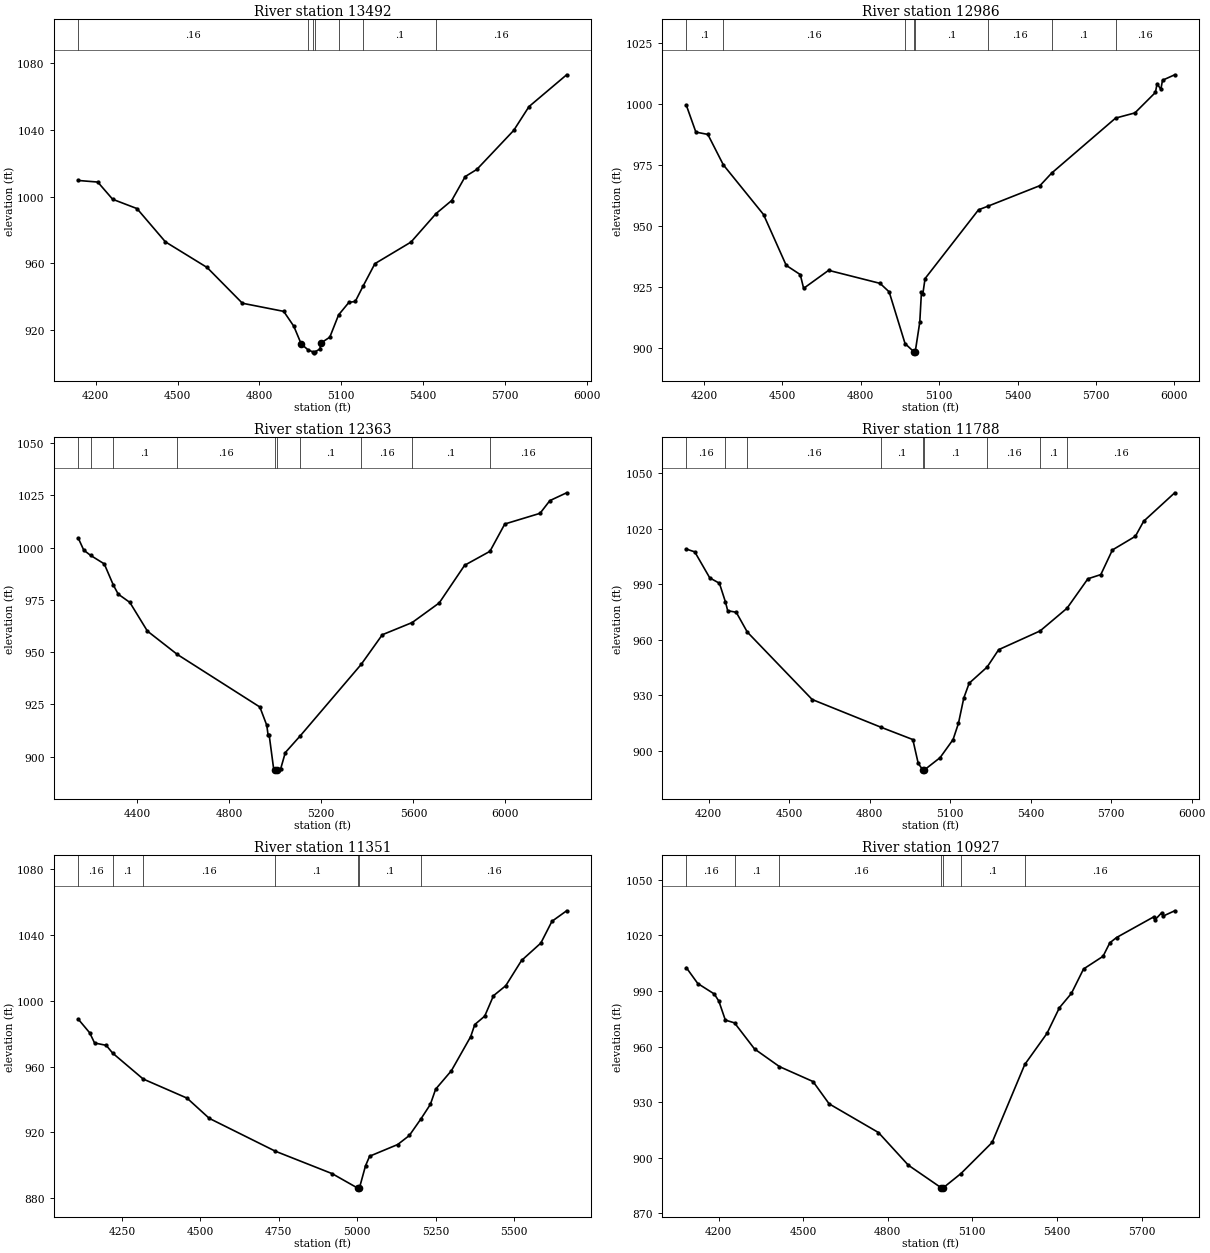
Type RM Length L Ch R = 1 ,13492   ,506,506,506
BEGIN DESCRIPTION:
ROY CREEK 30.0
END DESCRIPTION:
XS GIS Cut Line= 4
      2985688.95     10080911.77      2985550.07      10081564.5
      2986036.19     10081856.17      2986396.85     10082279.26
#Sta/Elev= 30
  4135.9 1009.67  4207.3 1008.72    4262  998.41    4351  992.85  4455.3  972.93
  4608.2  957.58  4737.5  936.19    4889  931.32    4926  922.42  4953.2  911.79
  4977.9  908.33  4996.6     907  4999.4   906.5  5002.6     907  5021.2  908.74
    5027  912.55  5057.9  915.87  5090.2  929.23  5128.1  936.72  5151.2  937.23
  5179.5  946.31  5223.3  959.88  5355.5  972.79  5447.7   989.9  5504.8  997.68
  5554.2 1011.99    5597  1016.3  5732.1 1039.64  5788.1 1053.89  5926.1 1072.93
#Mann= 7 ,-1 , 0
  4135.9     .16       0  4977.9      .1       0  4996.6     .07       0
  5002.6      .1       0  5090.2     .16       0  5179.5      .1       0
  5447.7     .16       0
Bank Sta=4953.2,5027
XS Rating Curve= 0 ,0
Exp/Cntr=0.3,0.1

Type RM Length L Ch R = 1 ,12986   ,623,623,623
BEGIN DESCRIPTION:
ROY CREEK 29.0
END DESCRIPTION:
XS GIS Cut Line= 4
      2984938.94     10081001.96      2985237.57     10081536.72
      2985307.02     10081967.28      2985945.88     10082481.15
#Sta/Elev= 30
    4133  999.58  4169.4  988.61  4215.2  987.66  4274.5  975.19  4428.3  954.84
  4515.1  934.01  4568.8  930.24  4581.7  924.59  4677.3  931.98  4874.1  926.64
  4908.9  923.16  4969.8  901.96  5002.8  898.68  5005.6  898.18  5008.8  898.68
  5026.1  910.76  5032.4  922.95  5037.5  922.12  5046.3   928.6  5250.9  956.78
  5285.3  958.19  5486.1  966.69  5530.3  971.78  5775.2  994.34  5849.2  996.47
  5927.6 1004.85    5934 1008.43  5948.4 1006.13  5954.8 1009.85  6001.5 1012.09
#Mann= 8 ,-1 , 0
    4133      .1       0  4274.5     .16       0  4969.8      .1       0
  5002.8     .07       0  5008.8      .1       0  5285.3     .16       0
  5530.3      .1       0  5775.2     .16       0
Bank Sta=5002.8,5008.8
XS Rating Curve= 0 ,0
Exp/Cntr=0.3,0.1

Type RM Length L Ch R = 1 ,12363   ,575,575,575
BEGIN DESCRIPTION:
ROY CREEK 27.0
END DESCRIPTION:
XS GIS Cut Line= 4
      2983966.76     10082161.72      2984591.74     10082071.45
       2985209.8       10082127.      2985952.82     10082578.37
#Sta/Elev= 30
  4144.3 1004.57  4168.2  998.81    4198  996.31  4257.2  992.25  4296.4  982.17
  4317.8  977.78  4368.3  973.82  4444.5  960.11  4574.6  948.92  4933.1  923.77
  4963.2     915  4968.6  910.55  4973.6  910.31  4993.4  893.84  5000.4  893.74
  5003.2  893.24  5006.4  893.74  5023.5   894.2  5043.6  901.98  5109.2  910.07
    5373  944.14    5465  958.35  5594.8  964.19  5712.2  973.57  5822.6  991.59
  5932.5  998.26    5997 1011.33  6150.1 1016.44  6192.8 1022.52  6265.7 1026.27
#Mann= 10 ,-1 , 0
  4144.3      .1       0    4198     .16       0  4296.4      .1       0
  4574.6     .16       0  5000.4     .07       0  5006.4     .16       0
  5109.2      .1       0    5373     .16       0  5594.8      .1       0
  5932.5     .16       0
Bank Sta=5000.4,5006.4
XS Rating Curve= 0 ,0
Exp/Cntr=0.3,0.1

Type RM Length L Ch R = 1 ,11788   ,437,437,437
BEGIN DESCRIPTION:
ROY CREEK 26.0
END DESCRIPTION:
XS GIS Cut Line= 4
      2983973.65      10082488.1      2984432.02     10082654.78
      2985230.63     10082661.72      2985751.44     10082779.77
#Sta/Elev= 30
  4116.5 1009.01  4147.9 1007.49  4203.8  993.41  4239.7  990.51  4262.4  980.31
  4270.6  975.65  4302.5  974.81  4343.6  964.11  4585.5   927.6  4842.9  912.54
  4960.7  905.93  4980.7   893.1  4997.7   889.5  5000.4     889  5003.7   889.5
  5062.2  896.12  5110.7  905.92  5130.7  914.68  5150.7  928.43  5170.7  936.42
  5237.4  945.12  5280.7  954.57  5435.2  964.72  5535.5     977  5613.2  992.92
  5661.4   995.2  5704.6 1008.52  5790.3 1015.93  5821.1 1024.06  5936.9 1039.47
#Mann= 9 ,-1 , 0
  4116.5     .16       0  4262.4      .1       0  4343.6     .16       0
  4842.9      .1       0  4997.7     .07       0  5003.7      .1       0
  5237.4     .16       0  5435.2      .1       0  5535.5     .16       0
Bank Sta=4997.7,5003.7
XS Rating Curve= 0 ,0
Exp/Cntr=0.3,0.1

Type RM Length L Ch R = 1 ,11351   ,424,424,424
BEGIN DESCRIPTION:
ROY CREEK 25.0
END DESCRIPTION:
XS GIS Cut Line= 3
      2983980.64     10082724.23      2984598.69     10082988.11
      2985390.33     10083383.93
#Sta/Elev= 30
  4110.6  988.91  4146.9  980.65  4162.6  974.42  4199.6  973.01  4220.6  968.19
  4317.5  952.51  4457.4  940.87  4528.2  928.57  4739.1  908.56  4920.1  894.91
    5001  886.17  5003.7  885.67    5007  886.17  5026.4  899.67  5039.5  905.52
    5129  912.63  5166.1  918.13  5203.6  928.37  5233.2  937.07    5250  946.31
  5300.3  957.57  5361.8  978.31  5374.9  985.67  5406.5  990.77  5434.4 1003.18
  5473.6 1009.29  5523.9 1024.64  5585.4 1035.22  5620.9 1048.48  5667.7 1054.88
#Mann= 7 ,-1 , 0
  4110.6     .16       0  4220.6      .1       0  4317.5     .16       0
  4739.1      .1       0    5001     .07       0    5007      .1       0
  5203.6     .16       0
Bank Sta=5001,5007
XS Rating Curve= 0 ,0
Exp/Cntr=0.3,0.1

Type RM Length L Ch R = 1 ,10927   ,448,448,448
BEGIN DESCRIPTION:
ROY CREEK 24.0
END DESCRIPTION:
XS GIS Cut Line= 4
      2983758.42     10082981.17      2984369.52     10083258.95
      2984779.24     10083647.84      2985237.61     10083835.35
#Sta/Elev= 30
    4086 1002.54  4126.5  994.01  4184.9  988.37  4201.2  984.52  4224.2  974.28
  4256.8  972.76  4327.7   958.7  4416.2  949.16  4535.1  941.12  4592.2  929.08
  4767.1   913.6  4873.1  895.97  4990.2  883.72    4993  883.22  4996.2  883.72
  5059.6  891.48    5170  908.24  5285.8  950.32  5364.5  967.09  5408.5  980.91
    5451  988.64  5494.2 1001.85  5563.3 1008.69  5587.3 1015.97  5611.3 1018.83
  5742.2  1029.9  5747.6 1028.38  5771.6 1032.26    5777 1030.44  5817.4 1033.25
#Mann= 7 ,-1 , 0
    4086     .16       0  4256.8      .1       0  4416.2     .16       0
  4990.2     .07       0  4996.2     .16       0  5059.6      .1       0
  5285.8     .16       0
Bank Sta=4990.2,4996.2
XS Rating Curve= 0 ,0
Exp/Cntr=0.3,0.1

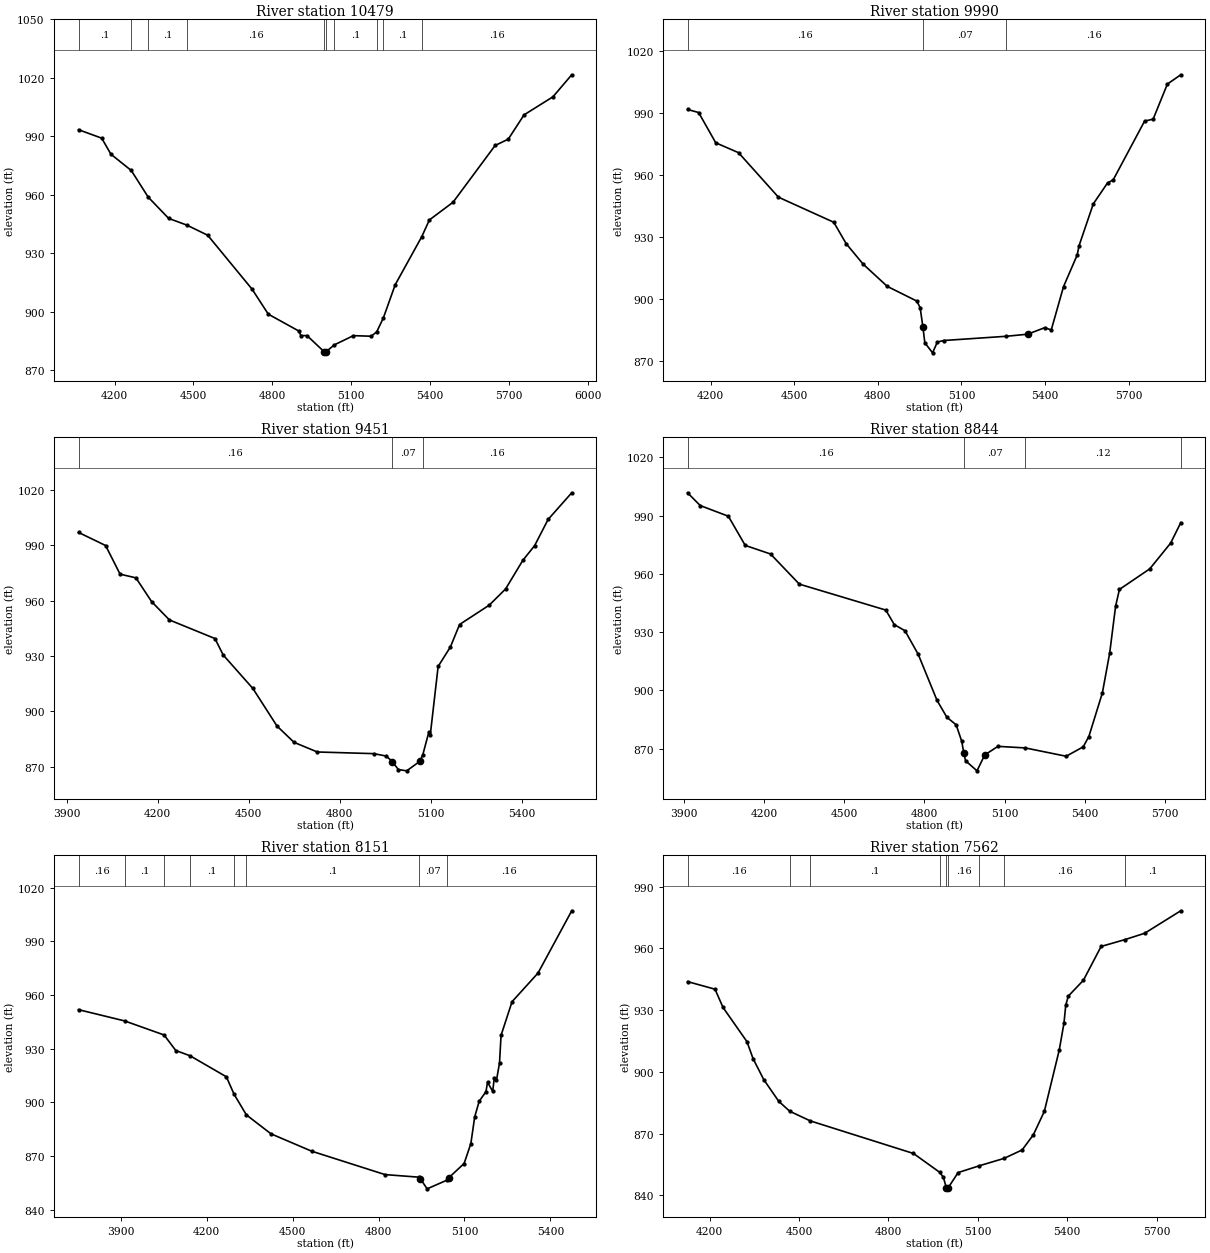
Type RM Length L Ch R = 1 ,10479   ,489,489,489
BEGIN DESCRIPTION:
ROY CREEK 23.0
END DESCRIPTION:
XS GIS Cut Line= 4
       2983570.9     10083217.28      2983952.85     10083647.84
      2984501.46     10083870.06      2985209.76     10083883.95
#Sta/Elev= 30
  4062.7  993.38  4150.9  989.04    4186   980.8  4263.3  972.47  4327.9  958.79
  4405.5  947.91  4474.9  944.45    4554  939.27  4722.9   911.6  4784.6  898.79
  4902.4  890.02  4907.8  887.82  4931.9   887.8  4997.4  879.47  5000.1  878.97
  5003.4  879.47  5035.8  883.06  5108.3  887.79  5175.9  887.48  5196.8  889.72
  5222.1  896.85  5267.2  913.89  5368.4  938.57  5397.2  947.11  5487.2  956.18
  5647.2  985.28  5697.3  988.54  5757.3 1000.99  5867.3 1010.26  5938.6 1021.54
#Mann= 10 ,-1 , 0
  4062.7      .1       0  4263.3     .05       0  4327.9      .1       0
  4474.9     .16       0  4997.4     .07       0  5003.4     .16       0
  5035.8      .1       0  5196.8     .16       0  5222.1      .1       0
  5368.4     .16       0
Bank Sta=4997.4,5003.4
XS Rating Curve= 0 ,0
Exp/Cntr=0.3,0.1

Type RM Length L Ch R = 1 ,9990    ,539,539,539
BEGIN DESCRIPTION:
ROY CREEK 22.0
END DESCRIPTION:
XS GIS Cut Line= 4
      2983369.51     10084488.11      2983987.57     10084356.17
      2984480.63     10084113.11      2985055.28     10084237.73
#Sta/Elev= 30
  4117.4  991.75  4157.2  990.27  4218.6   975.6  4300.4  970.81  4443.5  949.25
  4642.1  937.09  4686.5  926.74  4747.3  916.82    4834  906.03  4939.9  898.91
  4951.9  895.77  4962.2   886.1  4968.8  878.69  4996.6  873.82  5013.7  879.03
  5036.1  879.79  5260.7  881.84  5337.8  882.85  5399.2  886.02  5422.4   884.9
  5466.4  905.88  5515.6  921.26    5522  925.66  5573.2  945.98  5624.3  956.13
  5644.8  957.66  5757.3   986.1    5788  987.07  5839.2 1004.08  5887.1 1008.56
#Mann= 3 ,-1 , 0
  4117.4     .16       0  4962.2     .07       0  5260.7     .16       0
Bank Sta=4962.2,5337.8
XS Rating Curve= 0 ,0
Exp/Cntr=0.3,0.1

Type RM Length L Ch R = 1 ,9451    ,607,607,607
BEGIN DESCRIPTION:
ROY CREEK 21.0
END DESCRIPTION:
XS GIS Cut Line= 4
      2983556.99     10084793.68      2984265.35     10084585.34
      2984827.85     10084508.95      2985112.55     10084363.12
#Sta/Elev= 30
    3939  997.03  4028.3  989.92    4076   974.4  4128.2   972.4  4180.3  959.44
  4238.8  949.57  4388.8   939.5    4416  930.57  4513.8  912.43  4593.2   892.1
  4649.3  883.25  4726.2  878.01  4912.6  877.11  4953.7  875.79  4973.2  872.82
  4993.4   868.5  5020.9  867.79    5064  872.93  5074.1  876.58  5093.6  888.63
  5098.7  887.39  5124.5  924.38  5164.9  934.92  5195.2  947.11  5292.8  957.58
  5346.8  966.36  5403.8  981.92  5442.6  989.85    5487 1004.05  5564.9 1018.51
#Mann= 3 ,-1 , 0
    3939     .16       0  4973.2     .07       0  5074.1     .16       0
Bank Sta=4973.2,5064
XS Rating Curve= 0 ,0
Exp/Cntr=0.3,0.1

Type RM Length L Ch R = 1 ,8844    ,693,693,693
BEGIN DESCRIPTION:
ROY CREEK 20.0
END DESCRIPTION:
XS GIS Cut Line= 3
      2983633.39     10085599.23      2984390.35     10085349.22
      2985056.21     10084537.71
#Sta/Elev= 30
  3912.9 1001.81  3960.4  995.23  4065.7  989.73  4128.9  974.71  4223.7  970.28
  4331.6  954.76  4655.4   941.4    4687  933.93  4727.2  930.75  4776.7  918.62
  4847.1  894.91  4883.6  886.27  4918.8  882.29  4939.6  873.84  4947.5  867.77
    4954   863.8  4996.8  858.61  5025.7  866.78  5075.2  871.22  5177.7  870.41
  5330.7  866.12  5394.6  870.98  5415.7  876.29  5466.3  898.75  5493.6  919.19
  5515.9  943.47  5530.2  952.04  5643.6  962.61  5721.8  975.87  5759.8   986.4
#Mann= 4 ,-1 , 0
  3912.9     .16       0  4947.5     .07       0  5177.7     .12       0
  5759.8     .16       0
Bank Sta=4947.5,5025.7
XS Rating Curve= 0 ,0
Exp/Cntr=0.3,0.1

Type RM Length L Ch R = 1 ,8151    ,589,589,589
BEGIN DESCRIPTION:
ROY CREEK 18.0
END DESCRIPTION:
XS GIS Cut Line= 3
      2984293.09     10085946.46      2985050.07     10085550.61
      2985390.35     10084752.02
#Sta/Elev= 30
  3752.4  951.86  3913.4  945.57  4051.2  937.71  4092.1  929.03  4142.2  926.07
  4268.7  914.35  4295.4  904.66  4338.5  893.07  4424.3  882.49  4566.4  872.78
  4822.7  859.69  4940.2  858.26  4946.3  857.36  4969.7  851.73    5038  856.51
  5046.2  858.06  5098.9  865.88  5122.5  877.04  5135.9  891.96  5151.6  900.69
  5175.2  906.03  5180.7   911.3  5198.8  906.17  5204.3  913.89    5212  912.48
  5222.5  922.03  5227.9   937.5  5266.3  956.31  5356.9   972.3  5474.7 1007.12
#Mann= 8 ,-1 , 0
  3752.4     .16       0  3913.4      .1       0  4051.2     .05       0
  4142.2      .1       0  4295.4     .05       0  4338.5      .1       0
  4940.2     .07       0    5038     .16       0
Bank Sta=4946.3,5046.2
XS Rating Curve= 0 ,0
Exp/Cntr=0.3,0.1

Type RM Length L Ch R = 1 ,7562    ,571,571,571
BEGIN DESCRIPTION:
ROY CREEK 16.0
END DESCRIPTION:
XS GIS Cut Line= 4
      2984918.12      10086390.9      2985341.74     10085793.67
      2985591.74     10085585.34      2985883.42     10085064.48
#Sta/Elev= 30
  4126.3  943.88  4218.4  940.19  4245.4  931.29  4325.4  914.72  4346.3  906.37
    4382  896.22  4432.4  885.64    4469  880.84  4538.3  876.13  4884.3  860.29
    4972  851.16  4984.4  848.74  4994.6   843.6  4997.3   843.1  5000.6   843.6
    5034  851.01  5105.2  854.32  5188.2  857.91  5248.8  862.02  5286.5  869.41
  5323.3  880.79  5373.3  910.61  5389.2  923.74    5395   932.3  5403.5   936.8
  5454.3  944.52  5513.7  960.97  5594.1  964.32  5659.8  967.38  5780.9  978.32
#Mann= 9 ,-1 , 0
  4126.3     .16       0    4469     .05       0  4538.3      .1       0
    4972     .16       0  4994.6     .07       0  5000.6     .16       0
  5105.2      .1       0  5188.2     .16       0  5594.1      .1       0
Bank Sta=4994.6,5000.6
XS Rating Curve= 0 ,0
Exp/Cntr=0.3,0.1