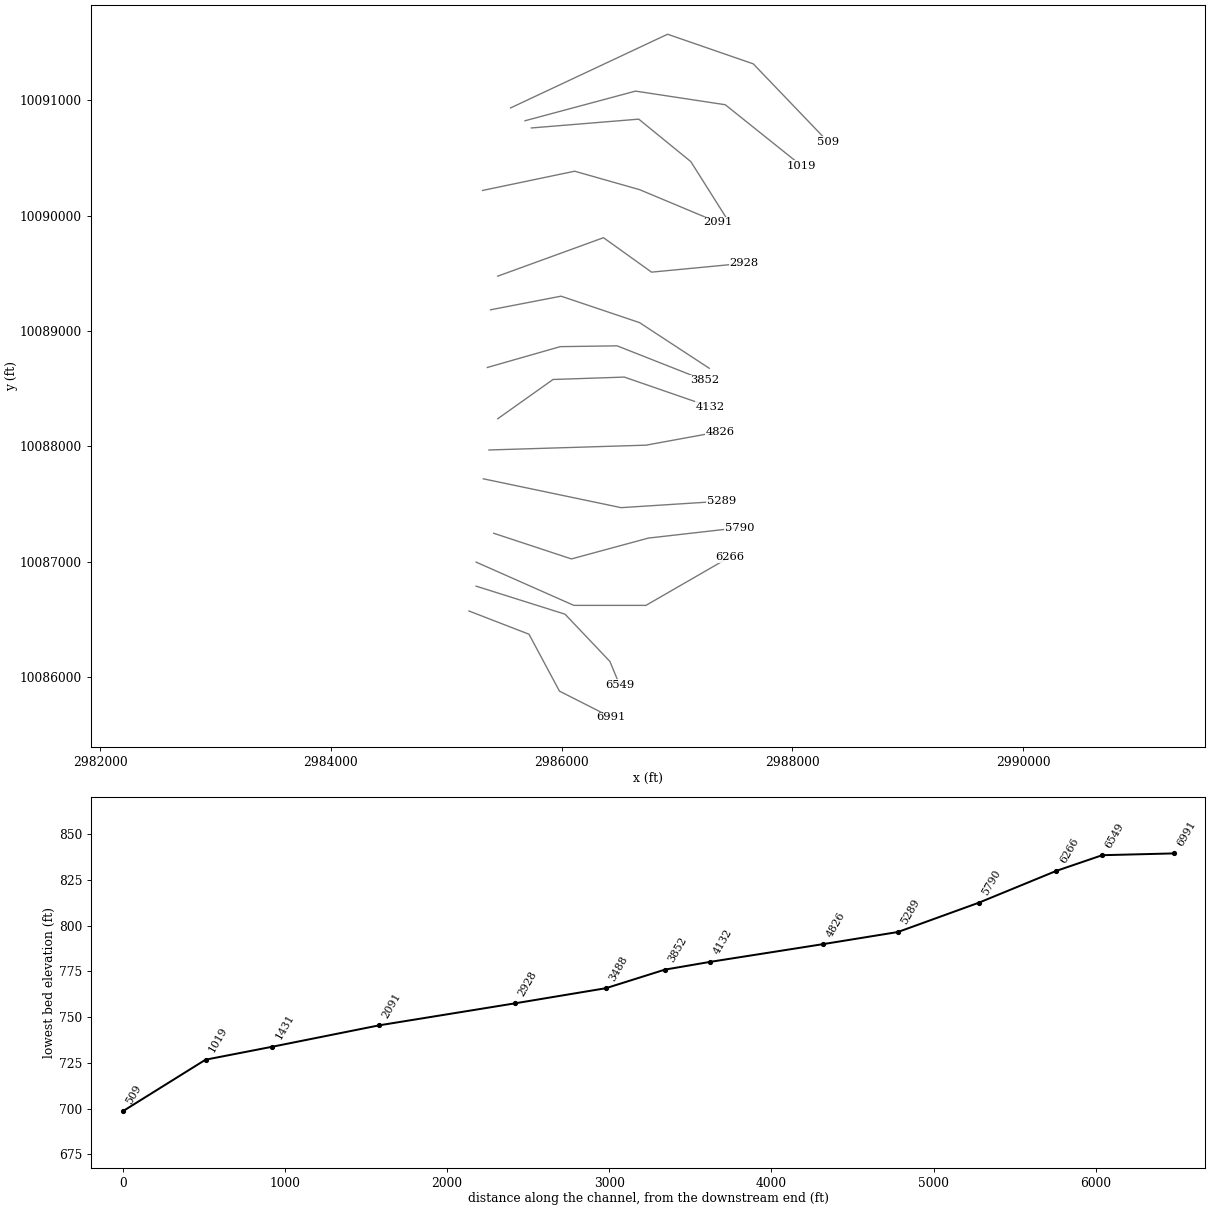
HEC-RAS study ROY CREEK.prj: ROY CREEK Base Level Engineering

--- ROY CREEK.g01 (geometry) --- (continued)

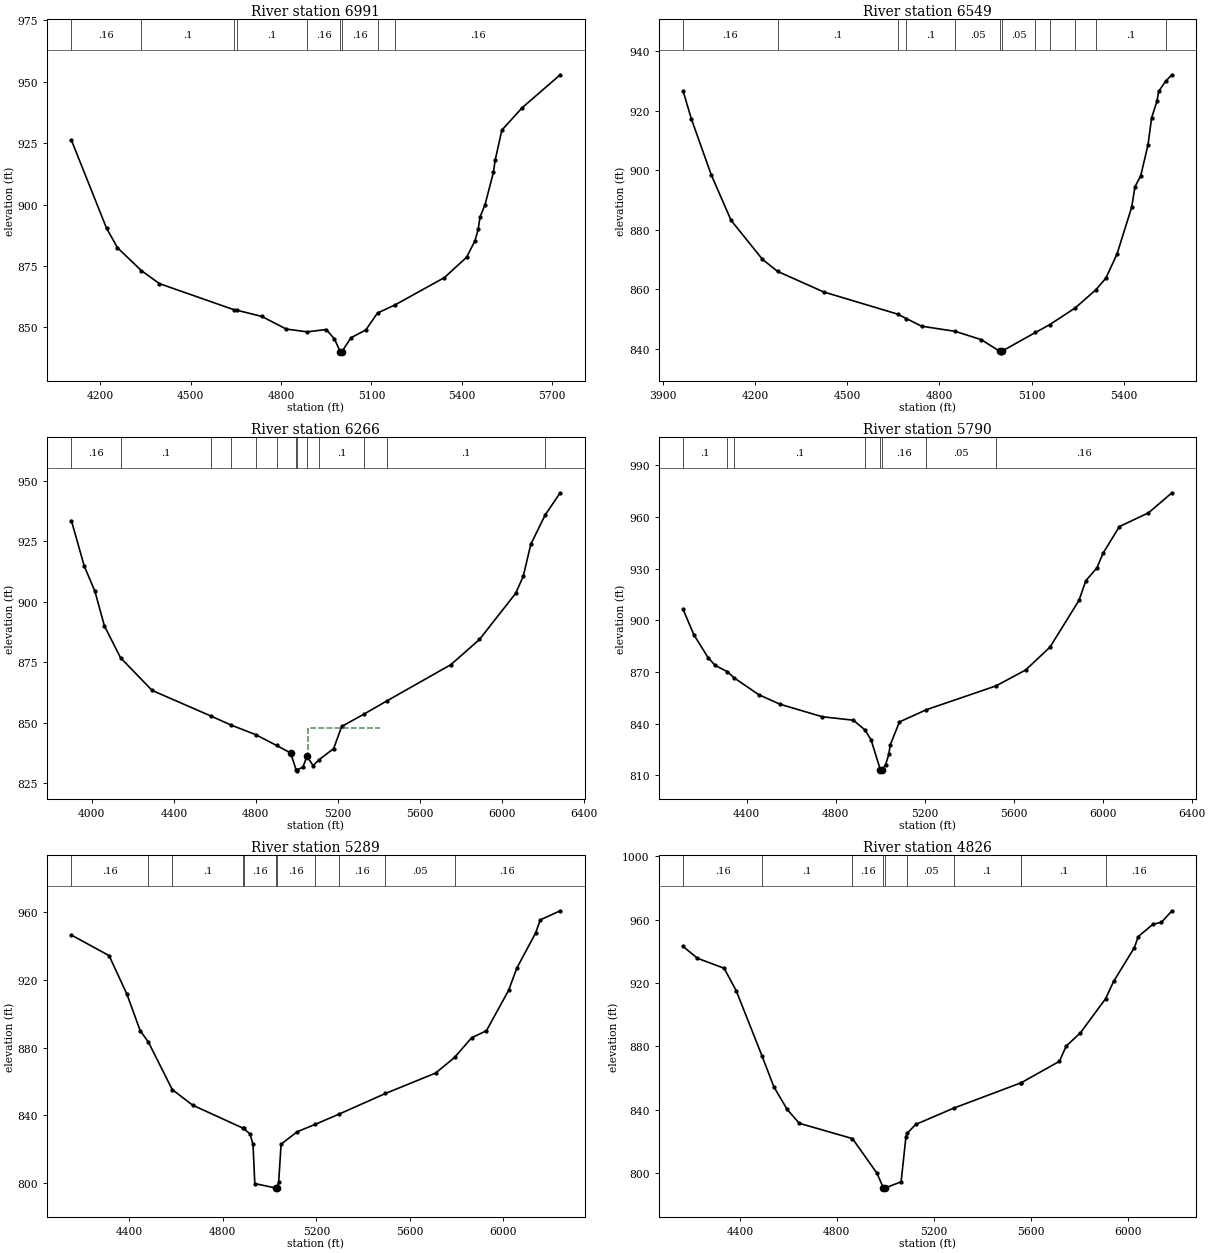
Type RM Length L Ch R = 1 ,6991    ,442,442,442
BEGIN DESCRIPTION:
ROY CREEK 15.0
END DESCRIPTION:
XS GIS Cut Line= 4
      2985195.87     10086571.46      2985716.74     10086370.06
      2985980.63       10085877.      2986431.11      10085648.3
#Sta/Elev= 30
    4104  926.19  4220.9  890.27  4256.9  882.41  4336.3  873.08  4396.3  867.78
  4642.5   857.2  4653.9  856.94  4736.1  854.42  4817.1  849.28  4886.5  848.14
  4949.9  849.09  4977.5  845.23  4996.4  840.09  4999.2  839.59  5002.4  840.09
  5031.9  845.71  5081.5  848.92  5120.4  855.82  5178.1  859.08  5342.6  870.25
  5416.1  878.52    5444  885.25  5454.8  890.04  5460.6  894.92  5477.2  899.87
  5505.1  913.06  5510.9  918.08  5533.3  930.32  5600.6  939.43  5726.9  952.85
#Mann= 9 ,-1 , 0
    4104     .16       0  4336.3      .1       0  4642.5     .16       0
  4653.9      .1       0  4886.5     .16       0  4996.4     .07       0
  5002.4     .16       0  5120.4      .1       0  5178.1     .16       0
Bank Sta=4996.4,5002.4
XS Rating Curve= 0 ,0
Exp/Cntr=0.3,0.1

Type RM Length L Ch R = 1 ,6549    ,283,283,283
BEGIN DESCRIPTION:
ROY CREEK 14.0
END DESCRIPTION:
XS GIS Cut Line= 4
      2985258.37     10086786.74      2986029.24     10086543.67
      2986418.13     10086133.95      2986501.45     10085932.59
#Sta/Elev= 30
  3965.5  926.67    3992   917.4  4056.7  898.58  4121.4  883.21  4223.7  870.07
  4272.8  866.02  4423.1  859.09  4663.3  851.65    4692  850.16  4741.5  847.58
  4851.6  845.83    4936  843.04  4996.5  839.11  4999.3  838.61  5002.5  839.11
  5112.3  845.46  5158.4  848.07  5242.6  853.78  5308.5  859.77  5341.5  863.72
  5377.8  871.83  5425.5  887.57  5436.4  894.52  5454.9  898.14  5478.8  908.59
  5490.4  917.63  5508.1  923.36  5513.5  926.59  5536.4  930.04  5556.6  932.16
#Mann= 12 ,-1 , 0
  3965.5     .16       0  4272.8      .1       0  4663.3     .05       0
    4692      .1       0  4851.6     .05       0  4996.5    .035       0
  5002.5     .05       0  5112.3      .1       0  5158.4     .05       0
  5242.6     .16       0  5308.5      .1       0  5536.4     .16       0
Bank Sta=4996.5,5002.5
XS Rating Curve= 0 ,0
Exp/Cntr=0.3,0.1

Type RM Length L Ch R = 1 ,6266    ,476,476,476
BEGIN DESCRIPTION:
ROY CREEK 13.0
END DESCRIPTION:
XS GIS Cut Line= 4
      2985258.41     10086995.05      2986105.63     10086620.06
      2986730.63     10086620.06      2987452.86     10087036.73
#Sta/Elev= 30
  3900.3   933.6  3962.9  914.83    4015  904.36  4061.5  889.99  4140.2  876.84
    4294  863.33  4580.1  852.76  4680.5  848.94    4800  845.01  4901.5  840.53
  4969.6  837.47  4996.6  830.53  4999.4  830.03  5002.6  830.53  5029.6  831.48
  5049.6  836.01  5051.5  835.79  5079.6  832.18  5108.6  834.62  5179.6   839.2
  5219.6  848.43  5326.6  853.45  5440.9  859.04  5752.3  874.01  5891.6  884.43
  6068.2  903.52  6105.5  910.65    6142  923.82  6212.6  936.03  6285.6  945.17
#Mann= 13 ,-1 , 0
  3900.3     .16       0  4140.2      .1       0  4580.1     .05       0
  4680.5      .1       0    4800     .05       0  4901.5      .1       0
  4996.6     .07       0  5002.6      .1       0  5051.5     .05       0
  5108.6      .1       0  5326.6     .05       0  5440.9      .1       0
  6212.6     .16       0
#XS Ineff= 1 ,-1
 5054.55 5405.68  847.68
Permanent Ineff=
       F
Bank Sta=4969.6,5049.6
XS Rating Curve= 0 ,0
Exp/Cntr=0.3,0.1

Type RM Length L Ch R = 1 ,5790    ,501,501,501
BEGIN DESCRIPTION:
ROY CREEK 12.0
END DESCRIPTION:
XS GIS Cut Line= 4
      2985411.17     10087245.06       2986084.8     10087022.84
      2986751.46     10087203.39      2987543.11     10087293.67
#Sta/Elev= 30
  4114.2  906.31  4162.5   891.6    4226   878.4  4257.8  873.85  4311.6   870.3
  4344.5  866.53  4453.6  856.89  4548.9  851.35  4739.4  844.07  4879.1  842.06
  4930.7  836.48  4958.9  830.68  5000.9  813.19  5003.6  812.69  5006.9  813.19
  5024.2  816.22  5038.5  822.27  5044.9   827.7  5086.3  841.05  5207.1  848.13
  5520.4  861.96  5653.4  871.15  5762.8  884.41  5893.7  911.66  5923.9  922.95
  5974.2  930.46    6001  938.77  6074.8  954.36  6205.7  962.31    6311  973.96
#Mann= 8 ,-1 , 0
  4114.2      .1       0  4311.6     .05       0  4344.5      .1       0
  4930.7     .16       0  5000.9     .07       0  5006.9     .16       0
  5207.1     .05       0  5520.4     .16       0
Bank Sta=5000.9,5006.9
XS Rating Curve= 0 ,0
Exp/Cntr=0.3,0.1

Type RM Length L Ch R = 1 ,5289    ,463,463,463
BEGIN DESCRIPTION:
ROY CREEK 11.0
END DESCRIPTION:
XS GIS Cut Line= 3
      2985320.93     10087717.28      2986515.35     10087467.28
      2987383.37     10087522.83
#Sta/Elev= 30
  4152.6  946.44  4313.6   934.3  4389.9  911.54  4446.4  890.06    4482  883.18
  4583.7  855.21  4671.1  845.99  4885.7  832.46  4888.8  832.23  4916.3  829.01
  4929.1  822.81  4936.8   799.7    5026  797.09  5028.7  796.59    5032  797.09
  5038.9  800.69  5049.2  822.96  5118.7  830.34    5194  834.59  5295.7  840.63
  5495.3  852.89  5710.2  864.97  5791.1  874.19  5863.7  885.77  5927.2  889.94
  6022.1  913.78  6057.4  926.98  6137.6  947.67  6157.6   955.4  6242.7  960.77
#Mann= 11 ,-1 , 0
  4152.6     .16       0    4482     .05       0  4583.7      .1       0
  4885.7     .05       0  4888.8     .16       0    5026     .07       0
    5032     .16       0    5194     .05       0  5295.7     .16       0
  5495.3     .05       0  5791.1     .16       0
Bank Sta=5026,5032
XS Rating Curve= 0 ,0
Exp/Cntr=0.3,0.1

Type RM Length L Ch R = 1 ,4826    ,694,694,694
BEGIN DESCRIPTION:
ROY CREEK 10.0
END DESCRIPTION:
XS GIS Cut Line= 3
      2985369.47     10087967.28      2986730.63     10088008.95
      2987374.96     10088126.73
#Sta/Elev= 30
  4165.9  943.09  4224.9  935.65    4335  929.35    4385   915.1  4490.7   874.2
  4540.1  854.47  4595.1  840.13  4645.1  831.37  4864.6  821.68  4965.3  799.88
  4992.3  790.44    4995  789.94  4998.3  790.44  5065.3  794.37  5085.3  822.98
  5091.4  825.22  5125.3  830.62  5282.4  840.94  5558.7  856.86  5561.7  857.06
  5718.6  870.54  5746.5  880.21  5804.8  888.46  5908.7  910.04  5942.3  921.05
  6027.9  942.41  6043.9   949.4  6104.9  957.19  6139.4  958.36  6182.7  965.66
#Mann= 10 ,-1 , 0
  4165.9     .16       0  4490.7      .1       0  4864.6     .16       0
  4992.3     .07       0  4998.3     .16       0  5091.4     .05       0
  5282.4      .1       0  5558.7     .16       0  5561.7      .1       0
  5908.7     .16       0
Bank Sta=4992.3,4998.3
XS Rating Curve= 0 ,0
Exp/Cntr=0.3,0.1

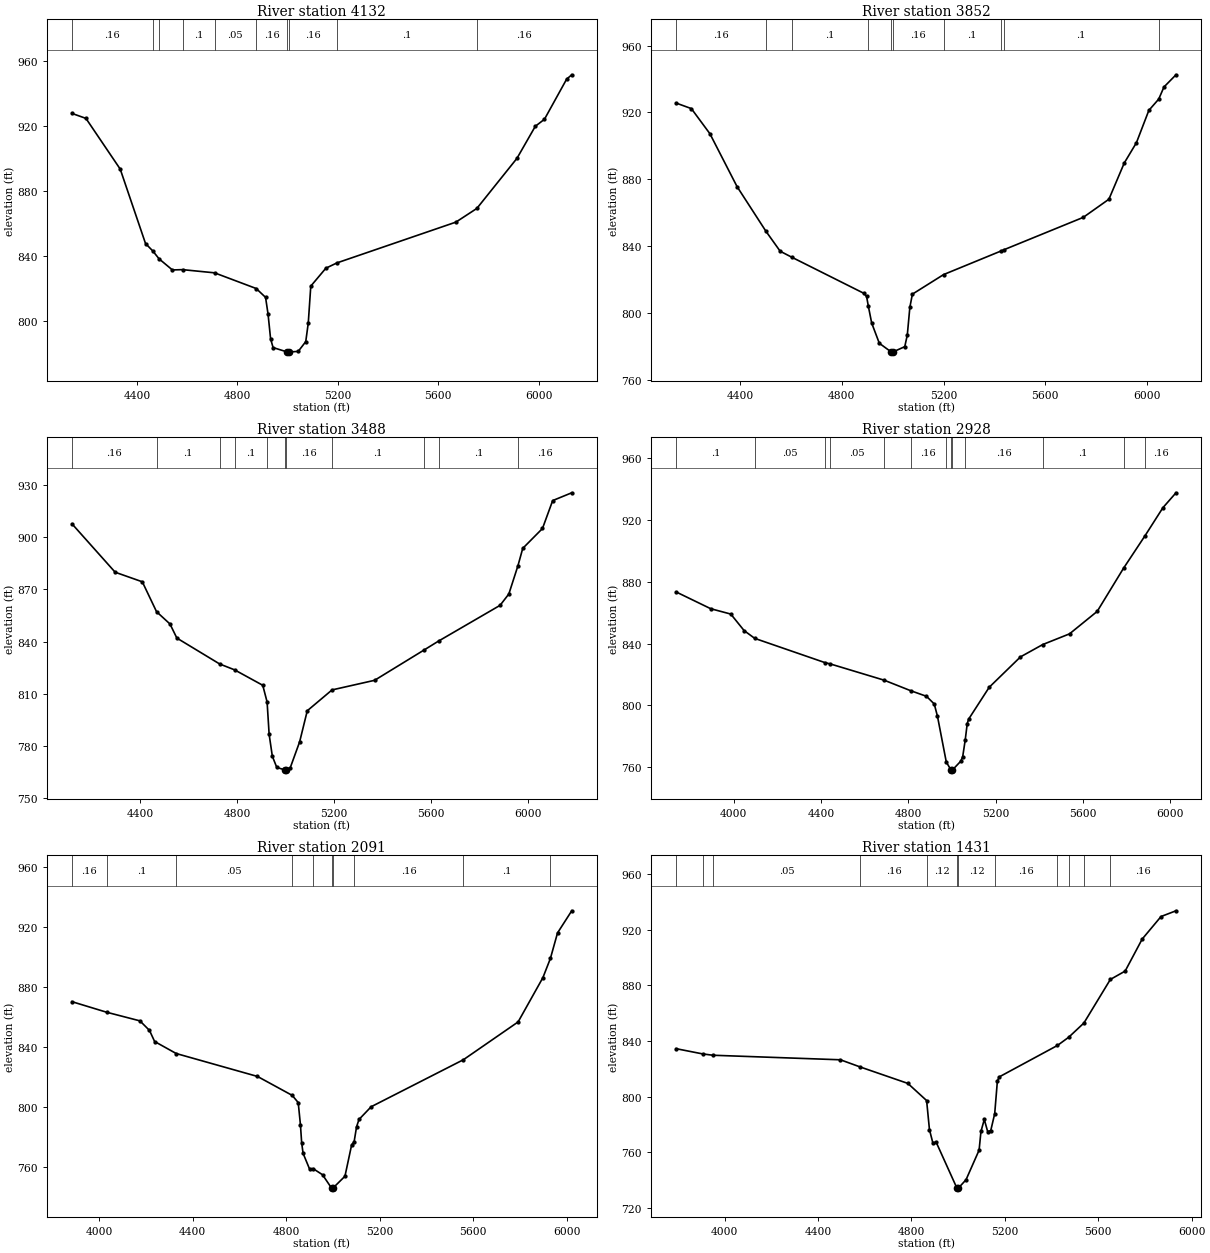
Type RM Length L Ch R = 1 ,4132    ,280,280,280
BEGIN DESCRIPTION:
ROY CREEK 9.0
END DESCRIPTION:
XS GIS Cut Line= 4
      2985445.89      10088238.1      2985925.07     10088578.39
      2986543.13     10088599.22      2987284.81     10088342.75
#Sta/Elev= 30
  4141.2  927.87  4196.8  924.81  4333.4  893.54  4434.2  847.66  4462.9  843.12
  4488.3   838.2  4541.3  831.37  4581.6  831.56    4709   829.6    4875  819.93
  4912.4  814.47  4922.4  804.04  4932.4  788.94  4942.4  783.51  4999.5  780.77
  5002.2  780.27  5005.5  780.77  5042.5  781.17  5072.5  787.19  5082.5  798.61
  5092.5  821.39  5152.6  832.44  5196.8  835.72  5670.4  860.84  5754.1   869.3
  5913.8  900.17    5987  919.94  6023.4  924.27  6111.7  948.99  6132.1  951.69
#Mann= 10 ,-1 , 0
  4141.2     .16       0  4462.9      .1       0  4488.3     .05       0
  4581.6      .1       0    4709     .05       0    4875     .16       0
  4999.5     .07       0  5005.5     .16       0  5196.8      .1       0
  5754.1     .16       0
Bank Sta=4999.5,5005.5
XS Rating Curve= 0 ,0
Exp/Cntr=0.3,0.1

Type RM Length L Ch R = 1 ,3852    ,364,364,364
BEGIN DESCRIPTION:
ROY CREEK 8.0
END DESCRIPTION:
XS GIS Cut Line= 4
      2985355.66     10088682.57      2985987.57     10088863.11
      2986480.63     10088870.06      2987237.56     10088571.45
#Sta/Elev= 30
  4149.6  925.53  4209.1  922.23  4281.9  907.21  4388.5  875.57  4501.6  848.92
  4558.1  836.84    4603  833.31  4887.7  811.59  4897.7  809.74  4904.5  804.01
  4917.7  793.86  4947.7  781.74  4994.7  776.51  4997.5  776.01  5000.7  776.51
  5047.7   779.7  5057.7  786.69  5067.7  803.28  5077.7  811.15  5200.4  822.87
  5424.4  836.88  5436.3  837.66  5749.1  857.11  5849.9  867.97  5910.3  889.68
  5958.1  901.82  6006.9  921.17  6045.6   927.9  6066.4  935.19  6113.6  942.48
#Mann= 10 ,-1 , 0
  4149.6     .16       0  4501.6     .05       0    4603      .1       0
  4904.5     .16       0  4994.7     .07       0  5000.7     .16       0
  5200.4      .1       0  5424.4     .16       0  5436.3      .1       0
  6045.6     .16       0
Bank Sta=4994.7,5000.7
XS Rating Curve= 0 ,0
Exp/Cntr=0.3,0.1

Type RM Length L Ch R = 1 ,3488    ,560,560,560
BEGIN DESCRIPTION:
ROY CREEK 7.0
END DESCRIPTION:
XS GIS Cut Line= 4
      2985383.42     10089182.56      2985994.52     10089300.61
      2986675.07     10089071.45      2987279.25      10088675.6
#Sta/Elev= 30
  4117.8  907.65  4296.1  879.86  4408.1  874.37  4466.9  857.21  4522.3  850.15
  4550.7  842.07  4727.3   827.2    4789  823.82  4905.3  814.96  4923.2  805.36
  4931.6  786.81  4944.8  774.23  4963.1  767.83  4996.8  766.35  4999.6  765.85
  5002.8  766.35  5018.7  767.61  5057.5   782.5    5089  800.34  5191.2   812.3
  5366.9  817.82  5571.6  835.26  5631.1  840.36  5884.8  860.86    5921  867.38
  5958.8  883.72  5978.3  893.54  6059.8  904.97  6101.9  920.99  6180.6  925.47
#Mann= 11 ,-1 , 0
  4117.8     .16       0  4466.9      .1       0  4727.3     .05       0
    4789      .1       0  4923.2     .16       0  4996.8     .07       0
  5002.8     .16       0  5191.2      .1       0  5571.6     .05       0
  5631.1      .1       0  5958.8     .16       0
Bank Sta=4996.8,5002.8
XS Rating Curve= 0 ,0
Exp/Cntr=0.3,0.1

Type RM Length L Ch R = 1 ,2928    ,837,837,837
BEGIN DESCRIPTION:
ROY CREEK 6.0
END DESCRIPTION:
XS GIS Cut Line= 4
      2985445.91     10089474.22      2986362.57     10089807.56
      2986779.24     10089508.95      2987577.89     10089585.34
#Sta/Elev= 30
  3736.6  873.43  3894.9  862.59  3986.6  859.13  4047.9   848.4  4096.5  843.38
  4418.3  827.68  4442.5  826.84  4689.7  816.29  4810.3  809.53  4883.5  805.86
  4919.1  800.88  4933.8  792.91  4974.2  763.32  4995.9  758.08  4998.7  757.58
  5001.9  758.08  5040.7  763.85  5049.3  766.66  5060.7  777.28  5070.2  788.15
  5076.3  791.01  5170.9  811.71  5314.2   831.4  5416.4   839.4  5538.9  846.31
  5665.8  860.87  5786.5  888.83  5885.2  909.92  5967.2  928.09  6026.9   937.7
#Mann= 13 ,-1 , 0
  3736.6      .1       0  4096.5     .05       0  4418.3      .1       0
  4442.5     .05       0  4689.7      .1       0  4810.3     .16       0
  4974.2     .12       0  4995.9     .07       0  5001.9     .12       0
  5060.7     .16       0  5416.4      .1       0  5786.5     .05       0
  5885.2     .16       0
Bank Sta=4995.9,5001.9
XS Rating Curve= 0 ,0
Exp/Cntr=0.3,0.1

Type RM Length L Ch R = 1 ,2091    ,660,660,660
BEGIN DESCRIPTION:
ROY CREEK 4.0
END DESCRIPTION:
XS GIS Cut Line= 4
      2985313.96     10090217.28      2986112.57     10090383.95
      2986675.07     10090224.22      2987354.55     10089939.95
#Sta/Elev= 30
  3883.9  870.12  4031.9  863.11  4174.5  857.35  4215.4  850.99  4237.3  843.62
  4329.8  835.61  4677.2  820.36  4825.8  807.75  4851.4  802.96  4860.9  788.11
  4866.1  776.21  4872.2  769.18    4900   758.7  4914.7  759.04  4955.3  754.94
  4993.9  746.06  4996.7  745.56  4999.9  746.06  5051.2  753.94  5079.9   774.9
  5090.4  776.87  5100.9  786.89  5111.3  791.75  5163.3   800.2  5557.8   831.5
  5791.6  856.64  5897.6   886.1  5929.7  898.89  5960.2  915.88    6021  930.62
#Mann= 10 ,-1 , 0
  3883.9     .16       0  4031.9      .1       0  4329.8     .05       0
  4825.8     .16       0  4914.7     .12       0  4993.9     .07       0
  4999.9     .12       0  5090.4     .16       0  5557.8      .1       0
  5929.7     .16       0
Bank Sta=4993.9,4999.9
XS Rating Curve= 0 ,0
Exp/Cntr=0.3,0.1

Type RM Length L Ch R = 1 ,1431    ,412,412,412
BEGIN DESCRIPTION:
ROY CREEK 3.0
END DESCRIPTION:
XS GIS Cut Line= 4
      2985737.58     10090758.95      2986668.13     10090835.34
      2987119.52     10090467.28      2987452.84     10089939.52
#Sta/Elev= 30
  3792.7  834.44  3905.9   830.7  3949.2  829.75  4495.9  826.48  4581.7  821.26
  4784.6  809.53    4865  797.22  4877.2  776.29  4891.6  766.89  4905.9  767.33
  4994.8  734.34  4997.5  733.84  5000.8  734.34  5033.8  740.37  5089.8  761.63
  5097.7  775.04    5112  783.64  5126.4  774.97  5139.7  775.69  5156.6  787.81
    5168  811.12  5175.9  814.19  5425.3  836.77  5473.4  842.65  5538.6  852.87
  5651.9  884.16  5715.2  890.15  5788.2  913.14  5868.9  929.32    5933  933.45
#Mann= 12 ,-1 , 0
  3792.7     .05       0  3905.9      .1       0  3949.2     .05       0
  4581.7     .16       0    4865     .12       0  4994.8     .07       0
  5000.8     .12       0  5156.6     .16       0  5425.3      .1       0
  5473.4     .05       0  5538.6      .1       0  5651.9     .16       0
Bank Sta=4994.8,5000.8
XS Rating Curve= 0 ,0
Exp/Cntr=0.3,0.1

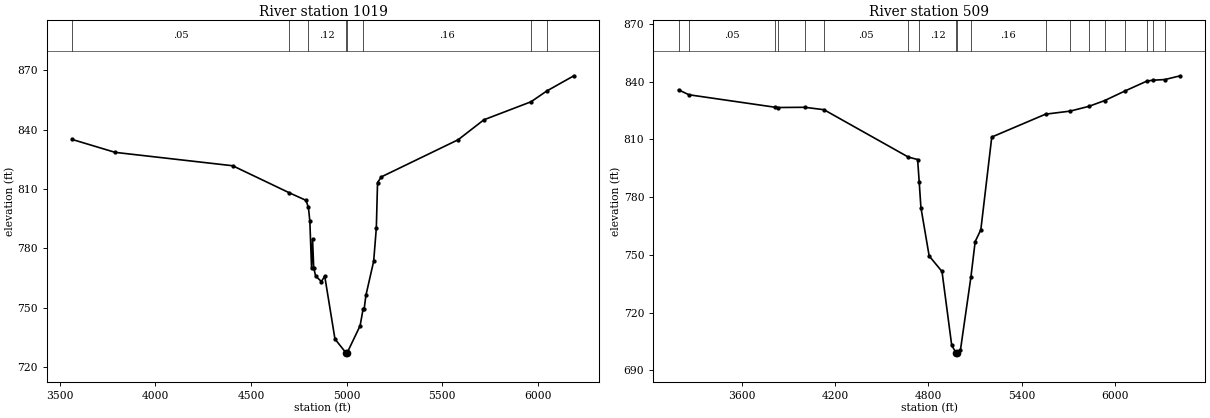
Type RM Length L Ch R = 1 ,1019    ,510,510,510
BEGIN DESCRIPTION:
ROY CREEK 2.0
END DESCRIPTION:
XS GIS Cut Line= 4
        2985682.     10090821.44      2986640.35     10091078.39
      2987418.13     10090960.34      2988077.82     10090432.58
#Sta/Elev= 30
  3564.1  835.06  3789.4  828.52  4403.7  821.76  4699.4  808.12    4787  804.29
  4799.9  800.72  4807.3  793.81  4816.4  769.96  4821.5  784.65  4827.5  770.25
  4837.6  766.02  4867.9  763.26  4885.2  765.98  4938.7  734.22  4996.4  727.24
  4999.2  726.74  5002.4  727.24  5070.2  740.94  5086.2  749.62  5091.3  749.39
  5100.6  756.33    5141   773.5    5155  790.29  5161.3  813.28  5181.5  816.15
    5583  834.91  5717.5  844.98  5963.9  854.08  6045.8   859.5  6187.8  867.21
#Mann= 8 ,-1 , 0
  3564.1     .05       0  4699.4     .16       0  4799.9     .12       0
  4996.4     .07       0  5002.4     .12       0  5086.2     .16       0
  5963.9     .05       0  6045.8     .16       0
Bank Sta=4996.4,5002.4
XS Rating Curve= 0 ,0
Exp/Cntr=0.3,0.1

Type RM Length L Ch R = 1 ,509     ,0,0,0
BEGIN DESCRIPTION:
ROY CREEK 1.0
END DESCRIPTION:
XS GIS Cut Line= 4
      2985556.98     10090932.54      2986918.13     10091571.45
      2987661.19      10091314.5      2988307.05     10090640.86
#Sta/Elev= 30
  3194.6  835.74  3261.6  833.18    3813  826.72  3832.2  826.56  4004.3  826.67
  4128.4  825.43  4671.4  800.77  4730.3  799.54  4740.4  787.97  4751.5  774.55
  4804.4  749.43  4886.9  741.34  4949.3  702.95  4977.5  699.05  4980.2  698.55
  4983.5  699.05  5005.4  700.53  5072.9  738.63  5099.9  756.88  5136.3  763.01
  5206.5  811.21    5552   823.1  5710.2  824.69  5830.8  827.17  5931.2  830.15
  6062.1  835.15  6203.5  840.31  6243.2  840.76  6317.9  841.08  6417.7  843.05
#Mann= 19 ,-1 , 0
  3194.6      .1       0  3261.6     .05       0    3813      .1       0
  3832.2     .05       0  4004.3      .1       0  4128.4     .05       0
  4671.4     .16       0  4740.4     .12       0  4977.5     .07       0
  4983.5     .12       0  5072.9     .16       0    5552      .1       0
  5710.2     .05       0  5830.8      .1       0  5931.2     .05       0
  6062.1     .16       0  6203.5     .05       0  6243.2     .16       0
  6317.9     .05       0
Bank Sta=4977.5,4983.5
XS Rating Curve= 0 ,0
Exp/Cntr=0.3,0.1

Chan Stop Cuts=-1
Use User Specified Reach Order=0
Composite Channel Slope=5