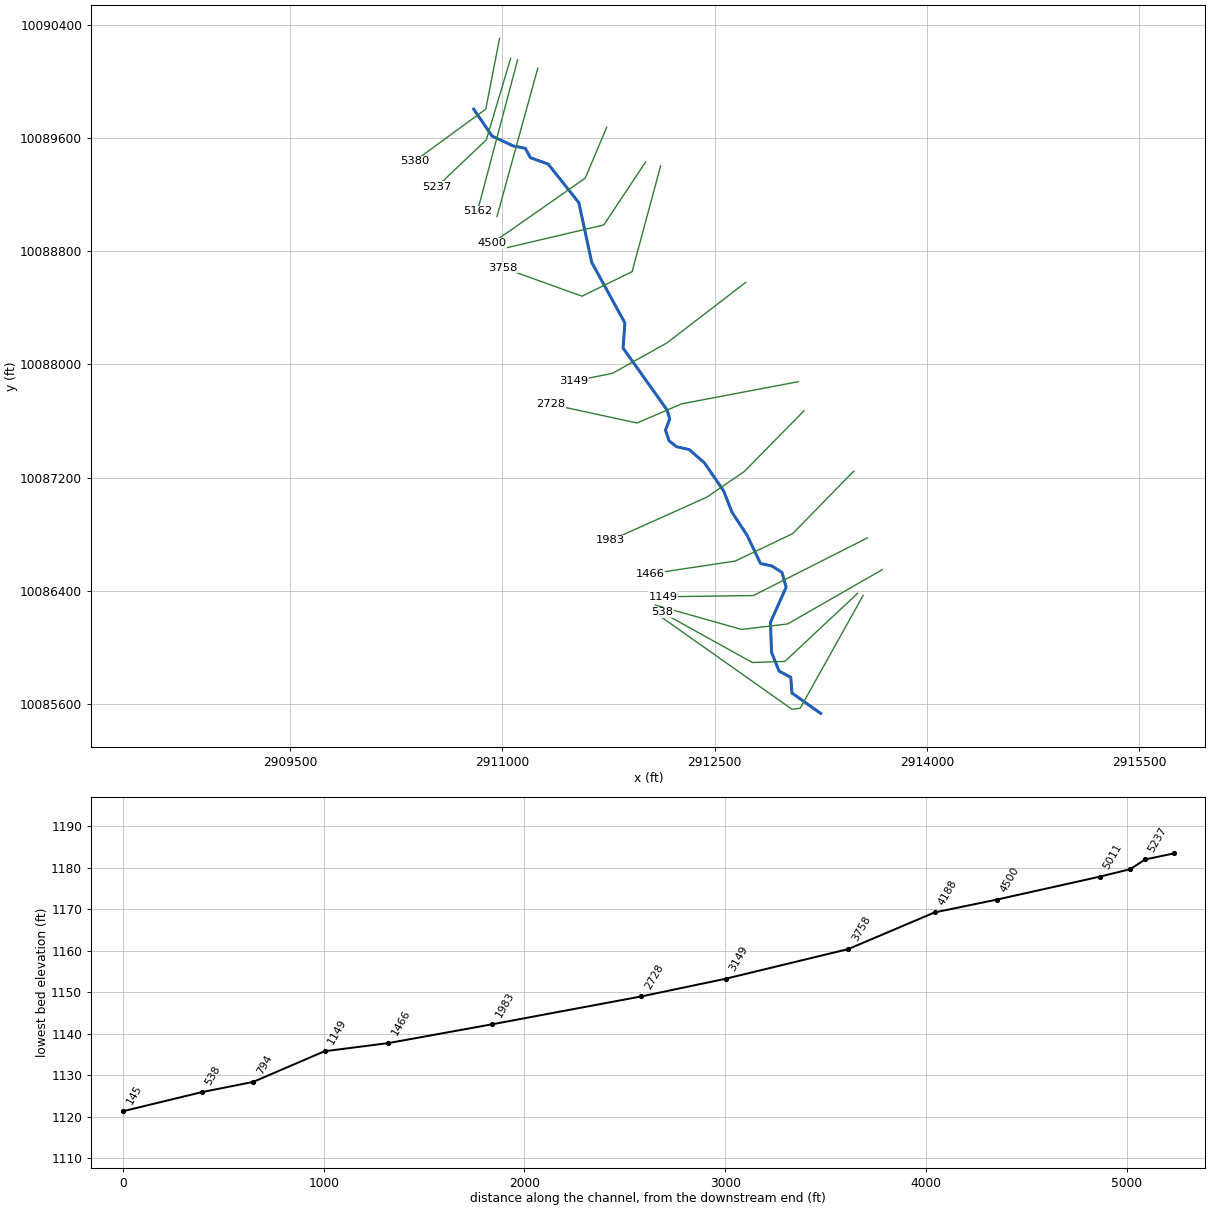
--- SALTER SPRING CREEK.prj (project) ---

Proj Title=SALTER SPRING CREEK Base Level Engineering
Current Plan=p01
Default Exp/Contr=0.3,0.1
English Units
Geom File=g01
Flow File=f01
Plan File=p01
BEGIN DESCRIPTION:
SALTER SPRING CREEK
END DESCRIPTION:

--- SALTER SPRING CREEK.p01 (plan) ---

Plan Title=Multiple Run
Short Identifier=Multiple
Geom File=g01
Flow File=f01
Subcritical Flow
K Sum by GR= 0
Std Step Tol= 0.01
Critical Tol= 0.01
Num of Std Step Trials= 20
Max Error Tol= 0.3
Flow Tol Ratio= 0.001
Split Flow NTrial= 30
Split Flow Tol= 0.02
Split Flow Ratio= 0.02
Log Output Level= 0
Friction Slope Method= 1
Unsteady Friction Slope Method= 2
Unsteady Bridges Friction Slope Method= 1
Parabolic Critical Depth
Global Vel Dist=  1 , 1 , 1
Global Log Level= 0
CheckData=True
Encroach Param= -1, 0, 0, 0
BEGIN DESCRIPTION:
Multiple Run
END DESCRIPTION:

--- SALTER SPRING CREEK.f01 (steady flow) ---

Flow Title=Multiple
Number of Profiles=7
Profile Names=10-year,25-year,50-year,1pct_min,100-year,1pct_plu,500-year
River Rch & RM= SALTER SPRING CR,Reach-1,5380
     770    1105    1394    1288    1742    2355    2728
River Rch & RM= SALTER SPRING CR,Reach-1,5011
    1043    1520    1936    1804    2440    3300    3890
Boundary for River Rch & Prof#=SALTER SPRING CR,Reach-1,1
Up Type=0
Dn Type=3
Dn Slope=0.005
Boundary for River Rch & Prof#=SALTER SPRING CR,Reach-1,2
Up Type=0
Dn Type=3
Dn Slope=0.005
Boundary for River Rch & Prof#=SALTER SPRING CR,Reach-1,3
Up Type=0
Dn Type=3
Dn Slope=0.005
Boundary for River Rch & Prof#=SALTER SPRING CR,Reach-1,4
Up Type=0
Dn Type=3
Dn Slope=0.005
Boundary for River Rch & Prof#=SALTER SPRING CR,Reach-1,5
Up Type=0
Dn Type=3
Dn Slope=0.005
Boundary for River Rch & Prof#=SALTER SPRING CR,Reach-1,6
Up Type=0
Dn Type=3
Dn Slope=0.005
Boundary for River Rch & Prof#=SALTER SPRING CR,Reach-1,7
Up Type=0
Dn Type=3
Dn Slope=0.005

--- SALTER SPRING CREEK.g01 (geometry) ---

Geom Title=Existing Conditions
Program Version=4.10

River Reach=SALTER SPRING CR,Reach-1
Reach XY= 30
      2910797.08     10089803.22       2910926.8      10089613.1
      2911078.05     10089542.77      2911161.86     10089526.56
      2911197.71     10089460.29        2911323.     10089415.02
      2911539.92     10089142.89       2911631.4     10088719.77
      2911865.39     10088292.47      2911852.44     10088115.13
      2912164.01     10087676.54      2912182.41     10087614.04
      2912152.12     10087534.46      2912177.26     10087460.44
      2912229.95     10087418.05      2912319.77     10087397.99
      2912427.48     10087303.97      2912562.95     10087106.16
      2912622.14     10086954.84      2912728.78      10086792.2
       2912823.5      10086593.3      2912905.27      10086574.6
      2912975.48     10086529.72      2913004.63     10086424.44
      2912894.05     10086177.72      2912901.63     10085965.06
      2912954.54      10085832.6      2913037.56       10085789.
      2913045.68     10085677.42      2913248.47     10085533.73

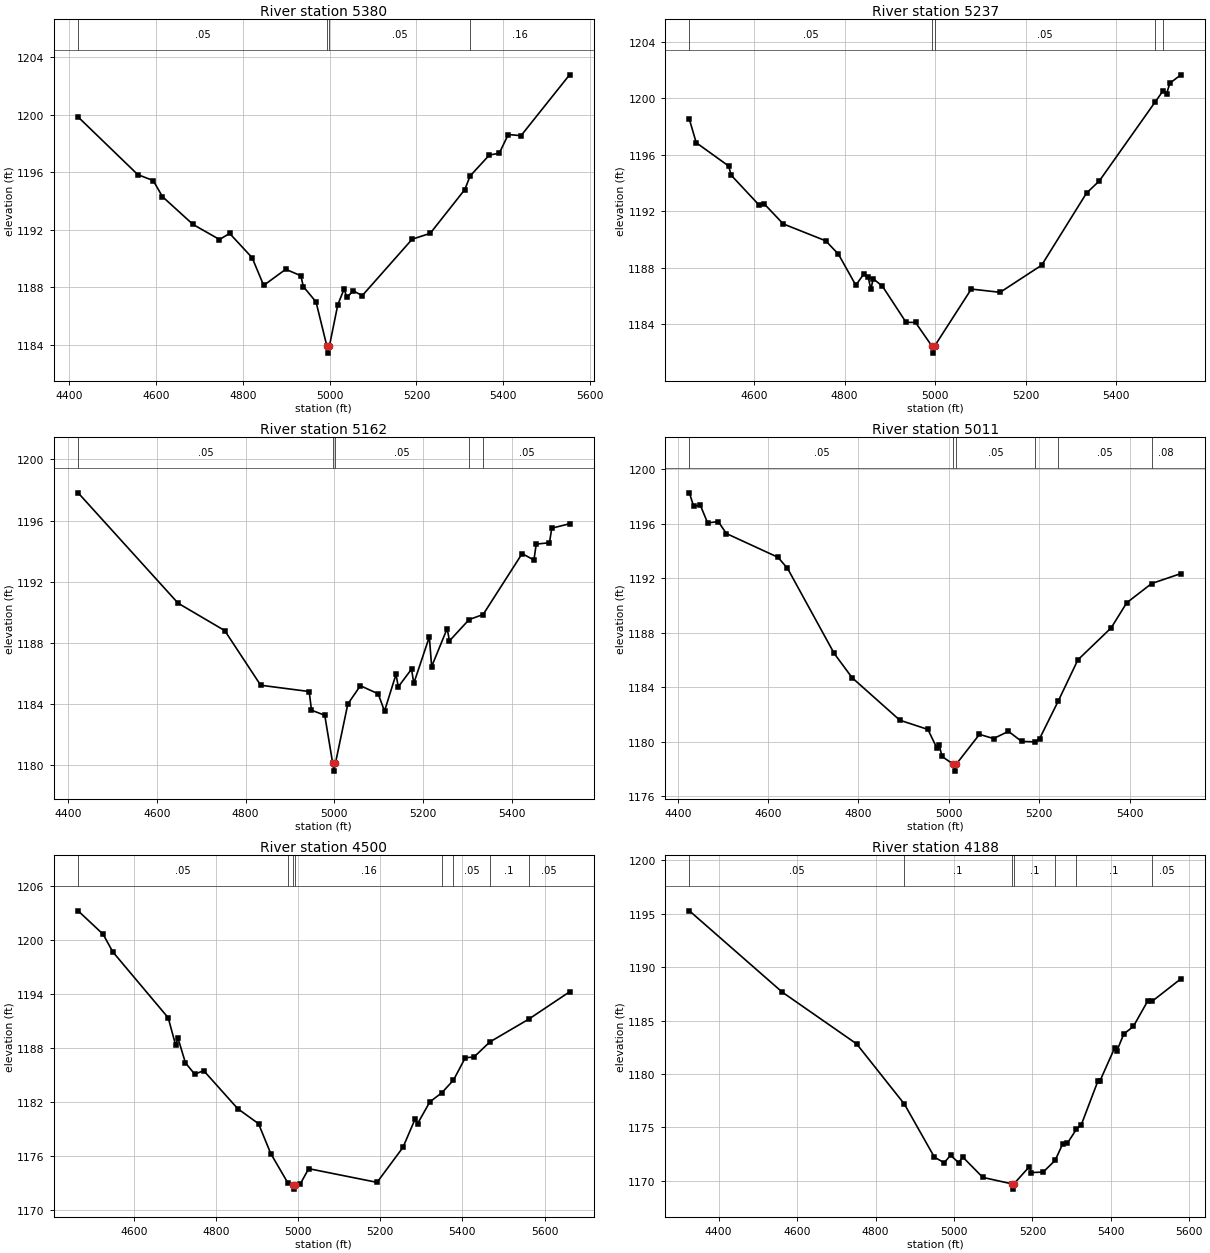
Type RM Length L Ch R = 1 ,5380    ,143,143,143
BEGIN DESCRIPTION:
SALTER SPRING CREEK 10.0
END DESCRIPTION:
XS GIS Cut Line= 3
      2910979.78     10090303.64      2910882.55     10089803.61
      2910379.12     10089435.59
#Sta/Elev= 30
  4419.9 1199.85  4557.5 1195.84    4593 1195.43  4614.3 1194.31  4684.7 1192.38
  4745.8 1191.33  4769.3 1191.75    4821 1190.07  4847.7 1188.14  4898.6 1189.26
  4933.4 1188.81  4939.1 1188.06  4968.4 1186.99  4993.3 1183.93    4996 1183.43
  4999.3 1183.93  5018.6  1186.8  5033.2 1187.89  5039.4  1187.3  5054.1 1187.76
    5075 1187.43    5190 1191.35  5231.7 1191.76  5311.3  1194.8  5323.7 1195.75
  5367.9  1197.2  5390.8 1197.33  5411.6 1198.63    5441 1198.55  5552.9 1202.78
#Mann= 4 ,-1 , 0
  4419.9     .05       0  4993.3     .04       0  4999.3     .05       0
  5323.7     .16       0
Bank Sta=4993.3,4999.3
XS Rating Curve= 0 ,0
Exp/Cntr=0.3,0.1

Type RM Length L Ch R = 1 ,5237    ,75,75,75
BEGIN DESCRIPTION:
Mapping XS 382c574b
END DESCRIPTION:
XS GIS Cut Line= 3
      2911058.09     10090162.22      2910886.64      10089587.1
      2910535.07      10089252.9
#Sta/Elev= 30
  4457.3  1198.5  4472.4 1196.85    4544  1195.2  4549.6 1194.55  4610.3 1192.47
  4622.7 1192.52  4664.4 1191.11  4758.5 1189.91  4786.5 1188.96  4824.8 1186.77
  4841.8 1187.54  4852.2 1187.33    4858 1186.49  4863.2 1187.23  4883.6  1186.7
  4935.7 1184.15  4956.6 1184.14  4992.8 1182.47  4995.6 1181.97  4998.8 1182.47
  5079.8  1186.5  5143.4 1186.27  5235.2 1188.19  5334.3 1193.29  5362.6 1194.15
    5486 1199.74  5503.7 1200.54  5511.1 1200.32  5518.3 1201.06  5542.5 1201.65
#Mann= 5 ,-1 , 0
  4457.3     .05       0  4992.8     .04       0  4998.8     .05       0
    5486     .16       0  5503.7      .1       0
Bank Sta=4992.8,4998.8
XS Rating Curve= 0 ,0
Exp/Cntr=0.3,0.1

Type RM Length L Ch R = 1 ,5162    ,151,151,151
BEGIN DESCRIPTION:
SALTER SPRING CREEK 9.0
END DESCRIPTION:
XS GIS Cut Line= 2
      2911107.38     10090151.72      2910823.06      10089080.3
#Sta/Elev= 30
  4422.3 1197.81  4647.8  1190.6    4753 1188.81  4834.1 1185.24  4943.5 1184.83
  4948.7 1183.61  4978.6 1183.28  4996.6 1180.13  4999.3 1179.63  5002.6 1180.13
  5030.6 1184.01  5058.9 1185.21  5099.1 1184.68  5113.4 1183.55  5139.3 1185.95
  5144.5 1185.14  5174.3 1186.29  5179.5 1185.37  5214.5  1188.4  5219.7 1186.46
  5254.7 1188.94  5259.9 1188.14  5304.2 1189.53  5335.8 1189.86  5423.8 1193.84
  5450.4 1193.42  5455.6 1194.46  5485.5 1194.55  5490.6  1195.5  5530.8 1195.79
#Mann= 5 ,-1 , 0
  4422.3     .05       0  4996.6     .04       0  5002.6     .05       0
  5304.2     .08       0  5335.8     .05       0
Bank Sta=4996.6,5002.6
XS Rating Curve= 0 ,0
Exp/Cntr=0.3,0.1

Type RM Length L Ch R = 1 ,5011    ,511,511,511
BEGIN DESCRIPTION:
SALTER SPRING CREEK 8.0
END DESCRIPTION:
XS GIS Cut Line= 2
      2911249.74     10090092.66      2910961.54     10089044.05
#Sta/Elev= 30
  4425.8 1198.26  4435.1 1197.28    4450 1197.35  4466.2 1196.05  4489.6 1196.15
  4507.7 1195.27  4621.7 1193.53  4642.9 1192.72  4746.2 1186.47  4785.8 1184.69
  4891.4 1181.57  4953.6 1180.89  4973.5 1179.52  4978.6 1179.76  4984.7 1178.91
  5010.1 1178.33  5012.8 1177.83  5016.1 1178.33  5067.7 1180.53  5098.8 1180.22
  5131.9 1180.75    5161 1180.01  5189.8 1179.98  5200.7 1180.21  5241.8 1182.96
  5285.5    1186  5359.2 1188.35  5393.6 1190.19  5448.6  1191.6  5513.3 1192.33
#Mann= 6 ,-1 , 0
  4425.8     .05       0  5010.1     .04       0  5016.1     .05       0
  5189.8     .08       0  5241.8     .05       0  5448.6     .08       0
Bank Sta=5010.1,5016.1
XS Rating Curve= 0 ,0
Exp/Cntr=0.3,0.1

Type RM Length L Ch R = 1 ,4500    ,312,312,312
BEGIN DESCRIPTION:
Mapping XS 9f2a61dc
END DESCRIPTION:
XS GIS Cut Line= 3
      2911737.01     10089675.15      2911584.99     10089315.83
      2910924.35     10088854.21
#Sta/Elev= 30
  4464.7  1203.2  4525.5  1200.6  4549.2 1198.64    4684 1191.33  4702.2 1188.27
  4707.7 1189.08  4725.9 1186.33  4748.6 1185.07  4770.3 1185.47  4853.3 1181.24
  4903.8 1179.58  4933.5 1176.27  4975.9 1172.95  4987.2 1172.82  4989.9 1172.32
  4993.2 1172.82    5005 1172.86  5025.9 1174.59  5192.2 1173.07  5255.3 1176.95
    5285 1180.11  5291.1  1179.6  5320.7    1182  5349.9 1183.01  5378.3 1184.42
  5407.1 1186.91    5428 1186.97  5466.8 1188.65  5561.1 1191.17  5660.8 1194.21
#Mann= 8 ,-1 , 0
  4464.7     .05       0  4975.9     .16       0  4987.2     .07       0
  4993.2     .16       0  5349.9      .1       0  5378.3     .05       0
  5466.8      .1       0  5561.1     .05       0
Bank Sta=4987.2,4993.2
XS Rating Curve= 0 ,0
Exp/Cntr=0.3,0.1

Type RM Length L Ch R = 1 ,4188    ,430,430,430
BEGIN DESCRIPTION:
Mapping XS fe905266
END DESCRIPTION:
XS GIS Cut Line= 3
      2912011.74     10089430.15      2911716.14     10088984.81
      2911016.95     10088820.75
#Sta/Elev= 30
  4325.6 1195.27  4562.5 1187.65  4751.9 1182.81  4873.7 1177.17  4950.2  1172.2
  4975.1 1171.68  4991.3 1172.38  5011.8 1171.69  5022.6 1172.21  5073.4 1170.31
  5146.9 1169.71  5149.7 1169.21  5152.9 1169.71  5192.4 1171.32  5197.5 1170.76
  5227.5 1170.81  5257.8  1171.9  5277.2 1173.45  5289.1 1173.51  5312.2 1174.82
  5324.8 1175.26  5367.2 1179.36  5372.4 1179.36  5409.7 1182.44  5414.8 1182.12
  5432.9 1183.74  5457.2 1184.44  5494.5 1186.87  5504.4 1186.78  5578.3  1188.9
#Mann= 7 ,-1 , 0
  4325.6     .05       0  4873.7      .1       0  5146.9     .07       0
  5152.9      .1       0  5257.8     .05       0  5312.2      .1       0
  5504.4     .05       0
Bank Sta=5146.9,5152.9
XS Rating Curve= 0 ,0
Exp/Cntr=0.3,0.1

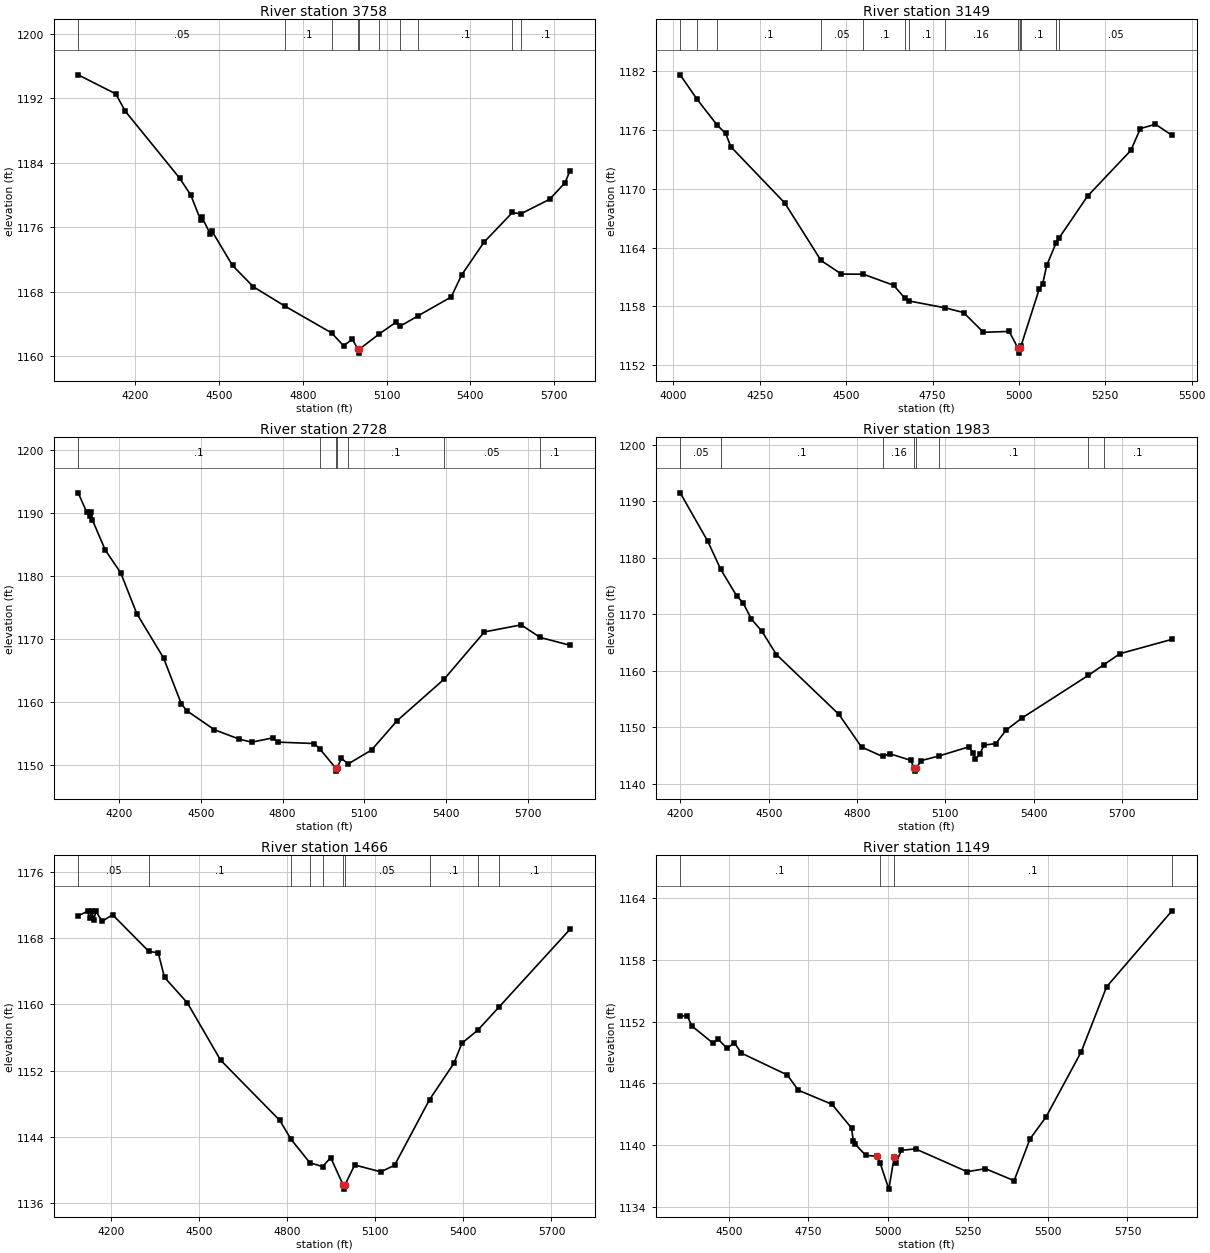
Type RM Length L Ch R = 1 ,3758    ,609,609,609
BEGIN DESCRIPTION:
SALTER SPRING CREEK 7.0
END DESCRIPTION:
XS GIS Cut Line= 4
      2912117.78     10089401.66       2911916.4     10088655.17
      2911562.24     10088481.56       2911003.3     10088682.92
#Sta/Elev= 30
  3995.2 1194.89  4129.9 1192.53  4164.7 1190.35    4359 1182.07  4398.9 1179.97
  4433.7  1176.9  4438.9 1177.24  4468.4 1175.14  4473.6 1175.57  4548.2 1171.25
  4622.9 1168.61  4735.4 1166.22  4903.1 1162.89  4945.9  1161.3  4977.7 1162.11
  4996.9 1160.88  4999.7 1160.38  5002.9 1160.88  5072.7 1162.73  5133.6 1164.21
  5147.4 1163.69  5214.1 1165.03  5331.5 1167.34  5368.8 1170.06    5449 1174.13
  5550.9 1177.82  5580.8 1177.65  5683.9 1179.45    5740 1181.53  5756.9 1183.01
#Mann= 10 ,-1 , 0
  3995.2     .05       0  4735.4      .1       0  4903.1     .16       0
  4996.9     .07       0  5002.9     .16       0  5072.7      .1       0
  5147.4     .05       0  5214.1      .1       0  5550.9     .05       0
  5580.8      .1       0
Bank Sta=4996.9,5002.9
XS Rating Curve= 0 ,0
Exp/Cntr=0.3,0.1

Type RM Length L Ch R = 1 ,3149    ,421,421,421
BEGIN DESCRIPTION:
SALTER SPRING CREEK 6.0
END DESCRIPTION:
XS GIS Cut Line= 4
       2912718.5      10088578.8      2912162.93      10088151.7
      2911777.52     10087936.42      2911501.61     10087881.24
#Sta/Elev= 30
  4019.4 1181.58  4067.9 1179.11  4127.2 1176.43  4151.3 1175.61  4165.8 1174.27
  4322.2 1168.53  4427.1 1162.68  4486.1  1161.3  4549.9 1161.28  4637.1 1160.16
  4670.4 1158.82  4681.7 1158.56    4785 1157.87  4839.8 1157.38  4897.1 1155.37
  4971.9 1155.46  4997.2 1153.75  4999.9 1153.25  5003.2 1153.75  5005.8 1153.95
  5058.8 1159.78  5068.9 1160.33  5080.5 1162.19  5107.6 1164.47  5116.2 1164.97
  5198.6 1169.23  5323.8 1173.88  5351.6 1176.11  5395.2 1176.55    5443 1175.42
#Mann= 13 ,-1 , 0
  4019.4      .1       0  4067.9     .16       0  4127.2      .1       0
  4427.1     .05       0  4549.9      .1       0  4670.4     .05       0
  4681.7      .1       0    4785     .16       0  4997.2     .07       0
  5003.2     .16       0  5005.8      .1       0  5107.6     .16       0
  5116.2     .05       0
Bank Sta=4997.2,5003.2
XS Rating Curve= 0 ,0
Exp/Cntr=0.3,0.1

Type RM Length L Ch R = 1 ,2728    ,745,745,745
BEGIN DESCRIPTION:
SALTER SPRING CREEK 4.0
END DESCRIPTION:
XS GIS Cut Line= 4
      2913090.03      10087877.4       2912267.1     10087721.15
      2911951.13     10087585.73      2911341.77      10087717.3
#Sta/Elev= 30
    4050 1193.24  4082.1 1190.12  4091.8 1189.52  4096.9 1190.26  4102.5 1188.91
  4149.2 1184.17  4206.5 1180.49  4265.3 1174.02  4363.3    1167  4428.2 1159.73
  4448.6 1158.59  4550.3 1155.56    4642 1154.06    4687 1153.58  4764.1 1154.27
  4784.5 1153.59  4916.2 1153.37  4935.8 1152.57  4994.8 1149.48  4997.6 1148.98
  5000.8 1149.48    5016 1151.01  5041.2 1150.13  5126.6 1152.33  5220.9 1157.01
    5393  1163.6    5541 1171.12  5675.6 1172.24  5745.8 1170.24  5854.8    1169
#Mann= 7 ,-1 , 0
    4050      .1       0  4935.8     .16       0  4994.8     .07       0
  5000.8     .16       0  5041.2      .1       0    5393     .05       0
  5745.8      .1       0
Bank Sta=4994.8,5000.8
XS Rating Curve= 0 ,0
Exp/Cntr=0.3,0.1

Type RM Length L Ch R = 1 ,1983    ,517,517,517
BEGIN DESCRIPTION:
SALTER SPRING CREEK 3.0
END DESCRIPTION:
XS GIS Cut Line= 4
      2913131.66     10087672.51      2912708.07     10087241.98
      2912444.18     10087061.42      2911763.64     10086755.88
#Sta/Elev= 30
  4199.4 1191.48  4292.7 1182.95  4337.2 1177.93  4391.8 1173.21  4412.9 1172.03
  4441.2 1169.14  4476.6 1167.01  4526.1 1162.88  4738.2  1152.3  4815.1 1146.51
  4886.8 1144.84  4910.6 1145.33  4982.4 1144.16  4993.8 1142.75  4996.5 1142.25
  4999.8 1142.75  5018.3 1144.12    5077 1144.91  5178.6 1146.53  5195.2 1145.46
  5201.8 1144.36  5217.1 1145.23  5230.4 1146.84  5271.3 1147.13  5305.4 1149.48
  5359.6 1151.64  5584.5 1159.17  5638.8 1161.11  5692.6 1163.03  5869.1 1165.56
#Mann= 8 ,-1 , 0
  4199.4     .05       0  4337.2      .1       0  4886.8     .16       0
  4993.8     .07       0  4999.8     .16       0    5077      .1       0
  5584.5     .05       0  5638.8      .1       0
Bank Sta=4993.8,4999.8
XS Rating Curve= 0 ,0
Exp/Cntr=0.3,0.1

Type RM Length L Ch R = 1 ,1466    ,317,317,317
BEGIN DESCRIPTION:
SALTER SPRING CREEK 2.0
END DESCRIPTION:
XS GIS Cut Line= 4
      2913482.36     10087245.43      2913051.82     10086804.48
      2912645.57     10086610.04      2912044.89     10086519.76
#Sta/Elev= 30
  4088.8  1170.7    4121 1171.24  4128.1 1170.39  4135.1  1171.3  4142.3 1170.25
  4149.3 1171.23  4170.6 1170.03  4205.9 1170.83  4329.4 1166.41  4361.4 1166.23
  4382.8 1163.27  4460.5  1160.2  4573.6 1153.29  4775.3 1146.01  4813.6 1143.73
  4877.7  1140.9  4920.8 1140.44  4948.6 1141.52  4990.9 1138.22  4993.7 1137.72
  4996.9 1138.22  5030.3 1140.63    5119 1139.81    5166  1140.6    5285 1148.52
    5368 1152.91  5395.2 1155.33  5448.9 1156.89  5521.5 1159.69  5762.9 1169.06
#Mann= 10 ,-1 , 0
  4088.8     .05       0  4329.4      .1       0  4813.6     .05       0
  4877.7      .1       0  4920.8     .05       0  4990.9     .04       0
  4996.9     .05       0    5285      .1       0  5448.9     .05       0
  5521.5      .1       0
Bank Sta=4990.9,4996.9
XS Rating Curve= 0 ,0
Exp/Cntr=0.3,0.1

Type RM Length L Ch R = 1 ,1149    ,355,355,355
BEGIN DESCRIPTION:
Mapping XS 260b2de5
END DESCRIPTION:
XS GIS Cut Line= 3
      2913578.38     10086773.44      2912773.23     10086366.39
      2912133.59     10086357.45
#Sta/Elev= 30
  4347.7 1152.51    4370 1152.58  4383.6 1151.59  4450.4 1149.91  4467.1 1150.28
    4495 1149.39  4517.3 1149.96  4539.6 1148.94  4683.8 1146.82  4717.9 1145.35
  4823.7 1143.98    4885 1141.68  4890.6 1140.43  4896.7 1140.11  4929.5 1139.03
  4963.9 1138.95  4974.1 1138.34  5001.8 1135.76  5018.7 1138.84  5024.3 1138.26
    5041 1139.52  5085.6 1139.66  5247.2 1137.45  5304.7 1137.74  5394.7 1136.58
  5444.7 1140.63  5494.7 1142.75  5604.7 1149.04  5684.7 1155.37  5889.6 1162.73
#Mann= 4 ,-1 , 0
  4347.7      .1       0  4974.1     .05       0  5018.7      .1       0
  5889.6     .05       0
Bank Sta=4963.9,5018.7
XS Rating Curve= 0 ,0
Exp/Cntr=0.3,0.1

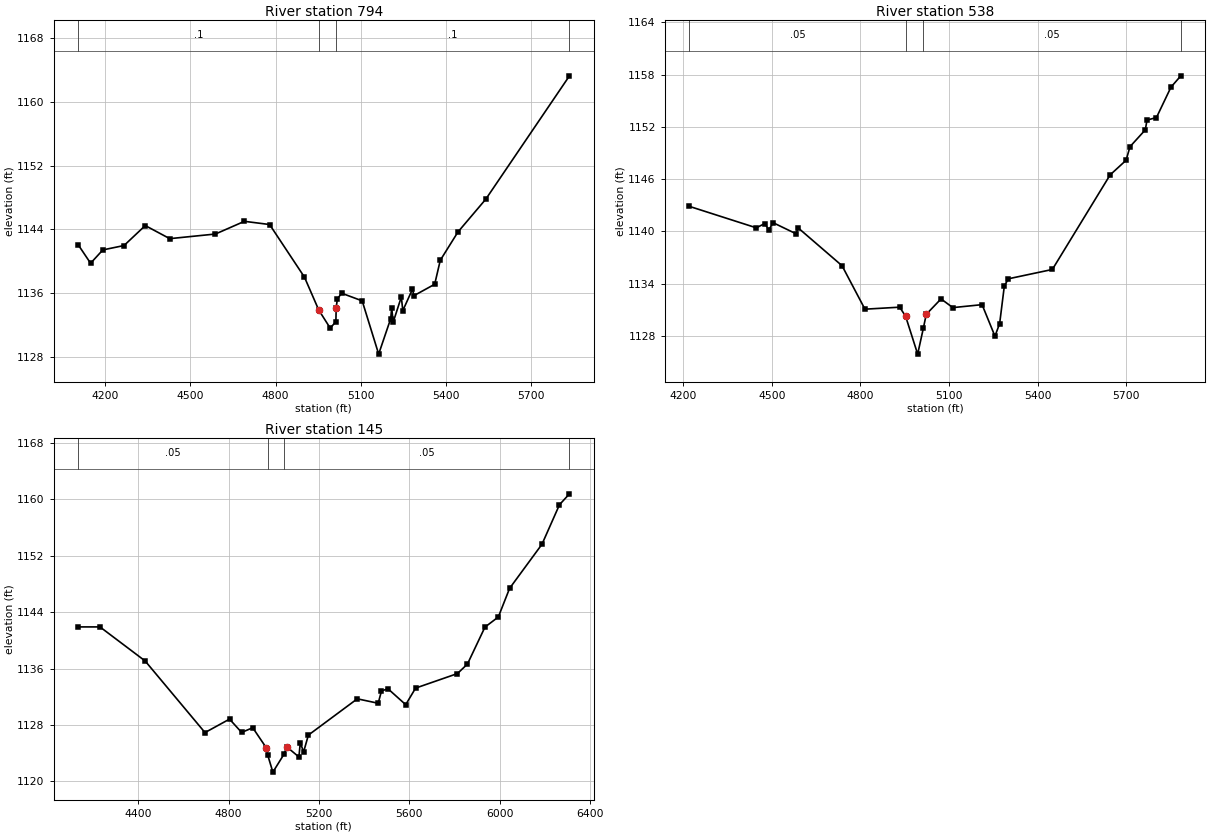
Type RM Length L Ch R = 1 ,794     ,256,256,256
BEGIN DESCRIPTION:
Mapping XS 02e15ee7
END DESCRIPTION:
XS GIS Cut Line= 4
      2913684.08     10086549.26      2913015.31      10086165.6
      2912689.71     10086126.88      2912080.15     10086299.04
#Sta/Elev= 30
  4103.9 1142.09  4147.9 1139.76  4191.1 1141.43  4265.9 1141.98  4340.6 1144.48
    4427 1142.84    4588 1143.42  4690.2 1145.01    4779 1144.61  4901.9 1138.02
  4952.3  1133.9  4992.6 1131.64  5012.7 1132.44  5013.7 1134.17  5017.8 1135.28
  5032.8 1136.01  5105.4 1135.05  5163.5 1128.38    5206 1132.83  5209.4 1134.19
  5214.6 1132.37  5243.4 1135.54  5248.6 1133.83  5282.6  1136.5  5287.8  1135.7
    5361 1137.13  5380.7 1140.13  5443.1 1143.68  5541.3 1147.79  5836.2 1163.23
#Mann= 4 ,-1 , 0
  4103.9      .1       0  4952.3     .05       0  5012.7      .1       0
  5836.2      .1       0
Bank Sta=4952.3,5013.7
XS Rating Curve= 0 ,0
Exp/Cntr=0.3,0.1

Type RM Length L Ch R = 1 ,538     ,393,393,393
BEGIN DESCRIPTION:
Mapping XS 30c5cfcc
END DESCRIPTION:
XS GIS Cut Line= 4
      2913510.05     10086382.26      2912995.84     10085900.91
      2912765.81     10085893.18      2912127.93     10086246.91
#Sta/Elev= 30
  4221.4 1142.87  4447.8 1140.41  4476.1  1140.9  4490.3 1140.18  4504.5    1141
  4582.1 1139.73  4589.5  1140.4    4738 1136.06  4815.6 1131.07  4933.1  1131.3
  4953.1 1130.27  4994.1 1125.91  5013.2 1128.86  5023.2 1130.48  5073.2 1132.25
  5113.2 1131.25  5212.2 1131.59  5255.8 1127.97  5271.7 1129.42  5287.7 1133.76
  5301.5 1134.56  5450.2 1135.63  5645.9 1146.49  5699.7 1148.16  5713.2 1149.73
    5765 1151.66  5770.7 1152.78  5802.7 1153.07    5852 1156.57  5885.3 1157.86
#Mann= 4 ,-1 , 0
  4221.4     .05       0  4953.1    .035       0  5013.2     .05       0
  5885.3      .1       0
Bank Sta=4953.1,5023.2
XS Rating Curve= 0 ,0
Exp/Cntr=0.3,0.1

Type RM Length L Ch R = 1 ,145     ,0,0,0
BEGIN DESCRIPTION:
SALTER SPRING CREEK 1.0
END DESCRIPTION:
XS GIS Cut Line= 4
      2913548.67     10086366.75      2913104.08     10085570.37
       2913046.1     10085562.64      2912061.87     10086257.38
#Sta/Elev= 30
  4133.4 1141.91  4230.2 1141.91  4430.1 1137.08  4695.1 1126.92  4803.7 1128.83
  4857.4 1126.94  4906.5 1127.61  4965.9 1124.79  4972.9 1123.72  4995.6 1121.31
  5045.5 1123.88    5057  1124.9  5110.9 1123.46    5117 1125.48  5131.8 1124.18
  5152.7 1126.56  5369.4 1131.71  5461.8 1131.08  5476.5 1132.82    5505 1133.14
  5583.7 1130.88  5627.4 1133.23  5812.6 1135.29    5857 1136.64  5934.5 1141.88
  5993.7 1143.32  6043.6 1147.38    6187 1153.64  6264.5 1159.25  6308.7 1160.79
#Mann= 4 ,-1 , 0
  4133.4     .05       0  4972.9    .035       0  5045.5     .05       0
  6308.7      .1       0
Bank Sta=4965.9,5057
XS Rating Curve= 0 ,0
Exp/Cntr=0.3,0.1

Chan Stop Cuts=-1
Use User Specified Reach Order=0
Composite Channel Slope=5