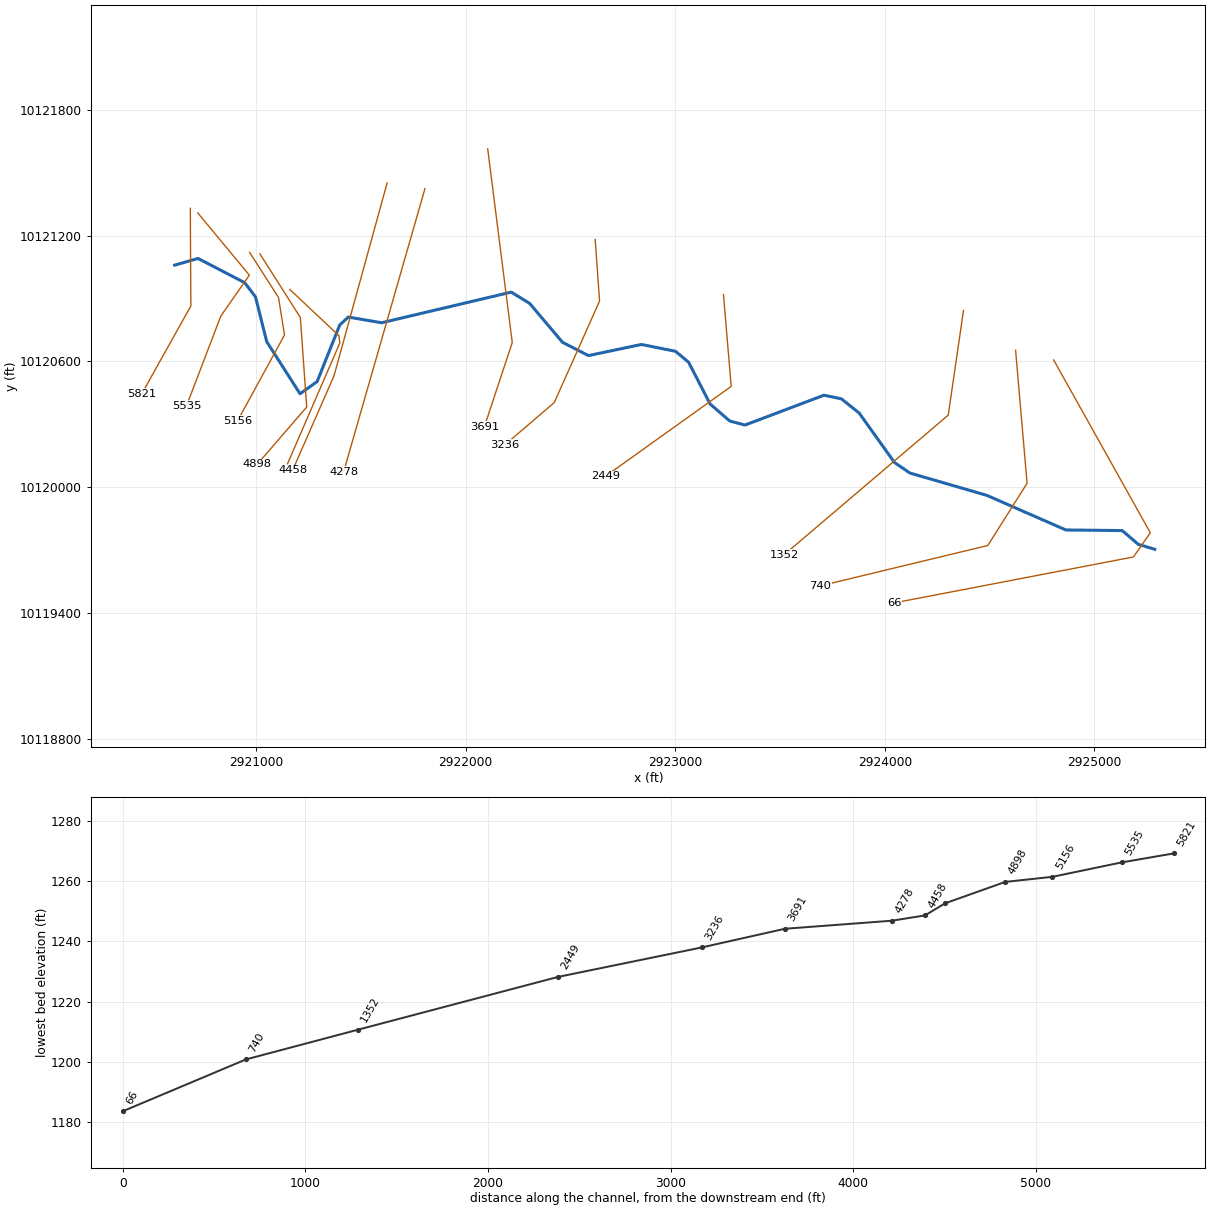
--- STRIBLING CREEK.prj (project) ---

Proj Title=STRIBLING CREEK Base Level Engineering
Current Plan=p01
Default Exp/Contr=0.3,0.1
English Units
Geom File=g01
Flow File=f01
Plan File=p01
BEGIN DESCRIPTION:
STRIBLING CREEK
END DESCRIPTION:

--- STRIBLING CREEK.p01 (plan) ---

Plan Title=Multiple Run
Short Identifier=Multiple
Geom File=g01
Flow File=f01
Subcritical Flow
K Sum by GR= 0
Std Step Tol= 0.01
Critical Tol= 0.01
Num of Std Step Trials= 20
Max Error Tol= 0.3
Flow Tol Ratio= 0.001
Split Flow NTrial= 30
Split Flow Tol= 0.02
Split Flow Ratio= 0.02
Log Output Level= 0
Friction Slope Method= 1
Unsteady Friction Slope Method= 2
Unsteady Bridges Friction Slope Method= 1
Parabolic Critical Depth
Global Vel Dist=  1 , 1 , 1
Global Log Level= 0
CheckData=True
Encroach Param= -1, 0, 0, 0
BEGIN DESCRIPTION:
Multiple Run
END DESCRIPTION:

--- STRIBLING CREEK.f01 (steady flow) ---

Flow Title=Multiple
Number of Profiles=7
Profile Names=10-year,25-year,50-year,1pct_min,100-year,1pct_plu,500-year
River Rch & RM= STRIBLING CREEK,Reach-1,5821
     811    1179    1499    1397    1889    2555    3010
River Rch & RM= STRIBLING CREEK,Reach-1,4458
    1102    1626    2089    1964    2656    3592    4313
Boundary for River Rch & Prof#=STRIBLING CREEK,Reach-1,1
Up Type=0
Dn Type=3
Dn Slope=0.005
Boundary for River Rch & Prof#=STRIBLING CREEK,Reach-1,2
Up Type=0
Dn Type=3
Dn Slope=0.005
Boundary for River Rch & Prof#=STRIBLING CREEK,Reach-1,3
Up Type=0
Dn Type=3
Dn Slope=0.005
Boundary for River Rch & Prof#=STRIBLING CREEK,Reach-1,4
Up Type=0
Dn Type=3
Dn Slope=0.005
Boundary for River Rch & Prof#=STRIBLING CREEK,Reach-1,5
Up Type=0
Dn Type=3
Dn Slope=0.005
Boundary for River Rch & Prof#=STRIBLING CREEK,Reach-1,6
Up Type=0
Dn Type=3
Dn Slope=0.005
Boundary for River Rch & Prof#=STRIBLING CREEK,Reach-1,7
Up Type=0
Dn Type=3
Dn Slope=0.005

--- STRIBLING CREEK.g01 (geometry) ---

Geom Title=Existing Conditions

River Reach=STRIBLING CREEK,Reach-1
Reach XY= 30
      2920610.82     10121059.59      2920722.62     10121091.61
      2920944.93     10120976.14      2920996.60     10120908.54
      2921050.33     10120694.50      2921209.28     10120445.78
      2921290.88     10120504.12      2921398.61     10120773.77
      2921439.38     10120811.90      2921598.74     10120784.81
      2922217.21     10120930.96      2922305.20     10120877.05
      2922461.96     10120691.51      2922585.67     10120628.03
      2922838.55     10120681.25      2923001.05     10120648.54
      2923063.64     10120596.60      2923166.18     10120397.36
      2923259.50     10120316.22      2923332.75     10120296.53
      2923709.50     10120438.94      2923792.64     10120421.88
      2923877.41     10120354.22      2924046.29     10120117.91
      2924120.05     10120067.60      2924487.34     10119961.00
      2924864.06     10119796.02      2925133.29     10119793.02
      2925209.92     10119727.30      2925288.47     10119703.73

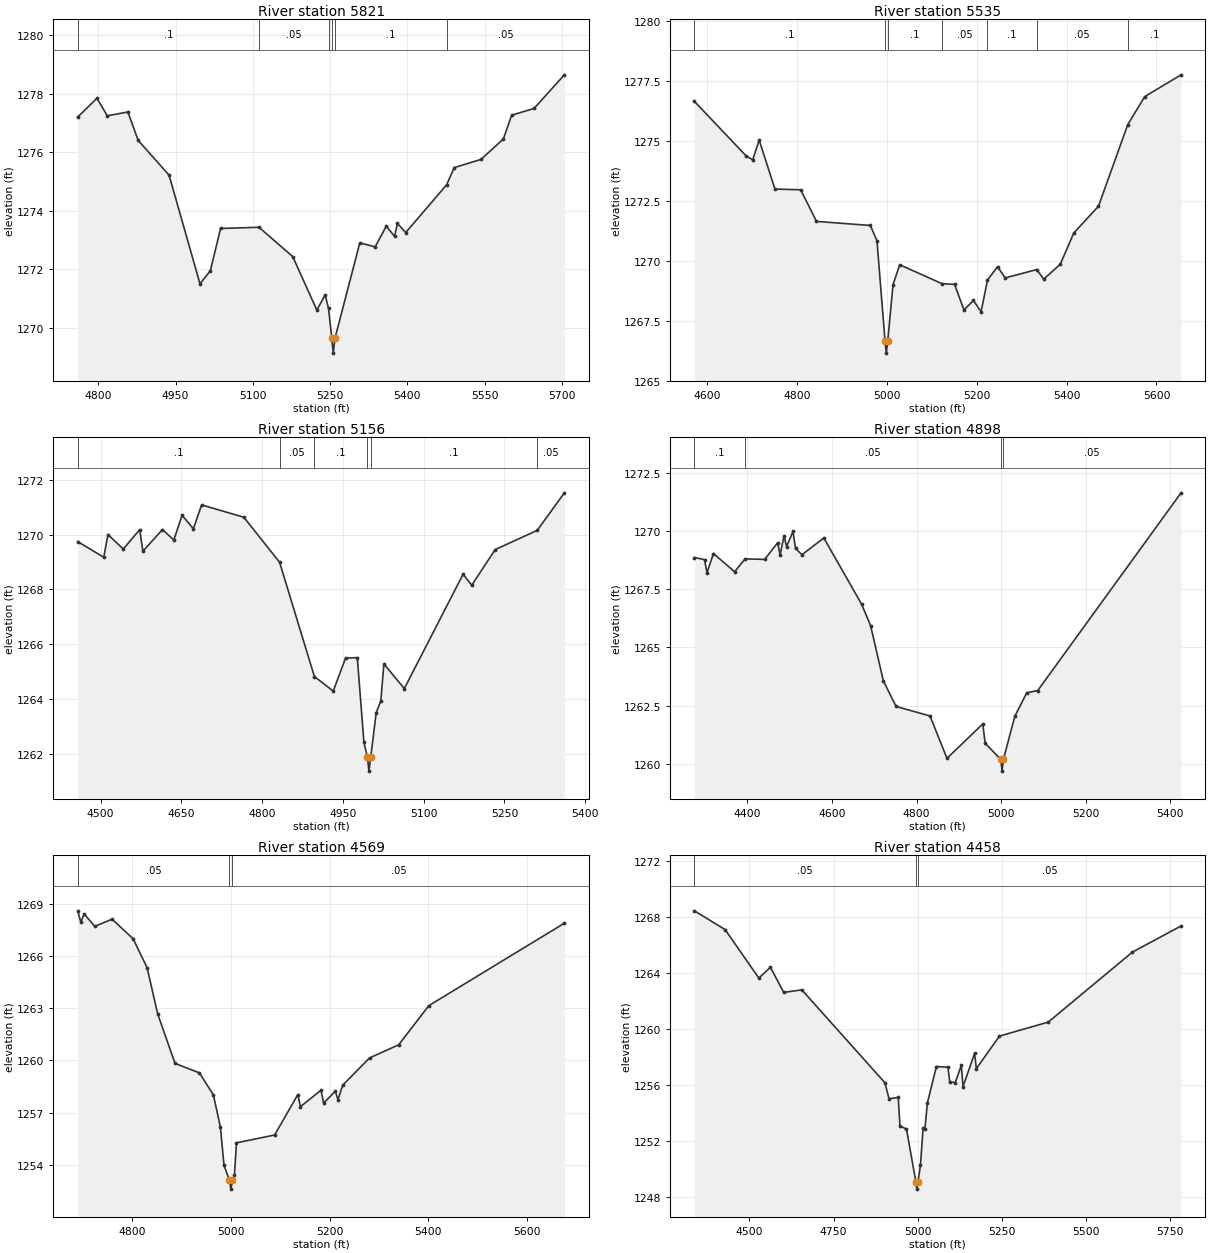
Type RM Length L Ch R = 1,5821,286,286,286
BEGIN DESCRIPTION:
STRIBLING CREEK 9.0
END DESCRIPTION:
XS GIS Cut Line= 3
      2920685.58     10121330.99      2920688.19     10120864.81
      2920454.70     10120447.13
#Sta/Elev= 30
  4760.1 1277.20  4797.4 1277.84  4817.4 1277.24  4857.4 1277.37  4877.4 1276.40
  4937.4 1275.21  4997.4 1271.50  5017.4 1271.94  5037.4 1273.39  5112.0 1273.43
  5177.4 1272.43  5224.3 1270.60  5240.3 1271.12  5246.9 1270.66  5253.3 1269.63
  5256.1 1269.13  5259.3 1269.63  5307.7 1272.90  5337.4 1272.76  5359.1 1273.47
  5375.1 1273.12  5380.8 1273.56  5396.8 1273.25  5476.1 1274.88  5491.0 1275.47
  5543.0 1275.75  5586.4 1276.45  5602.4 1277.26  5645.8 1277.49  5704.8 1278.64
#Mann=6,-1,0
  4760.1     0.1       0  5112.0    0.05       0  5246.9     0.1       0
  5253.3    0.07       0  5259.3     0.1       0  5476.1    0.05       0
Bank Sta=5253.3,5259.3
Exp/Cntr=0.3,0.1

Type RM Length L Ch R = 1,5535,379,379,379
BEGIN DESCRIPTION:
STRIBLING CREEK 7.0
END DESCRIPTION:
XS GIS Cut Line= 4
      2920721.07     10121308.98      2920967.45     10121011.94
      2920831.12     10120816.66      2920667.40     10120388.04
#Sta/Elev= 30
  4571.9 1276.66  4687.2 1274.38  4701.6 1274.22  4715.9 1275.05  4751.0 1273.00
  4808.3 1272.97  4843.5 1271.65  4963.3 1271.48  4978.1 1270.84  4996.0 1266.65
  4998.8 1266.15  5002.0 1266.65  5013.8 1269.01  5028.7 1269.84  5122.8 1269.05
  5150.8 1269.02  5171.7 1267.95  5192.7 1268.35  5209.8 1267.88  5224.0 1269.20
  5246.4 1269.76  5263.3 1269.29  5333.7 1269.64  5349.0 1269.24  5386.0 1269.86
  5416.1 1271.17  5470.9 1272.28  5536.1 1275.69  5573.8 1276.86  5654.8 1277.77
#Mann=7,-1,0
  4571.9     0.1       0  4996.0    0.07       0  5002.0     0.1       0
  5122.8    0.05       0  5224.0     0.1       0  5333.7    0.05       0
  5536.1     0.1       0
Bank Sta=4996,5002
Exp/Cntr=0.3,0.1

Type RM Length L Ch R = 1,5156,258,258,258
BEGIN DESCRIPTION:
STRIBLING CREEK 8.0
END DESCRIPTION:
XS GIS Cut Line= 4
      2920968.41     10121120.97      2921106.56     10120905.45
      2921135.10     10120726.39      2920911.20     10120317.14
#Sta/Elev= 30
  4457.6 1269.74  4505.9 1269.17  4513.7 1270.00  4542.2 1269.47  4572.7 1270.18
  4578.6 1269.39  4614.9 1270.18  4636.1 1269.80  4651.3 1270.70  4672.4 1270.21
  4687.6 1271.08  4766.0 1270.63  4832.4 1268.99  4897.1 1264.82  4932.1 1264.29
  4954.9 1265.49  4976.8 1265.51  4989.1 1262.42  4995.7 1261.87  4998.4 1261.37
  5001.7 1261.87  5011.9 1263.50  5020.5 1263.94  5026.2 1265.28  5064.1 1264.38
  5173.2 1268.55  5189.3 1268.15  5232.9 1269.45  5310.9 1270.15  5361.4 1271.52
#Mann=6,-1,0
  4457.6     0.1       0  4832.4    0.05       0  4897.1     0.1       0
  4995.7    0.07       0  5001.7     0.1       0  5310.9    0.05       0
Bank Sta=4995.7,5001.7
Exp/Cntr=0.3,0.1

Type RM Length L Ch R = 1,4898,329,329,329
BEGIN DESCRIPTION:
Mapping XS f8d52a9d
END DESCRIPTION:
XS GIS Cut Line= 4
      2921017.53     10121113.81      2921210.70     10120809.95
      2921241.08     10120382.43      2921004.55     10120109.00
#Sta/Elev= 30
  4275.1 1268.86  4298.9 1268.77  4304.8 1268.21  4320.0 1269.03  4370.0 1268.25
  4394.8 1268.80  4441.1 1268.78  4471.6 1269.49  4477.6 1268.98  4486.9 1269.79
  4492.8 1269.33  4508.0 1269.98  4514.0 1269.25  4529.2 1268.98  4580.9 1269.70
  4670.3 1266.85  4691.5 1265.93  4721.6 1263.56  4751.7 1262.46  4831.9 1262.05
  4872.0 1260.23  4956.7 1261.71  4962.2 1260.88  4999.3 1260.18  5002.1 1259.68
  5005.3 1260.18  5032.4 1262.04  5060.6 1263.05  5086.3 1263.14  5425.3 1271.64
#Mann=4,-1,0
  4275.1     0.1       0  4394.8    0.05       0  4999.3    0.04       0
  5005.3    0.05       0
Bank Sta=4999.3,5005.3
Exp/Cntr=0.3,0.1

Type RM Length L Ch R = 1,4569,111,111,111
BEGIN DESCRIPTION:
Mapping XS 06071ed5
END DESCRIPTION:
XS GIS Cut Line= 4
      2921160.12     10120944.03      2921394.93     10120722.97
      2921399.16     10120688.07      2921149.55     10120111.64
#Sta/Elev= 30
  4689.7 1268.59  4695.9 1267.94  4702.7 1268.41  4724.2 1267.70  4759.4 1268.11
  4801.9 1266.98  4830.2 1265.32  4851.6 1262.67  4886.8 1259.82  4936.2 1259.28
  4964.5 1258.01  4978.7 1256.16  4986.0 1253.97  4997.1 1253.10  4999.9 1252.60
  5003.1 1253.10  5007.0 1253.39  5011.2 1255.26  5088.5 1255.71  5135.5 1258.03
  5140.9 1257.34  5182.4 1258.28  5187.9 1257.54  5211.4 1258.23  5216.8 1257.74
  5226.4 1258.57  5280.9 1260.14  5339.7 1260.89  5400.8 1263.14  5675.5 1267.88
#Mann=3,-1,0
  4689.7    0.05       0  4997.1    0.04       0  5003.1    0.05       0
Bank Sta=4997.1,5003.1
Exp/Cntr=0.3,0.1

Type RM Length L Ch R = 1,4458,180,180,180
BEGIN DESCRIPTION:
STRIBLING CREEK 6.0
END DESCRIPTION:
XS GIS Cut Line= 3
      2921624.83     10121451.66      2921371.35     10120531.47
      2921173.44     10120080.11
#Sta/Elev= 30
  4336.3 1268.43  4427.5 1267.09  4527.9 1263.63  4562.3 1264.40  4601.8 1262.61
  4655.7 1262.79  4902.8 1256.16  4915.0 1255.02  4942.4 1255.11  4947.6 1253.07
  4966.9 1252.86  4995.0 1249.07  4997.7 1248.57  5001.0 1249.07  5008.4 1250.26
  5016.4 1252.94  5021.6 1252.85  5029.1 1254.72  5055.9 1257.32  5090.3 1257.27
  5095.5 1256.23  5112.1 1256.17  5129.9 1257.40  5135.1 1255.89  5169.5 1258.26
  5174.7 1257.17  5243.4 1259.49  5388.6 1260.49  5638.6 1265.48  5783.6 1267.35
#Mann=3,-1,0
  4336.3    0.05       0  4995.0    0.04       0  5001.0    0.05       0
Bank Sta=4995,5001
Exp/Cntr=0.3,0.1

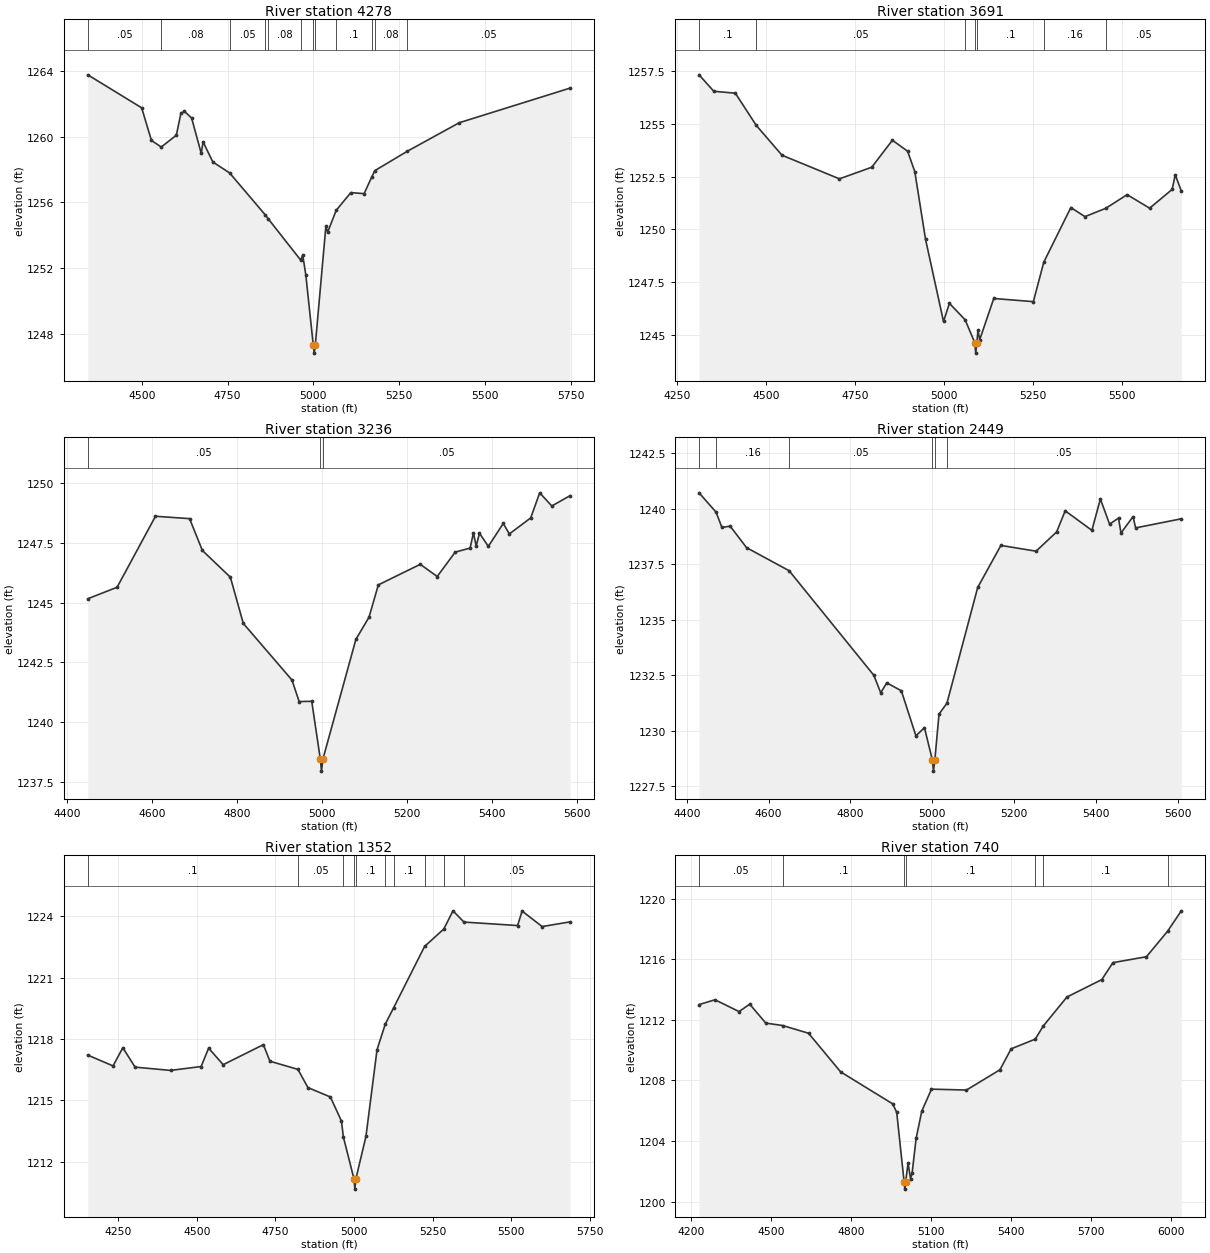
Type RM Length L Ch R = 1,4278,587,587,587
BEGIN DESCRIPTION:
STRIBLING CREEK 5.0
END DESCRIPTION:
XS GIS Cut Line= 2
      2921805.37     10121424.69      2921417.36     10120073.18
#Sta/Elev= 30
  4342.3 1263.78  4499.4 1261.77  4527.9 1259.78  4556.5 1259.38  4600.5 1260.10
  4613.8 1261.43  4624.2 1261.55  4645.0 1261.15  4673.2 1258.99  4678.4 1259.70
  4706.9 1258.47  4755.9 1257.80  4860.0 1255.24  4867.9 1255.02  4963.0 1252.49
  4969.0 1252.79  4977.9 1251.61  4999.7 1247.32  5002.5 1246.82  5005.7 1247.32
  5036.5 1254.54  5041.7 1254.19  5066.6 1255.52  5109.1 1256.60  5148.0 1256.54
  5170.4 1257.56  5179.2 1257.94  5273.7 1259.12  5425.3 1260.86  5748.4 1262.97
#Mann=12,-1,0
  4342.3    0.05       0  4556.5    0.08       0  4755.9    0.05       0
  4860.0    0.16       0  4867.9    0.08       0  4963.0    0.05       0
  4999.7    0.04       0  5005.7    0.05       0  5066.6     0.1       0
  5170.4    0.05       0  5179.2    0.08       0  5273.7    0.05       0
Bank Sta=4999.7,5005.7
Exp/Cntr=0.3,0.1

Type RM Length L Ch R = 1,3691,455,455,455
BEGIN DESCRIPTION:
STRIBLING CREEK 4.0
END DESCRIPTION:
XS GIS Cut Line= 3
      2922104.86     10121614.79      2922222.04     10120690.33
      2922089.23     10120289.31
#Sta/Elev= 30
  4312.4 1257.33  4353.8 1256.55  4414.3 1256.46  4473.2 1254.93  4545.3 1253.52
  4706.6 1252.40  4797.3 1252.95  4855.4 1254.23  4898.1 1253.71  4918.3 1252.74
  4948.5 1249.53  4998.9 1245.64  5015.5 1246.50  5059.6 1245.72  5086.6 1244.64
  5089.4 1244.14  5092.6 1244.64  5095.6 1245.22  5100.7 1244.78  5140.0 1246.73
  5251.2 1246.58  5280.5 1248.45  5356.5 1251.04  5396.1 1250.61  5454.0 1251.00
  5514.6 1251.65  5577.8 1251.01  5641.0 1251.90  5649.7 1252.59  5666.7 1251.83
#Mann=7,-1,0
  4312.4     0.1       0  4473.2    0.05       0  5059.6     0.1       0
  5086.6   0.035       0  5092.6     0.1       0  5280.5    0.16       0
  5454.0    0.05       0
Bank Sta=5086.6,5092.6
Exp/Cntr=0.3,0.1

Type RM Length L Ch R = 1,3236,787,787,787
BEGIN DESCRIPTION:
STRIBLING CREEK 3.0
END DESCRIPTION:
XS GIS Cut Line= 4
      2922617.87     10121182.50      2922638.71     10120888.24
      2922422.56     10120403.87      2922188.15     10120203.32
#Sta/Elev= 30
  4448.9 1245.16  4517.8 1245.64  4608.1 1248.61  4688.3 1248.51  4718.3 1247.18
  4784.2 1246.06  4814.5 1244.13  4929.0 1241.76  4945.9 1240.86  4975.5 1240.87
  4995.7 1238.45  4998.4 1237.95  5001.7 1238.45  5079.3 1243.46  5110.2 1244.39
  5132.1 1245.74  5230.7 1246.60  5270.5 1246.09  5312.8 1247.11  5347.9 1247.28
  5355.6 1247.91  5362.2 1247.37  5369.9 1247.90  5390.7 1247.35  5425.8 1248.31
  5440.1 1247.87  5490.3 1248.54  5511.5 1249.59  5540.0 1249.04  5582.8 1249.47
#Mann=3,-1,0
  4448.9    0.05       0  4995.7   0.035       0  5001.7    0.05       0
Bank Sta=4995.7,5001.7
Exp/Cntr=0.3,0.1

Type RM Length L Ch R = 1,2449,1097,1097,1097
BEGIN DESCRIPTION:
Mapping XS 78b8b413
END DESCRIPTION:
XS GIS Cut Line= 3
      2923230.06     10120919.44      2923266.96     10120481.07
      2922665.85     10120051.40
#Sta/Elev= 30
  4430.2 1240.72  4471.8 1239.85  4486.1 1239.16  4506.2 1239.22  4546.3 1238.25
  4650.4 1237.21  4857.4 1232.50  4874.3 1231.71  4889.0 1232.16  4924.7 1231.80
  4960.3 1229.77  4981.2 1230.14  5000.5 1228.68  5003.2 1228.18  5006.5 1228.68
  5016.8 1230.75  5036.1 1231.24  5111.4 1236.46  5168.0 1238.35  5254.0 1238.09
  5304.3 1238.96  5325.2 1239.91  5390.4 1239.03  5411.2 1240.44  5433.7 1239.31
  5455.5 1239.58  5461.6 1238.91  5491.1 1239.65  5497.3 1239.14  5609.0 1239.55
#Mann=6,-1,0
  4430.2     0.1       0  4471.8    0.16       0  4650.4    0.05       0
  5000.5   0.035       0  5006.5    0.05       0  5036.1    0.05       0
Bank Sta=5000.5,5006.5
Exp/Cntr=0.3,0.1

Type RM Length L Ch R = 1,1352,612,612,612
BEGIN DESCRIPTION:
STRIBLING CREEK 2.0
END DESCRIPTION:
XS GIS Cut Line= 3
      2924375.68     10120843.95      2924302.77     10120343.97
      2923519.74     10119678.01
#Sta/Elev= 30
  4153.3 1217.21  4233.6 1216.68  4264.7 1217.57  4303.7 1216.62  4416.3 1216.46
  4513.7 1216.65  4537.5 1217.55  4583.7 1216.74  4711.6 1217.72  4732.4 1216.91
  4821.4 1216.51  4853.2 1215.62  4924.6 1215.16  4959.8 1213.98  4965.8 1213.21
  4999.6 1211.15  5002.4 1210.65  5005.6 1211.15  5037.7 1213.23  5072.9 1217.47
  5099.2 1218.73  5125.5 1219.52  5224.2 1222.53  5285.2 1223.38  5314.5 1224.27
  5349.2 1223.72  5519.8 1223.55  5534.1 1224.26  5597.8 1223.50  5686.5 1223.73
#Mann=10,-1,0
  4153.3     0.1       0  4821.4    0.05       0  4965.8     0.1       0
  4999.6    0.07       0  5005.6     0.1       0  5099.2    0.05       0
  5125.5     0.1       0  5224.2    0.05       0  5285.2     0.1       0
  5349.2    0.05       0
Bank Sta=4999.6,5005.6
Exp/Cntr=0.3,0.1

Type RM Length L Ch R = 1,740,674,674,674
BEGIN DESCRIPTION:
Mapping XS b3f931ae
END DESCRIPTION:
XS GIS Cut Line= 4
      2924624.27     10120653.35      2924679.06     10120018.92
      2924491.63     10119721.91      2923691.73     10119529.13
#Sta/Elev= 30
  4228.7 1213.00  4288.5 1213.32  4378.9 1212.54  4419.0 1213.03  4479.2 1211.78
  4542.3 1211.62  4639.8 1211.11  4760.3 1208.56  4955.6 1206.45  4970.9 1205.89
  4998.5 1201.32  5001.2 1200.82  5004.5 1201.32  5013.5 1202.53  5022.7 1201.52
  5028.6 1201.86  5043.8 1204.17  5065.0 1205.97  5101.5 1207.42  5232.8 1207.36
  5358.6 1208.70  5400.5 1210.08  5491.0 1210.72  5520.9 1211.58  5610.0 1213.50
  5740.9 1214.65  5782.8 1215.77  5908.6 1216.16  5988.3 1217.85  6039.5 1219.19
#Mann=7,-1,0
  4228.7    0.05       0  4542.3     0.1       0  4998.5    0.07       0
  5004.5     0.1       0  5491.0    0.16       0  5520.9     0.1       0
  5988.3    0.05       0
Bank Sta=4998.5,5004.5
Exp/Cntr=0.3,0.1

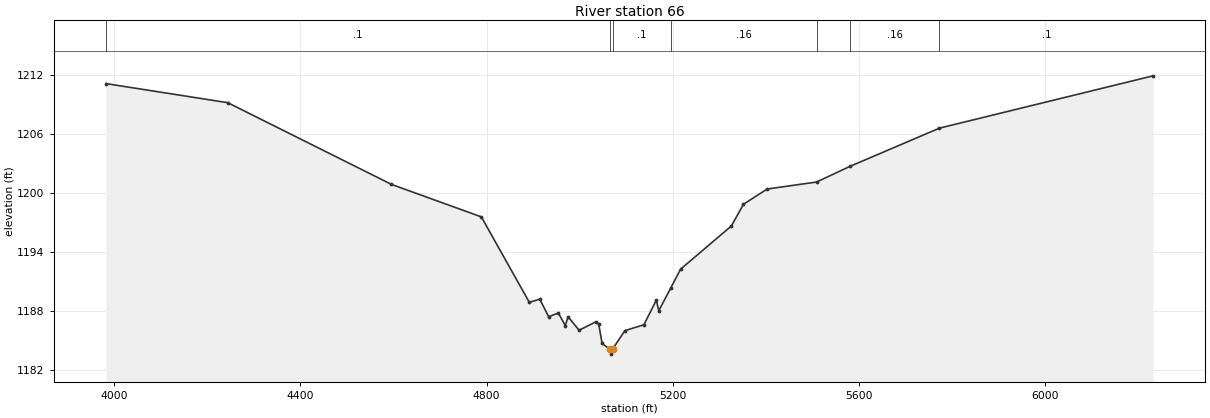
Type RM Length L Ch R = 1,66,0,0,0
BEGIN DESCRIPTION:
STRIBLING CREEK 1.0
END DESCRIPTION:
XS GIS Cut Line= 4
      2924805.93     10120607.18      2925267.31     10119782.47
      2925186.57     10119667.12      2924044.71     10119447.98
#Sta/Elev= 30
  3982.5 1211.15  4244.0 1209.21  4595.7 1200.90  4788.6 1197.60  4891.7 1188.91
  4914.2 1189.23  4933.1 1187.45  4954.1 1187.82  4968.9 1186.54  4975.0 1187.44
  4998.5 1186.07  5034.3 1186.92  5040.4 1186.75  5048.0 1184.73  5064.3 1184.14
  5067.1 1183.64  5070.3 1184.14  5096.9 1186.03  5137.6 1186.62  5164.5 1189.13
  5169.6 1188.05  5195.2 1190.35  5216.5 1192.28  5325.5 1196.67  5351.5 1198.88
  5402.4 1200.43  5508.5 1201.14  5580.0 1202.73  5772.4 1206.62  6231.0 1211.94
#Mann=7,-1,0
  3982.5     0.1       0  5064.3    0.07       0  5070.3     0.1       0
  5195.2    0.16       0  5508.5     0.1       0  5580.0    0.16       0
  5772.4     0.1       0
Bank Sta=5064.3,5070.3
Exp/Cntr=0.3,0.1

Chan Stop Cuts=-1