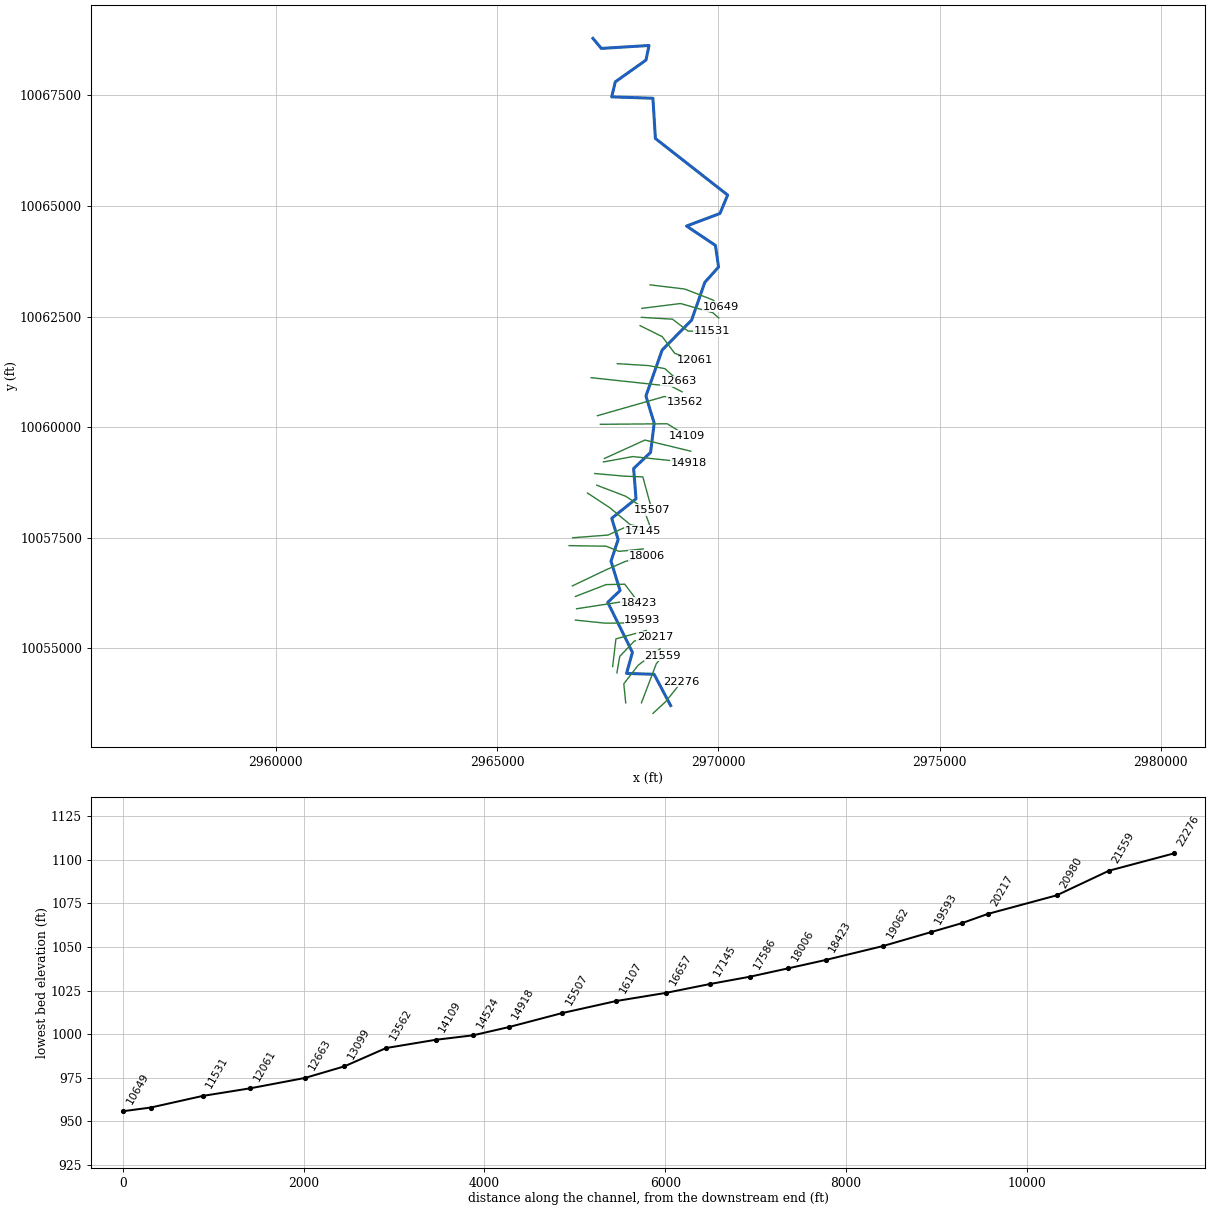
--- SYCAMORE CREEK.prj (project) ---

Proj Title=SYCAMORE CREEK Base Level Engineering
Current Plan=p01
Default Exp/Contr=0.3,0.1
English Units
Geom File=g01
Flow File=f01
Plan File=p01
Y Axis Title=Elevation
X Axis Title(PF)=Main Channel Distance
X Axis Title(XS)=Station
BEGIN DESCRIPTION:
SYCAMORE CREEK
END DESCRIPTION:
DSS Export Rating Curves= 0
DSS Export Rating Curve Sorted= 0
DSS Export Volume Flow Curves= 0
DXF OffsetX= 0
DXF OffsetY= 0
DXF ScaleX= 1
DXF ScaleY= 10

--- SYCAMORE CREEK.p01 (plan) ---

Plan Title=Multiple Run
Short Identifier=Multiple
Geom File=g01
Flow File=f01
Subcritical Flow
K Sum by GR= 0
Std Step Tol= 0.01
Critical Tol= 0.01
Num of Std Step Trials= 20
Max Error Tol= 0.3
Flow Tol Ratio= 0.001
Split Flow NTrial= 30
Split Flow Tol= 0.02
Split Flow Ratio= 0.02
Log Output Level= 0
Friction Slope Method= 1
Unsteady Friction Slope Method= 2
Unsteady Bridges Friction Slope Method= 1
Parabolic Critical Depth
Global Vel Dist=  1 , 1 , 1
Global Log Level= 0
CheckData=True
Encroach Param= -1, 0, 0, 0
BEGIN DESCRIPTION:
Multiple Run
END DESCRIPTION:

--- SYCAMORE CREEK.f01 (steady flow) ---

Flow Title=Multiple
Program Version=4.10
Number of Profiles= 7
Profile Names=10-year,25-year,50-year,1pct_min,100-year,1pct_plu,500-year
River Rch & RM=SYCAMORE CREEK,Reach-1         ,22276
     975    1423    1816    1697    2296    3104    3679
River Rch & RM=SYCAMORE CREEK,Reach-1         ,19593
    1588    2382    3096    2942    3979    5382    6599
River Rch & RM=SYCAMORE CREEK,Reach-1         ,18006
    2105    3197    4189    4011    5424    7335    9129
River Rch & RM=SYCAMORE CREEK,Reach-1         ,14524
    2395    3650    4793    4596    6215    8405   10492
River Rch & RM=SYCAMORE CREEK,Reach-1         ,9408
    3237    4999    6623    6401    8656   11707   14850
River Rch & RM=SYCAMORE CREEK,Reach-1         ,6797
    4794    7502   10027    9764   13205   17859   23002
Boundary for River Rch & Prof#=SYCAMORE CREEK,Reach-1         , 1
Up Type= 0
Dn Type= 3
Dn Slope=0.013
Boundary for River Rch & Prof#=SYCAMORE CREEK,Reach-1         , 2
Up Type= 0
Dn Type= 3
Dn Slope=0.013
Boundary for River Rch & Prof#=SYCAMORE CREEK,Reach-1         , 3
Up Type= 0
Dn Type= 3
Dn Slope=0.013
Boundary for River Rch & Prof#=SYCAMORE CREEK,Reach-1         , 4
Up Type= 0
Dn Type= 3
Dn Slope=0.013
Boundary for River Rch & Prof#=SYCAMORE CREEK,Reach-1         , 5
Up Type= 0
Dn Type= 3
Dn Slope=0.013
Boundary for River Rch & Prof#=SYCAMORE CREEK,Reach-1         , 6
Up Type= 0
Dn Type= 3
Dn Slope=0.013
Boundary for River Rch & Prof#=SYCAMORE CREEK,Reach-1         , 7
Up Type= 0
Dn Type= 3
Dn Slope=0.013
DSS Import GetInterval= 0
DSS Import GetPeak= 0
DSS Import FillOption= 0

--- SYCAMORE CREEK.g01 (geometry) ---

Geom Title=Existing Conditions
Program Version=4.10

River Reach=SYCAMORE CREEK  ,Reach-1
Reach XY= 30
      2968920.29     10053704.29      2968547.09     10054411.16
      2967924.04     10054431.16      2968056.72     10054907.75
      2967499.06     10056038.34      2967777.41     10056304.08
      2967572.87     10056969.34      2967734.64     10057458.66
      2967588.99     10057938.91      2968138.04     10058379.94
      2968084.03     10059064.21      2968467.36     10059428.33
      2968548.64     10060089.55       2968362.1     10060704.02
      2968728.76     10061744.76      2969393.13     10062417.62
      2969691.72     10063272.38      2970003.16     10063621.31
      2969933.46     10064108.96      2969279.51      10064548.2
      2970035.19     10064831.55      2970208.77      10065248.7
       2968576.1     10066527.46      2968519.81     10067437.86
      2967588.11     10067468.37      2967670.06     10067808.75
       2968363.6     10068300.84       2968431.6     10068630.56
       2967352.9      10068564.7      2967163.93     10068792.54

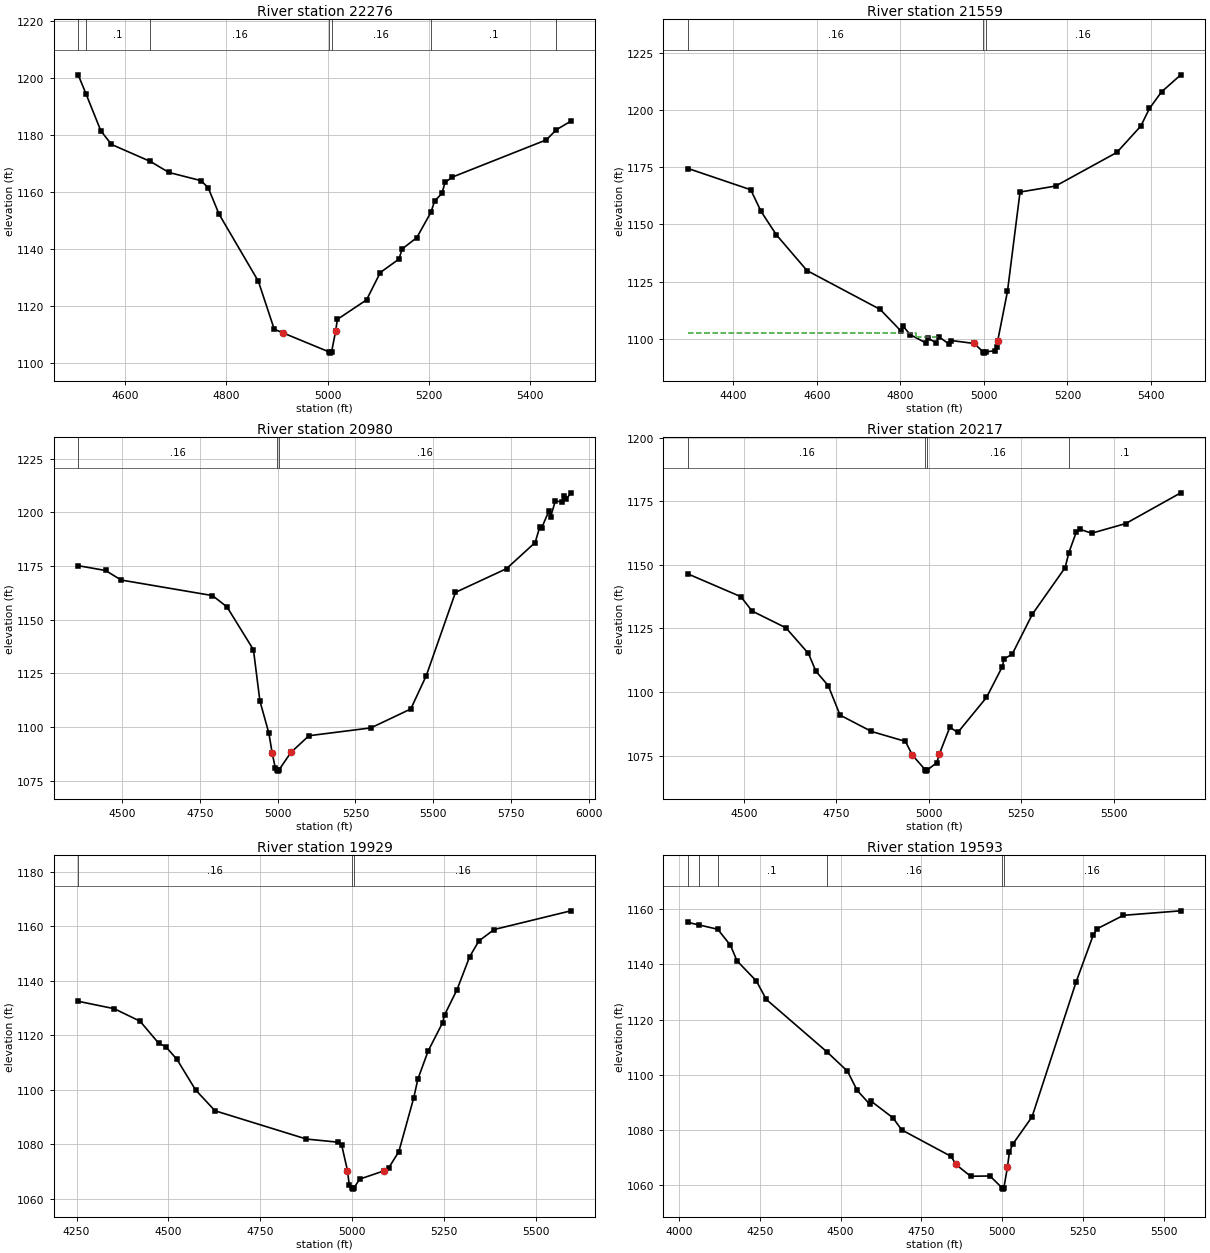
Type RM Length L Ch R = 1 ,22276   ,717,717,717
BEGIN DESCRIPTION:
SYCAMORE CREEK 44.0
END DESCRIPTION:
XS GIS Cut Line= 3
      2968521.54     10053527.45      2968807.99      10053792.2
      2969172.59     10054247.95
#Sta/Elev= 30
    4507 1201.05  4522.2  1194.5  4551.8 1181.42  4572.8 1176.66  4649.7 1170.69
  4686.2 1166.85  4749.7 1163.97  4763.8 1161.53  4785.4 1152.24  4863.1 1128.71
  4894.5 1111.91    4912 1110.61  5001.9 1104.03  5004.6 1103.53  5007.9 1104.03
 5015.68 1111.11  5019.3 1115.37  5076.9 1122.18  5104.1 1131.77  5140.9 1136.48
  5147.3 1140.04  5176.2 1143.99  5204.2 1152.89  5211.4 1156.79  5225.8 1159.48
  5232.2 1163.39  5246.6 1165.22  5432.3 1178.26  5452.2 1181.83  5480.7  1184.8
#Mann= 7 ,-1 , 0
    4507     .16       0  4522.2      .1       0  4649.7     .16       0
  5001.9     .07       0  5007.9     .16       0  5204.2      .1       0
  5452.2     .05       0
Bank Sta=4912,5015.68
XS Rating Curve= 0 ,0
Exp/Cntr=0.3,0.1

Type RM Length L Ch R = 1 ,21559   ,579,579,579
BEGIN DESCRIPTION:
SYCAMORE CREEK 43.0
END DESCRIPTION:
XS GIS Cut Line= 3
      2968261.13      10053766.2      2968595.32     10054647.24
      2968742.88     10054833.86
#Sta/Elev= 30
  4291.3 1174.47  4441.3 1165.17  4466.1 1155.67  4502.6 1145.46    4576  1129.8
  4751.5 1112.76  4801.1 1103.33  4806.4 1105.41  4823.4 1101.74  4861.3 1098.05
  4866.7 1100.13  4886.1 1098.02  4891.5  1100.9  4916.3 1097.58  4921.6 1099.16
  4976.5 1097.86  4998.3 1094.14  5001.1 1093.64  5004.3 1094.14  5026.1 1094.73
  5031.5 1096.21 5032.84 1098.92  5056.3 1120.66  5086.4 1164.16  5171.5 1166.79
  5318.4 1181.52  5375.7 1193.05  5396.5 1200.76  5425.4 1208.03  5471.5 1215.49
#Mann= 3 ,-1 , 0
  4291.3     .16       0  4998.3     .07       0  5004.3     .16       0
#XS Ineff= 2 ,-1
  4291.3 4836.48 1102.24 4840.36 4891.48 1100.91
Permanent Ineff=
       T       T
Bank Sta=4976.5,5032.84
XS Rating Curve= 0 ,0
Exp/Cntr=0.3,0.1

Type RM Length L Ch R = 1 ,20980   ,763,763,763
BEGIN DESCRIPTION:
SYCAMORE CREEK 41.0
END DESCRIPTION:
XS GIS Cut Line= 4
      2967905.21     10053766.18      2967861.81     10054195.85
      2968187.33     10054616.86      2968684.07     10054988.33
#Sta/Elev= 30
  4358.4 1175.22  4446.4 1172.98  4496.6 1168.54  4790.3 1161.29  4836.9 1156.03
    4922 1136.06  4942.8 1112.21  4971.8 1097.08 4982.39 1087.83  4992.6  1080.8
  4997.8 1080.02  5000.6 1079.52  5003.8 1080.02  5042.4  1088.2  5100.4 1096.01
  5299.6 1099.66  5427.9 1108.47  5477.9 1124.02  5571.7 1162.79  5735.9 1173.84
    5828 1186.02  5842.6  1193.2  5848.9 1192.77  5871.8 1200.64    5878 1198.11
  5892.6 1205.25  5913.5 1205.06  5921.8 1207.91  5928.1 1206.19  5942.7 1209.16
#Mann= 3 ,-1 , 0
  4358.4     .16       0  4997.8     .07       0  5003.8     .16       0
Bank Sta=4982.39,5042.4
XS Rating Curve= 0 ,0
Exp/Cntr=0.3,0.1

Type RM Length L Ch R = 1 ,20217   ,288,288,288
BEGIN DESCRIPTION:
SYCAMORE CREEK 40.0
END DESCRIPTION:
XS GIS Cut Line= 4
      2967705.57     10054443.29      2967770.67     10054816.51
      2968100.53     10055163.73      2968564.16     10055263.39
#Sta/Elev= 30
  4349.1 1146.42  4491.7  1137.5  4522.1 1131.85  4613.5 1125.25  4674.4 1115.15
  4694.7 1108.14    4728 1102.48  4759.8 1090.91  4844.8 1084.47  4936.6 1080.56
 4955.45 1075.17  4990.2 1069.36    4993 1068.86  4996.2 1069.36  5021.5 1072.17
  5028.4  1075.6  5056.7 1086.13  5078.2 1084.07  5155.8 1097.85  5198.3 1109.85
  5203.4 1113.03  5225.2 1114.85  5279.9 1130.61  5368.4 1148.92  5378.6 1154.87
  5399.1 1163.11  5409.3 1163.98    5440 1162.46  5532.1 1166.26  5681.1 1178.36
#Mann= 4 ,-1 , 0
  4349.1     .16       0  4990.2     .07       0  4996.2     .16       0
  5378.6      .1       0
Bank Sta=4955.45,5028.4
XS Rating Curve= 0 ,0
Exp/Cntr=0.3,0.1

Type RM Length L Ch R = 1 ,19929   ,336,336,336
BEGIN DESCRIPTION:
SYCAMORE CREEK 39.0
END DESCRIPTION:
XS GIS Cut Line= 3
      2967610.07     10054586.45      2967683.86     10055211.47
       2968369.6     10055402.44
#Sta/Elev= 30
  4254.4 1132.46  4352.4 1129.75  4422.8 1125.16  4473.2 1117.13  4493.3 1115.75
  4523.5 1111.12  4573.9 1099.96  4626.9  1092.3  4875.7 1081.92  4961.2 1080.78
  4971.6 1079.78  4987.5 1070.36  4992.3 1065.13  4999.7 1064.05  5002.5 1063.55
  5005.7 1064.05  5020.5 1067.21  5085.8 1070.21  5099.3 1071.25  5127.3 1077.29
  5167.7 1096.94  5179.2 1103.93  5207.1 1114.23  5246.5 1124.62  5251.9 1127.47
  5285.9 1136.78  5320.1 1148.81  5345.3 1154.61  5386.8 1158.79  5595.6 1165.65
#Mann= 3 ,-1 , 0
  4254.4     .16       0  4999.7     .07       0  5005.7     .16       0
Bank Sta=4987.5,5085.8
XS Rating Curve= 0 ,0
Exp/Cntr=0.3,0.1

Type RM Length L Ch R = 1 ,19593   ,531,531,531
BEGIN DESCRIPTION:
SYCAMORE CREEK 38.0
END DESCRIPTION:
XS GIS Cut Line= 4
      2966768.04     10055636.82      2967440.81     10055567.38
      2967926.92     10055571.72      2968282.84     10055636.83
#Sta/Elev= 30
  4028.4 1155.21    4063 1154.29    4120 1152.75  4159.5 1146.91  4179.6  1141.3
  4239.9 1133.94  4270.1 1127.31  4456.9 1108.39  4521.4 1101.28  4551.6 1094.29
  4590.5 1089.28  4595.5 1090.32  4662.2 1084.35  4689.4 1079.97  4842.4 1070.35
    4857 1067.44  4902.4 1063.17  4962.4 1063.27  4999.4    1059  5002.2  1058.5
  5005.4    1059 5016.36 1066.43  5022.4 1071.85  5032.4 1074.73  5092.4 1084.69
  5228.9 1133.65  5282.1 1150.72  5294.1 1152.94  5375.4  1157.8  5552.7 1159.43
#Mann= 6 ,-1 , 0
  4028.4      .1       0    4063     .16       0    4120      .1       0
  4456.9     .16       0  4999.4     .07       0  5005.4     .16       0
Bank Sta=4857,5016.36
XS Rating Curve= 0 ,0
Exp/Cntr=0.3,0.1

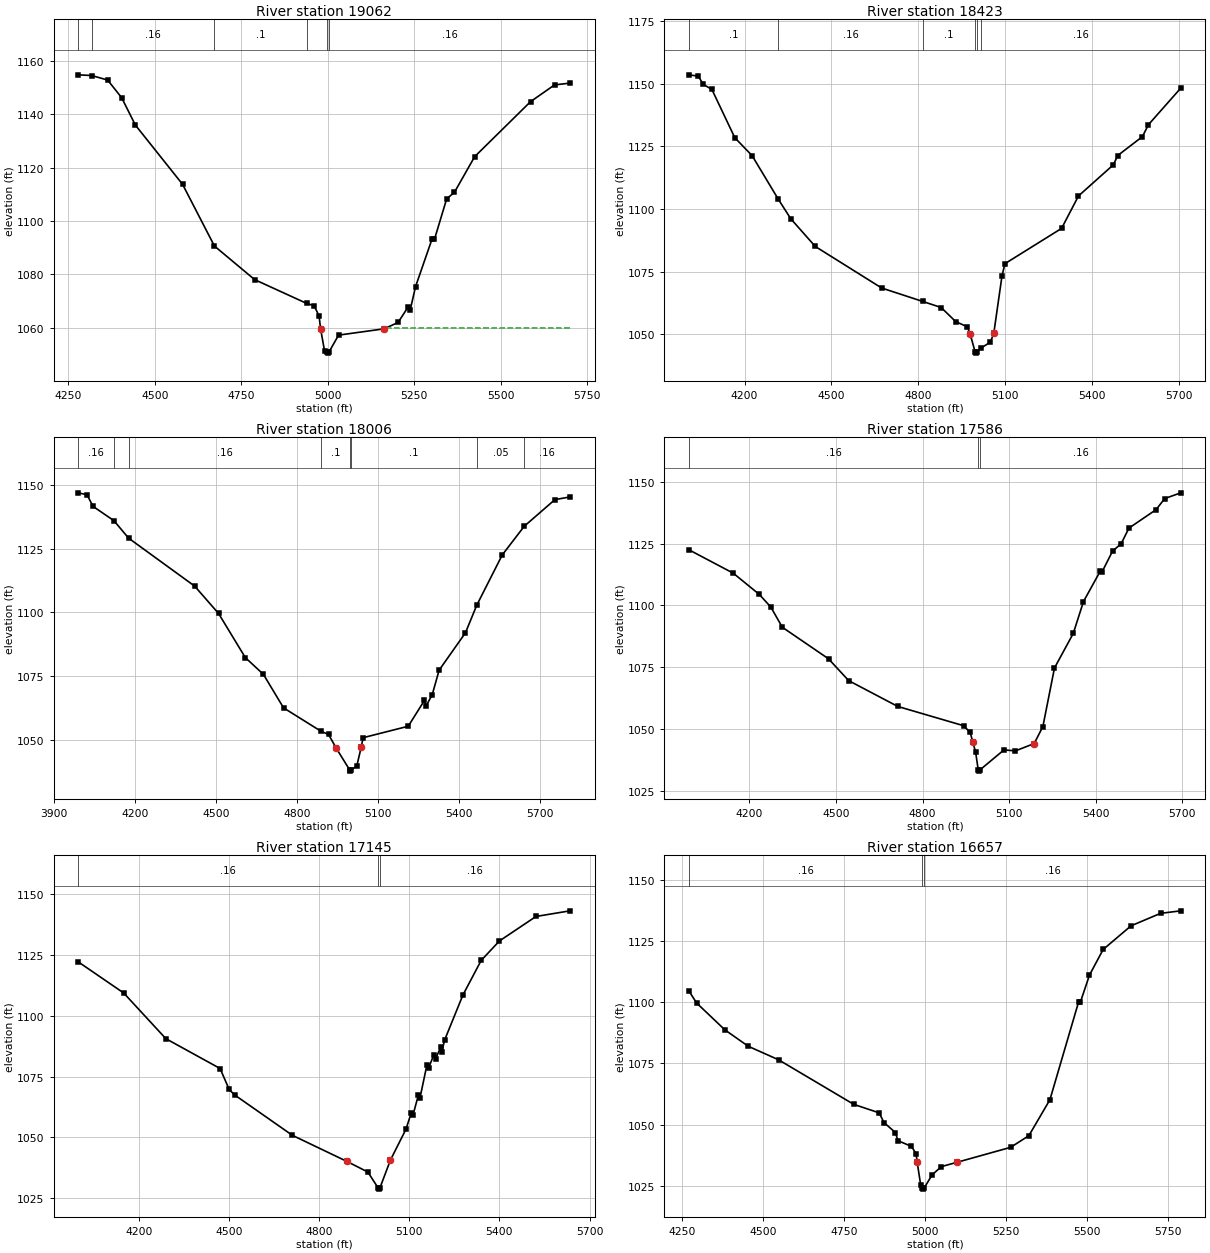
Type RM Length L Ch R = 1 ,19062   ,639,639,639
BEGIN DESCRIPTION:
SYCAMORE CREEK 37.0
END DESCRIPTION:
XS GIS Cut Line= 3
      2966794.15      10055892.9      2967809.73     10056049.15
      2968191.67     10055949.32
#Sta/Elev= 30
  4278.1 1154.86  4317.2  1154.6  4363.4  1152.9  4403.9 1146.29  4443.6 1136.02
  4580.2 1113.78  4672.2 1090.67  4788.4 1078.08  4939.3 1069.14  4960.4 1068.29
  4974.8 1064.46 4979.09 1059.67  4990.7 1051.28  4997.8 1051.02  5000.6 1050.52
  5003.8 1051.02  5031.2 1057.27  5162.7 1059.63  5203.2 1062.02  5232.8 1067.92
  5237.9 1066.52  5253.8 1075.47  5301.1 1093.18  5308.4 1093.18  5343.7 1108.36
  5366.3 1110.85  5424.6 1124.17  5586.3 1144.81  5655.7 1151.09  5700.4 1151.74
#Mann= 6 ,-1 , 0
  4278.1      .1       0  4317.2     .16       0  4672.2      .1       0
  4939.3     .16       0  4997.8     .07       0  5003.8     .16       0
#XS Ineff= 2 , 0
                          5169.6         1060.07
Permanent Ineff=
       T       T
Bank Sta=4979.09,5162.7
XS Rating Curve= 0 ,0
Exp/Cntr=0.3,0.1

Type RM Length L Ch R = 1 ,18423   ,417,417,417
BEGIN DESCRIPTION:
SYCAMORE CREEK 36.0
END DESCRIPTION:
XS GIS Cut Line= 4
       2966768.1     10056170.69      2967462.51     10056439.77
      2967883.52     10056448.45      2968204.09     10056023.91
#Sta/Elev= 30
  4008.2 1153.49  4040.8 1152.96  4057.5 1149.67  4087.4 1147.68  4166.5 1128.41
  4226.3 1121.24    4317  1103.8  4359.9 1096.05  4444.3 1085.03  4673.5 1068.45
  4815.5 1063.08  4878.9 1060.67  4928.9 1055.06  4968.9    1053  4978.9 1050.08
  4995.9 1042.98  4998.7 1042.48  5001.9 1042.98  5015.7 1044.46  5048.9 1046.88
 5060.57 1050.51  5088.9 1073.39  5098.9 1078.16  5294.5 1092.24  5352.8 1105.18
  5473.5 1117.64  5488.1 1121.29  5573.4 1128.84  5594.3 1133.61    5706 1148.22
#Mann= 6 ,-1 , 0
  4008.2      .1       0    4317     .16       0  4815.5      .1       0
  4995.9     .07       0  5001.9      .1       0  5015.7     .16       0
Bank Sta=4978.9,5060.57
XS Rating Curve= 0 ,0
Exp/Cntr=0.3,0.1

Type RM Length L Ch R = 1 ,18006   ,420,420,420
BEGIN DESCRIPTION:
SYCAMORE CREEK 35.0
END DESCRIPTION:
XS GIS Cut Line= 4
      2966698.66     10056409.41      2967471.19     10056778.31
      2967900.88     10056964.95      2968382.63     10057095.15
#Sta/Elev= 30
  3988.3  1146.9  4021.3 1146.15  4043.5 1141.58  4121.1 1135.96  4175.4 1129.11
  4420.3 1110.28  4508.9 1099.54  4608.2 1082.22  4675.2 1075.64  4749.9 1062.49
    4890 1053.22  4916.5 1052.07  4945.4 1046.63  4994.8 1038.16  4997.5 1037.66
  5000.8 1038.16  5021.2 1039.64  5037.7    1047  5044.7 1050.78  5212.1 1055.28
  5272.1 1065.41  5277.6 1063.11    5301 1067.66  5326.6 1077.29  5424.3 1091.98
    5466 1102.76  5560.7 1122.53  5642.1 1133.77  5755.8 1144.23  5811.9 1145.29
#Mann= 8 ,-1 , 0
  3988.3     .16       0  4121.1      .1       0  4175.4     .16       0
    4890      .1       0  4994.8     .07       0  5000.8      .1       0
    5466     .05       0  5642.1     .16       0
#XS Ineff= 3 ,-1
 5068.08  5089.8 1051.37 5120.65 5134.66 1052.73 5167.23 5184.07 1053.87
Permanent Ineff=
       T       T       T
Bank Sta=4945.4,5037.7
XS Rating Curve= 0 ,0
Exp/Cntr=0.3,0.1

Type RM Length L Ch R = 1 ,17586   ,441,441,441
BEGIN DESCRIPTION:
SYCAMORE CREEK 34.0
END DESCRIPTION:
XS GIS Cut Line= 4
      2966624.87     10057320.85      2967462.51     10057307.83
      2967757.65     10057190.64      2968303.96     10057247.01
#Sta/Elev= 30
  3990.2 1122.49  4143.8 1113.02  4233.8 1104.45  4273.8 1099.33  4313.8 1091.14
  4473.9 1078.36  4543.9 1069.52  4713.9 1059.08  4941.9 1051.29  4964.9 1048.55
  4974.2 1044.55  4983.8 1040.45  4992.7  1033.4  4995.5  1032.9  4998.7  1033.4
  5081.8 1041.49  5121.5  1041.1  5186.5 1044.05  5216.7 1050.94  5256.9 1074.65
    5322 1088.64  5357.4 1101.54    5416 1113.94    5421 1113.36    5458 1121.92
  5488.1 1124.98  5514.9 1131.27  5608.8 1138.73  5638.9 1143.23  5694.7 1145.55
#Mann= 3 ,-1 , 0
  3990.2     .16       0  4992.7     .07       0  4998.7     .16       0
Bank Sta=4974.2,5186.5
XS Rating Curve= 0 ,0
Exp/Cntr=0.3,0.1

Type RM Length L Ch R = 1 ,17145   ,488,488,488
BEGIN DESCRIPTION:
SYCAMORE CREEK 33.0
END DESCRIPTION:
XS GIS Cut Line= 4
      2966707.34      10057498.8      2967501.57     10057559.56
      2967879.17     10057728.84      2968300.22     10057659.38
#Sta/Elev= 30
    3998 1122.15  4149.6 1109.33    4290 1090.55  4470.5 1078.29  4500.6  1069.7
  4518.5 1067.46  4711.2 1050.83  4892.8  1040.1  4962.3 1035.75  4996.4 1029.23
  4999.1 1028.73  5002.4 1029.23  5037.4 1040.67  5089.2 1053.38  5106.9 1060.15
  5112.4  1059.1  5130.1 1067.25  5135.6 1066.11  5158.7 1079.69  5164.2 1078.47
  5181.9 1083.93  5187.4 1082.32  5205.1 1087.02  5208.2 1085.08  5217.8 1090.02
  5278.6 1108.49  5339.4 1122.71  5400.2 1130.71  5521.8 1140.77  5635.1 1143.09
#Mann= 3 ,-1 , 0
    3998     .16       0  4996.4     .07       0  5002.4     .16       0
Bank Sta=4892.8,5037.4
XS Rating Curve= 0 ,0
Exp/Cntr=0.3,0.1

Type RM Length L Ch R = 1 ,16657   ,550,550,550
BEGIN DESCRIPTION:
SYCAMORE CREEK 32.0
END DESCRIPTION:
XS GIS Cut Line= 4
      2967041.46     10058510.11      2967549.31     10058175.88
      2968009.38     10057793.94      2968313.23     10057724.49
#Sta/Elev= 30
  4271.3 1104.58  4294.8 1099.68  4382.2 1088.69  4454.5 1081.97  4547.8 1076.47
  4779.8 1058.26  4858.1  1054.8  4873.2 1050.82  4908.4 1046.74  4916.2 1043.43
  4957.9 1041.08  4972.2 1038.09 4975.45 1034.72  4986.5 1025.15  4991.3 1024.14
  4994.1 1023.64  4997.3 1024.14  5021.7 1029.51  5050.3 1032.84  5099.8 1034.65
  5263.9 1040.71  5320.1 1045.48    5385 1060.14  5473.5 1100.09  5479.3 1100.09
    5507 1111.04  5549.3 1121.52  5635.2 1131.17  5726.3 1136.27  5788.9  1137.3
#Mann= 3 ,-1 , 0
  4271.3     .16       0  4991.3     .07       0  4997.3     .16       0
Bank Sta=4975.45,5099.8
XS Rating Curve= 0 ,0
Exp/Cntr=0.3,0.1

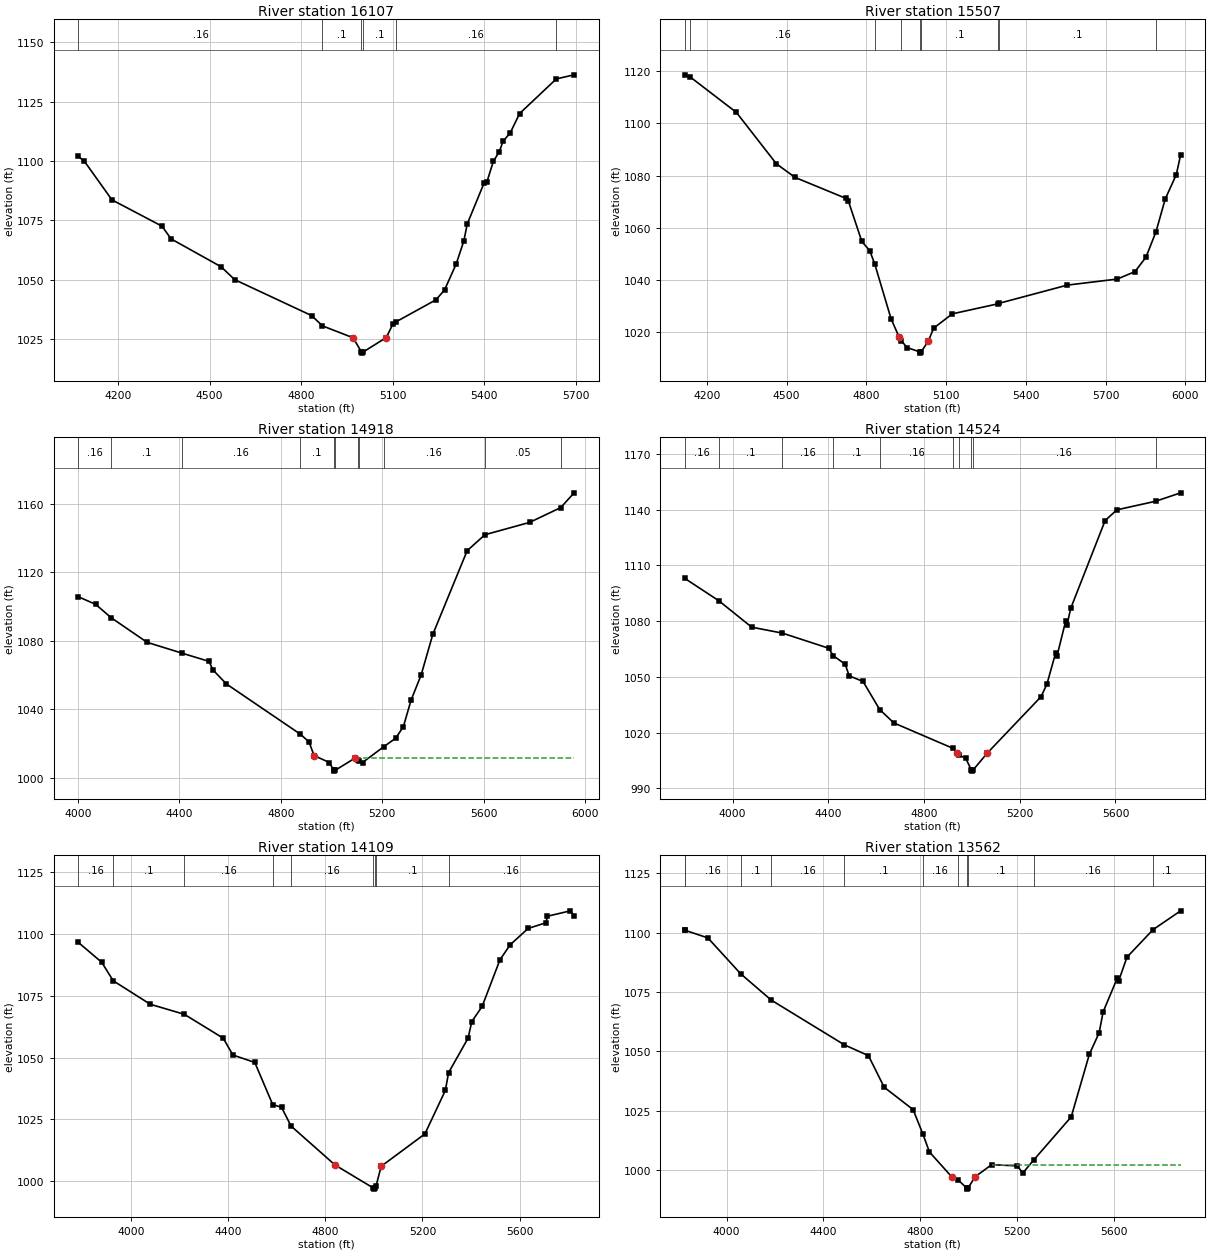
Type RM Length L Ch R = 1 ,16107   ,600,600,600
BEGIN DESCRIPTION:
SYCAMORE CREEK 31.0
END DESCRIPTION:
XS GIS Cut Line= 4
      2967249.85     10058688.03      2967905.22      10058436.3
      2968300.18     10058180.22      2968456.43     10057754.88
#Sta/Elev= 30
  4069.4 1101.91  4089.3 1099.88  4179.7 1083.61  4343.7 1072.52  4373.7 1067.15
  4537.7  1055.4  4582.1 1049.97  4834.7  1034.8  4870.2 1030.46  4970.6 1025.46
  4997.9 1019.48  5000.6 1018.98  5003.9 1019.48  5079.3 1025.54  5100.5 1031.08
  5112.3 1032.25  5242.2 1041.45  5270.4 1045.61  5308.7 1056.58  5333.8 1066.29
    5345 1073.47  5400.1  1090.7  5408.9 1090.95  5430.6 1099.87  5450.4 1103.97
  5462.1 1108.26  5486.2 1111.93  5516.7 1120.02    5637 1134.61  5695.3 1136.34
#Mann= 6 ,-1 , 0
  4069.4     .16       0  4870.2      .1       0  4997.9     .07       0
  5003.9      .1       0  5112.3     .16       0    5637      .1       0
Bank Sta=4970.6,5079.3
XS Rating Curve= 0 ,0
Exp/Cntr=0.3,0.1

Type RM Length L Ch R = 1 ,15507   ,589,589,589
BEGIN DESCRIPTION:
SYCAMORE CREEK 30.0
END DESCRIPTION:
XS GIS Cut Line= 4
      2967205.54     10058951.62      2967883.08     10058890.68
      2968291.77     10058876.34      2968495.89     10058127.89
#Sta/Elev= 30
  4117.1 1118.57  4135.9 1117.84  4310.8 1104.19  4461.4 1084.51  4531.7  1079.3
  4722.5  1071.3  4732.5 1070.15  4782.7  1054.8  4812.8 1051.22  4831.8 1046.01
  4892.8 1025.18  4922.8 1018.25  4930.7 1016.88  4952.9 1014.18  4999.9 1012.55
  5002.6 1012.05  5005.9 1012.55  5032.9 1016.64  5052.9  1021.6    5123 1027.08
    5296 1030.95  5299.2 1031.12  5555.5 1038.08  5743.8  1040.4  5810.2 1043.24
  5851.7 1048.76  5889.6 1058.58  5924.2 1071.05  5965.7 1080.34  5982.1 1087.92
#Mann= 9 ,-1 , 0
  4117.1      .1       0  4135.9     .16       0  4831.8     .05       0
  4930.7      .1       0  4999.9     .07       0  5005.9      .1       0
    5296     .16       0  5299.2      .1       0  5889.6     .16       0
Bank Sta=4922.8,5032.9
XS Rating Curve= 0 ,0
Exp/Cntr=0.3,0.1

Type RM Length L Ch R = 1 ,14918   ,394,394,394
BEGIN DESCRIPTION:
SYCAMORE CREEK 29.0
END DESCRIPTION:
XS GIS Cut Line= 3
      2967401.72     10059213.21      2968065.81     10059334.74
      2969337.49     10059200.19
#Sta/Elev= 30
    4002  1105.7  4069.9 1101.31  4131.8 1093.45  4273.2 1079.12  4408.9  1072.9
  4517.2 1068.02  4532.5 1063.06  4585.7 1054.86  4876.1 1025.68  4911.1  1021.1
  4931.2 1013.12  4991.5 1009.05  5008.6 1004.54  5011.4 1004.04  5014.6 1004.54
  5092.1  1011.6  5106.2 1010.46  5109.7    1010  5122.2 1009.07  5205.8 1018.27
    5253 1023.26  5283.1 1029.96  5313.3 1045.34  5353.5 1060.27  5399.1 1083.77
  5534.5 1132.56  5604.5 1141.87  5780.3 1149.04  5903.5  1157.7  5955.9  1166.3
#Mann= 11 ,-1 , 0
    4002     .16       0  4131.8      .1       0  4408.9     .16       0
  4876.1      .1       0  5008.6     .07       0  5014.6      .1       0
  5106.2     .05       0  5109.7      .1       0  5205.8     .16       0
  5604.5     .05       0  5903.5      .1       0
#XS Ineff= 2 , 0
                         5096.02         1011.43
Permanent Ineff=
       T       T
Bank Sta=4931.2,5092.1
XS Rating Curve= 0 ,0
Exp/Cntr=0.3,0.1

Type RM Length L Ch R = 1 ,14524   ,415,415,415
BEGIN DESCRIPTION:
SYCAMORE CREEK 28.0
END DESCRIPTION:
XS GIS Cut Line= 3
      2967423.45     10059291.34      2968339.24       10059708.
      2969375.05     10059456.63
#Sta/Elev= 30
  3800.3 1102.94  3941.9 1090.98  4079.4 1076.75    4208 1073.55  4401.1 1065.43
  4420.7 1061.38  4470.3 1056.82    4487 1050.59    4545 1047.54  4614.6 1032.43
  4673.7 1025.26  4921.9 1011.53  4939.4 1008.99  4947.3 1007.94  4974.2 1006.19
  4998.1  999.84  5000.9  999.34  5004.1  999.84  5062.9 1008.86  5289.3 1039.44
  5313.6 1046.19  5350.2 1063.04  5355.4 1061.15    5392 1080.16  5397.1 1077.75
  5412.7 1086.79  5556.8  1134.1  5606.1 1139.85    5768 1144.46  5872.3 1148.99
#Mann= 10 ,-1 , 0
  3800.3     .16       0  3941.9      .1       0    4208     .16       0
  4420.7      .1       0  4614.6     .16       0  4921.9     .05       0
  4947.3     .16       0  4998.1     .07       0  5004.1     .16       0
    5768      .1       0
Bank Sta=4939.4,5062.9
XS Rating Curve= 0 ,0
Exp/Cntr=0.3,0.1

Type RM Length L Ch R = 1 ,14109   ,547,547,547
BEGIN DESCRIPTION:
SYCAMORE CREEK 26.0
END DESCRIPTION:
XS GIS Cut Line= 3
      2967332.34      10060063.9      2968842.72     10060076.93
      2969293.81     10059799.33
#Sta/Elev= 30
  3783.7 1096.57  3879.8 1088.55  3927.3 1081.05  4079.8 1071.55  4220.2 1067.47
  4379.9 1057.83  4419.9 1051.01  4509.9 1048.01  4583.6 1030.97  4619.9 1029.87
  4659.3 1022.26  4839.9 1006.54  4996.9  997.26  4999.6  996.76  5002.9  997.26
  5009.3  998.14  5029.9 1005.99  5209.9 1019.09  5294.1  1036.7  5307.4 1043.88
  5387.5 1057.82  5402.9 1064.53  5445.5 1070.68  5518.9 1089.57  5561.4 1095.67
  5634.8 1102.22  5708.2 1104.53  5714.1 1107.16  5808.8 1109.35  5823.8 1107.27
#Mann= 9 ,-1 , 0
  3783.7     .16       0  3927.3      .1       0  4220.2     .16       0
  4583.6     .05       0  4659.3     .16       0  4996.9     .07       0
  5002.9     .16       0  5009.3      .1       0  5307.4     .16       0
Bank Sta=4839.9,5029.9
XS Rating Curve= 0 ,0
Exp/Cntr=0.3,0.1

Type RM Length L Ch R = 1 ,13562   ,463,463,463
BEGIN DESCRIPTION:
SYCAMORE CREEK 25.0
END DESCRIPTION:
XS GIS Cut Line= 3
      2967267.18     10060259.21      2968781.95     10060693.24
       2969237.7     10060571.71
#Sta/Elev= 30
  3827.6 1100.97  3827.8 1100.97  3922.6 1097.74  4057.9 1082.66  4184.1 1071.59
    4486 1052.78  4585.7 1048.21  4650.7 1034.92  4770.1 1025.51  4810.3 1015.28
  4837.6 1007.69  4931.6  997.01  4954.8  996.04    4991  992.56  4993.8  992.06
    4997  992.56  5027.2  997.34  5094.7 1002.35  5201.1 1001.84  5222.9   998.8
  5267.6 1004.23  5423.2 1022.48  5498.2 1048.85  5538.4 1057.81    5555 1066.65
  5613.4 1080.82  5618.6 1079.53  5653.5 1089.66    5761 1101.22    5875 1109.14
#Mann= 11 ,-1 , 0
  3827.6      .1       0  3827.8     .16       0  4057.9      .1       0
  4184.1     .16       0    4486      .1       0  4810.3     .16       0
  4954.8      .1       0    4991     .07       0    4997      .1       0
  5267.6     .16       0    5761      .1       0
#XS Ineff= 2 , 0
                         5094.47         1002.34
Permanent Ineff=
       T       T
Bank Sta=4931.6,5027.2
XS Rating Curve= 0 ,0
Exp/Cntr=0.3,0.1

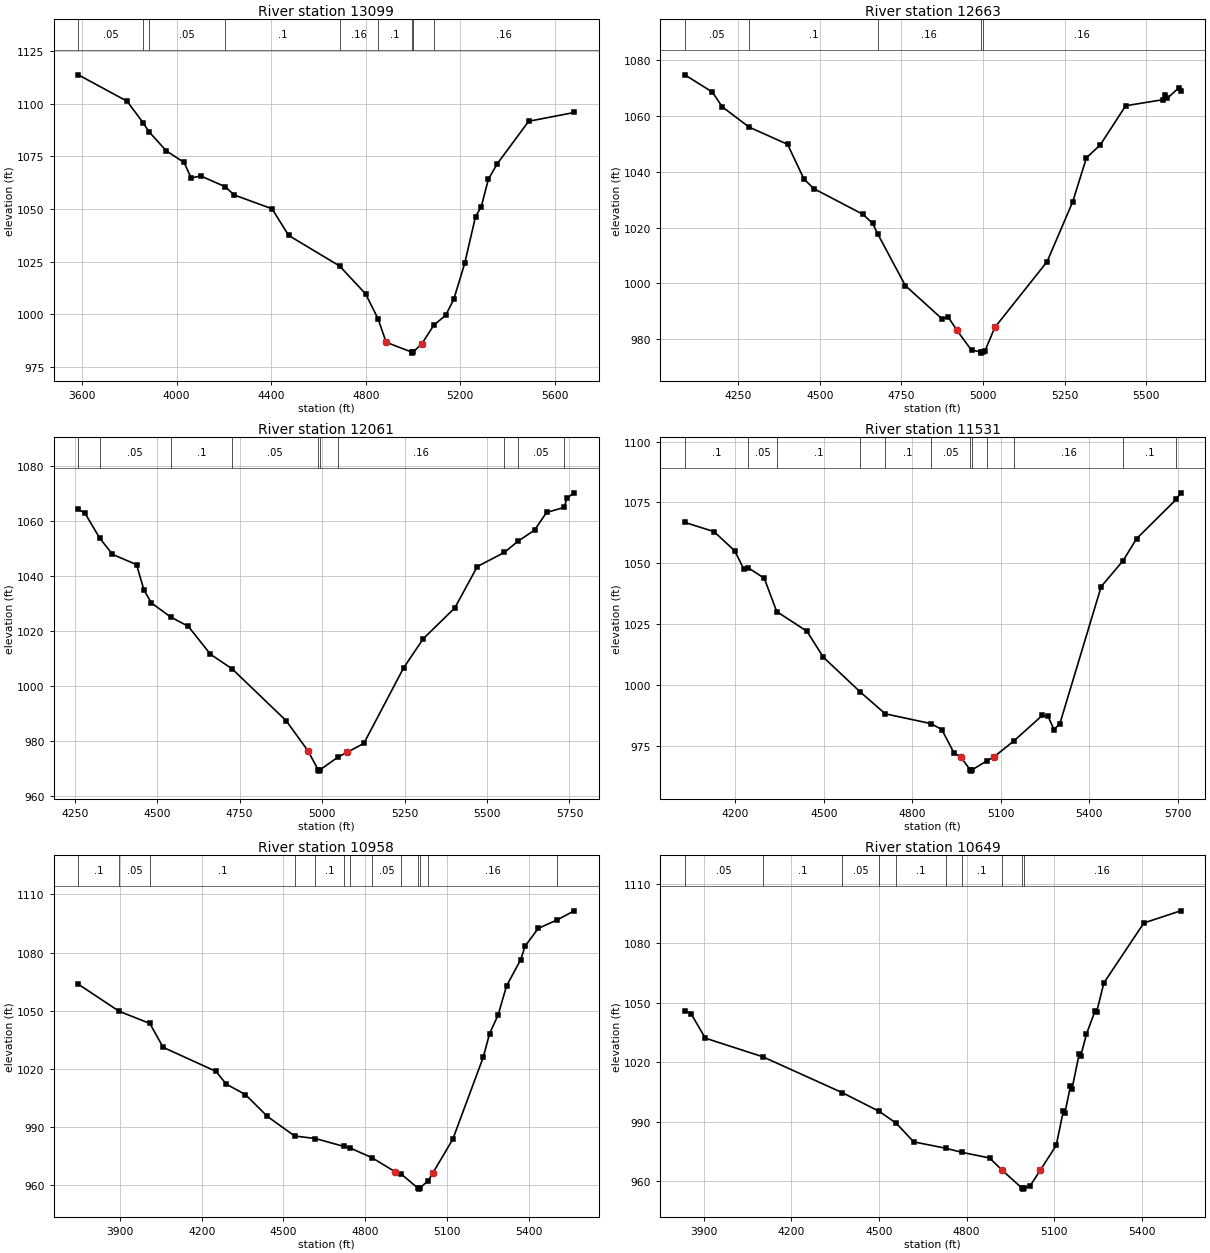
Type RM Length L Ch R = 1 ,13099   ,436,436,436
BEGIN DESCRIPTION:
SYCAMORE CREEK 24.0
END DESCRIPTION:
XS GIS Cut Line= 3
      2967123.96     10061118.59       2968938.2     10060923.28
      2969179.98     10060798.07
#Sta/Elev= 30
  3584.4 1113.73  3790.1 1101.23  3858.9  1090.9    3883 1086.73  3956.4 1077.62
  4031.5 1072.11  4061.6 1064.74  4101.9  1065.7  4206.7 1060.54  4242.7  1056.7
  4403.6  1050.1    4474 1037.44  4689.4 1022.93  4799.3 1009.69  4851.8  997.91
  4886.2   986.7    4994  982.04  4996.8  981.54    5000  982.04  5037.2  985.97
  5088.1  994.87  5137.8  999.49  5172.2 1007.06  5218.3 1024.12  5264.2 1046.36
  5288.7 1051.14  5318.9 1064.24  5356.1 1071.46  5489.1 1091.67  5681.4 1095.84
#Mann= 9 ,-1 , 0
  3584.4     .05       0  3858.9     .16       0    3883     .05       0
  4206.7      .1       0  4689.4     .16       0  4851.8      .1       0
    4994     .07       0    5000      .1       0  5088.1     .16       0
Bank Sta=4886.2,5037.2
XS Rating Curve= 0 ,0
Exp/Cntr=0.3,0.1

Type RM Length L Ch R = 1 ,12663   ,602,602,602
BEGIN DESCRIPTION:
SYCAMORE CREEK 23.0
END DESCRIPTION:
XS GIS Cut Line= 4
      2967714.28     10061435.43      2968421.71     10061392.03
      2968790.63     10061322.59      2969114.84     10061032.96
#Sta/Elev= 30
  4086.4 1074.81  4170.7 1068.63  4200.8 1063.36    4283 1056.06  4401.2 1049.86
  4451.3 1037.44  4481.3 1033.97  4631.6 1024.77  4661.7 1021.53  4677.5 1017.68
  4761.9  999.17  4873.3  987.33  4893.6  987.81  4920.1  983.08  4964.8  975.94
  4992.4  975.41  4995.1  974.91  4998.4  975.41  5005.6  975.64  5036.1  984.13
  5196.3 1007.75  5274.8 1029.27  5316.7 1045.01  5359.3 1049.68    5437 1063.71
  5550.7 1065.88  5557.4 1067.56  5564.9 1066.41    5600  1070.2  5605.3 1068.95
#Mann= 5 ,-1 , 0
  4086.4     .05       0    4283      .1       0  4677.5     .16       0
  4992.4     .07       0  4998.4     .16       0
Bank Sta=4920.1,5036.1
XS Rating Curve= 0 ,0
Exp/Cntr=0.3,0.1

Type RM Length L Ch R = 1 ,12061   ,530,530,530
BEGIN DESCRIPTION:
SYCAMORE CREEK 22.0
END DESCRIPTION:
XS GIS Cut Line= 4
      2968230.72     10062294.82      2968729.87     10062047.41
      2969011.99     10061669.81      2969459.06     10061509.21
#Sta/Elev= 30
  4260.8 1064.28  4280.6 1062.96  4325.4 1053.86  4364.4 1047.91  4437.3 1044.16
  4459.7 1034.96  4482.1 1030.26  4540.6 1025.11  4594.2 1021.72  4661.5 1011.53
  4726.9 1006.26  4890.9  987.37 4957.27  976.37    4988  969.51  4990.7  969.01
    4994  969.51  5049.1  974.19  5076.5  975.89  5126.5   979.1  5247.4 1006.65
  5306.8 1017.21  5402.4 1028.41  5470.7 1043.48  5552.7 1048.61  5593.1 1052.61
  5644.4 1056.75  5680.5 1063.16  5734.1 1064.99  5742.4 1068.35  5764.3  1070.3
#Mann= 10 ,-1 , 0
  4260.8      .1       0  4325.4     .05       0  4540.6      .1       0
  4726.9     .05       0    4988    .035       0    4994     .05       0
  5049.1     .16       0  5552.7      .1       0  5593.1     .05       0
  5734.1      .1       0
Bank Sta=4957.27,5076.5
XS Rating Curve= 0 ,0
Exp/Cntr=0.3,0.1

Type RM Length L Ch R = 1 ,11531   ,573,573,573
BEGIN DESCRIPTION:
SYCAMORE CREEK 21.0
END DESCRIPTION:
XS GIS Cut Line= 4
      2968259.42     10062483.17      2968962.51     10062441.51
      2969316.67     10062170.68      2969847.88     10062175.88
#Sta/Elev= 30
  4028.8 1066.79    4128 1063.01  4198.1  1055.1  4228.2  1047.8  4244.6  1048.1
  4298.3 1043.83  4340.5 1030.16  4442.8 1022.09  4498.7  1011.4  4624.5  997.05
  4708.7  988.14  4863.5  984.13  4900.1   981.7    4942  972.02  4964.5   970.4
  4996.9   965.1  4999.6   964.6  5002.9   965.1  5054.4  968.92  5078.8  970.61
  5145.2  977.05  5240.8  987.46  5260.8  987.06  5280.8  981.67  5300.8  984.14
  5440.8 1040.44  5515.1 1051.07  5560.8 1060.12  5695.5 1076.27  5710.2 1078.95
#Mann= 12 ,-1 , 0
  4028.8      .1       0  4244.6     .05       0  4340.5      .1       0
  4624.5     .05       0  4708.7      .1       0  4863.5     .05       0
  4996.9    .035       0  5002.9     .05       0  5054.4      .1       0
  5145.2     .16       0  5515.1      .1       0  5695.5     .16       0
Bank Sta=4964.5,5078.8
XS Rating Curve= 0 ,0
Exp/Cntr=0.3,0.1

Type RM Length L Ch R = 1 ,10958   ,309,309,309
BEGIN DESCRIPTION:
SYCAMORE CREEK 20.0
END DESCRIPTION:
XS GIS Cut Line= 4
      2968269.76      10062686.3       2969144.8     10062795.68
      2969873.97     10062587.34      2970008.71     10062468.14
#Sta/Elev= 30
  3747.1 1063.65  3896.5 1049.72  4009.7 1043.41  4058.2 1031.12  4252.6 1018.67
    4290 1012.13  4360.5 1006.73  4441.2  995.45  4541.3  985.37  4617.2  984.07
  4720.5  980.05  4745.1  979.17  4824.3  974.23  4908.7  967.04  4931.5  965.83
  4993.8  958.47  4996.5  957.97  4999.8  958.47  5032.1  962.37  5048.8  966.37
  5121.6  983.68  5233.7 1026.08  5256.8  1038.2    5288 1047.77  5319.2 1062.85
  5371.2 1076.36    5387 1083.27  5435.3 1092.43  5505.7 1096.88  5567.2  1101.5
#Mann= 13 ,-1 , 0
  3747.1      .1       0  3896.5     .05       0  4009.7      .1       0
  4541.3     .05       0  4617.2      .1       0  4720.5     .16       0
  4745.1      .1       0  4824.3     .05       0  4931.5      .1       0
  4993.8     .07       0  4999.8      .1       0  5032.1     .16       0
  5505.7      .1       0
Bank Sta=4908.7,5048.8
XS Rating Curve= 0 ,0
Exp/Cntr=0.3,0.1

Type RM Length L Ch R = 1 ,10649   ,382,382,382
BEGIN DESCRIPTION:
SYCAMORE CREEK 19.0
END DESCRIPTION:
XS GIS Cut Line= 4
      2968457.27     10063217.55      2969238.55      10063123.8
      2969868.76     10062879.01      2970050.59     10062728.35
#Sta/Elev= 30
  3834.5 1046.11  3855.8  1044.5  3904.9 1032.15    4101 1022.79    4373 1004.68
  4500.5  995.18  4559.3  989.13  4618.8  979.73  4728.8  976.51  4783.9  974.45
  4878.7   971.6  4921.6  965.48  4989.9  956.35  4992.7  955.85  4995.9  956.35
  5017.5  957.42  5052.7   965.4  5107.2  977.93  5131.7  995.36  5137.1  994.43
  5156.2 1008.01  5161.6 1006.66  5186.1 1024.27  5191.5 1023.23  5210.7 1034.13
  5240.6 1046.02  5245.9 1045.39  5270.5 1060.06  5407.5 1090.36  5533.6 1096.51
#Mann= 10 ,-1 , 0
  3834.5     .05       0    4101      .1       0    4373     .05       0
  4500.5     .16       0  4559.3      .1       0  4728.8     .05       0
  4783.9      .1       0  4921.6     .16       0  4989.9     .07       0
  4995.9     .16       0
Bank Sta=4921.6,5052.7
XS Rating Curve= 0 ,0
Exp/Cntr=0.3,0.1