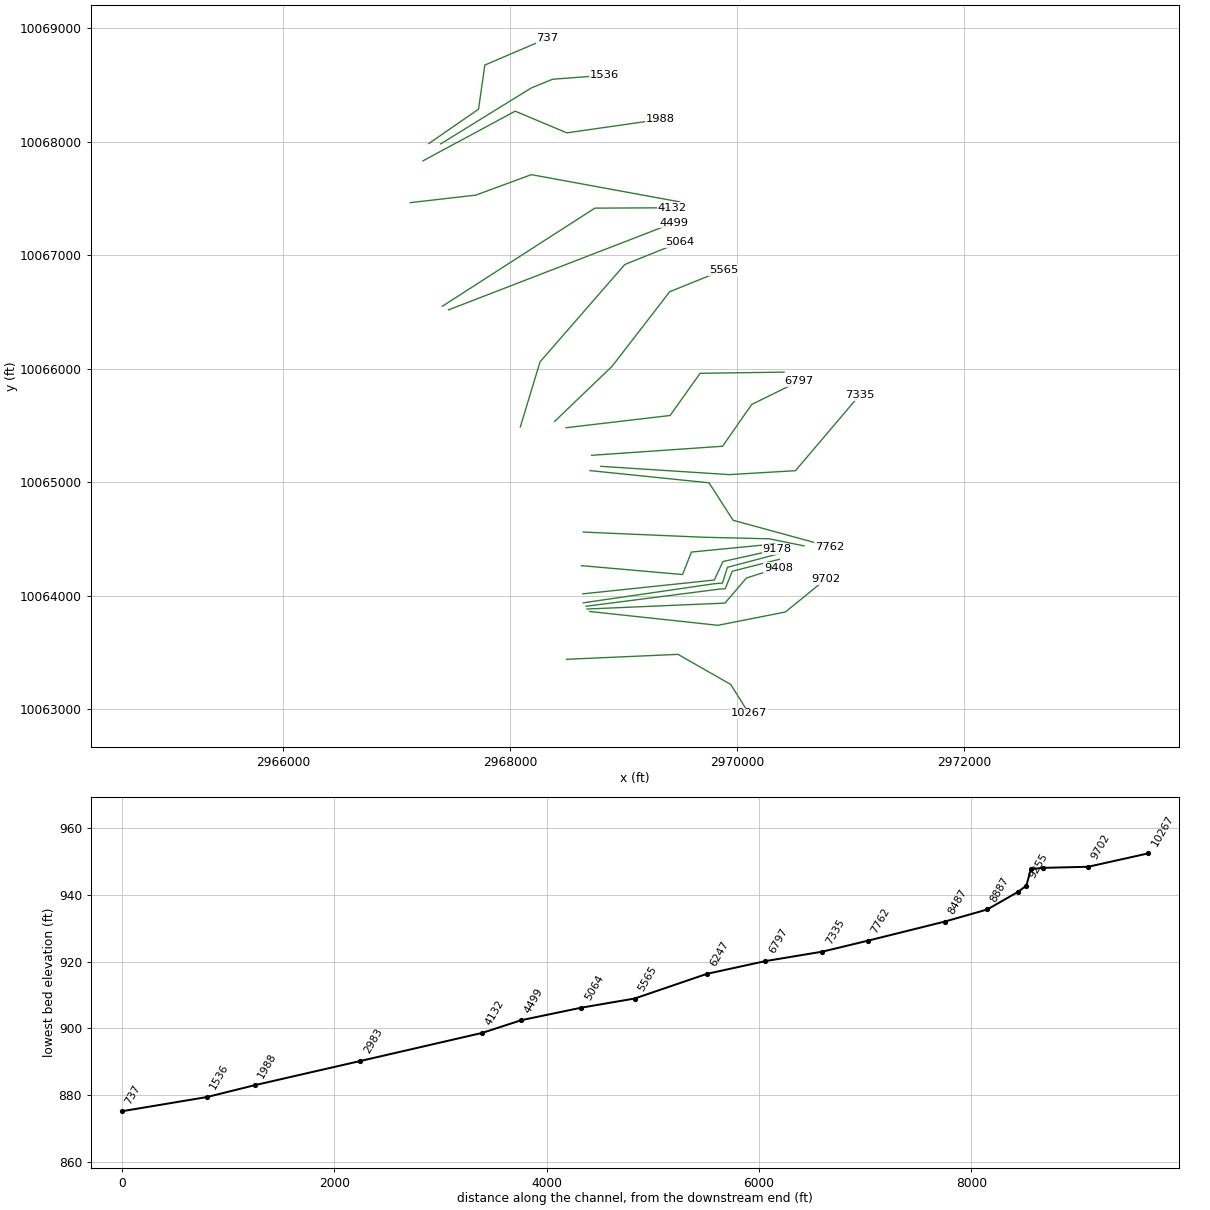
HEC-RAS study SYCAMORE CREEK.prj: SYCAMORE CREEK Base Level Engineering

--- SYCAMORE CREEK.g01 (geometry) --- (continued)

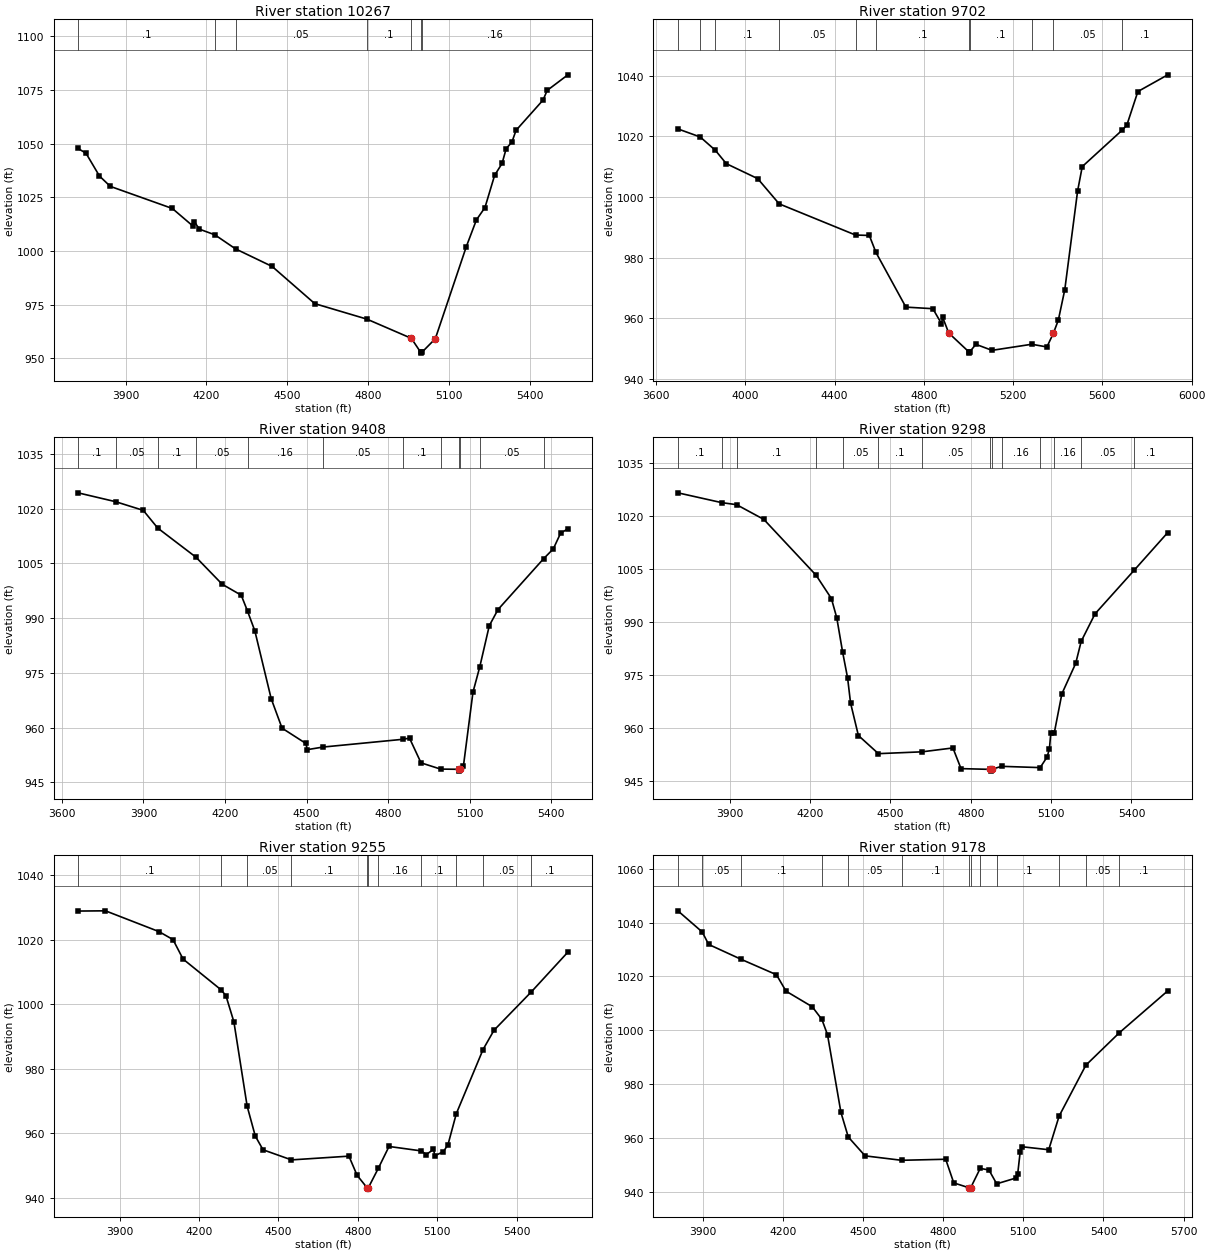
Type RM Length L Ch R = 1 ,10267   ,565,565,565
BEGIN DESCRIPTION:
SYCAMORE CREEK 18.0
END DESCRIPTION:
XS GIS Cut Line= 4
      2968498.92     10063439.77      2969479.87     10063483.18
      2969944.28     10063218.42      2970104.15     10062963.49
#Sta/Elev= 30
  3723.5 1047.74  3753.1 1045.52  3803.1 1034.89  3843.2 1030.09  4073.4 1019.79
  4150.5 1011.53  4155.5 1013.56  4173.5 1010.17  4231.2 1007.52  4307.8 1000.98
  4443.8  992.78  4601.9  975.46  4795.2  968.25  4959.7  959.33  4960.2   959.3
  4994.2  952.91  4996.9  952.41  5000.2  952.91  5049.1  959.12  5164.3 1002.08
  5201.7  1014.5  5233.3 1020.23  5269.1 1035.22  5296.8 1040.78  5312.1  1047.7
  5333.3 1050.72  5348.6 1056.19  5448.8 1070.29  5464.1 1074.78  5540.9 1082.05
#Mann= 7 ,-1 , 0
  3723.5      .1       0  4231.2     .16       0  4307.8     .05       0
  4795.2      .1       0  4960.2     .16       0  4994.2     .07       0
  5000.2     .16       0
Bank Sta=4959.7,5049.1
XS Rating Curve= 0 ,0
Exp/Cntr=0.3,0.1

Type RM Length L Ch R = 1 ,9702    ,429,429,429
BEGIN DESCRIPTION:
SYCAMORE CREEK 17.0
END DESCRIPTION:
XS GIS Cut Line= 4
      2968702.95     10063860.78      2969831.43     10063739.25
      2970426.05     10063856.44      2970777.65     10064142.93
#Sta/Elev= 30
  3698.2 1022.49  3798.3 1019.82  3865.9 1015.43    3915 1011.01  4055.8 1006.06
  4151.9  997.73  4493.9  987.43  4555.8  987.29  4585.6  981.66  4719.6  963.61
  4840.4  963.09  4879.1  958.15  4884.2  960.26  4911.7  955.05  5000.5  948.91
  5003.2  948.41  5006.5  948.91  5033.2  951.32  5105.4  949.33  5283.6  951.34
  5351.4  950.45  5380.2  954.93  5402.7  959.34  5431.5  969.36    5489    1002
  5509.8 1010.04  5689.2 1022.12  5709.4 1023.71    5759 1034.84  5892.8 1040.36
#Mann= 11 ,-1 , 0
  3698.2      .1       0  3798.3     .05       0  3865.9      .1       0
  4151.9     .05       0  4493.9     .16       0  4585.6      .1       0
  5000.5     .07       0  5006.5      .1       0  5283.6     .16       0
  5380.2     .05       0  5689.2      .1       0
Bank Sta=4911.7,5380.2
XS Rating Curve= 0 ,0
Exp/Cntr=0.3,0.1

Type RM Length L Ch R = 1 ,9408    ,110,110,110
BEGIN DESCRIPTION:
Mapping XS b3df0c54
END DESCRIPTION:
XS GIS Cut Line= 4
      2968678.91     10063882.75      2969894.14     10063934.83
      2970081.64     10064155.32      2970362.92     10064245.61
#Sta/Elev= 30
  3659.7  1024.3    3798 1021.87  3899.5  1019.5  3952.9 1014.64  4093.5 1006.66
  4189.7  999.27  4259.8  996.26    4283   991.9  4309.9  986.48  4369.9  967.94
  4409.9  959.85  4497.5  955.66  4502.5  953.96  4560.3  954.67    4856  956.81
  4878.6  957.12  4920.9  950.35  4992.7  948.64  5059.6  948.58  5062.3  948.08
  5065.6  948.58  5076.9   949.5    5112  969.72  5136.7  976.56    5172  987.92
  5204.1  992.34  5372.2  1006.3  5407.3 1008.94  5434.2 1013.25  5460.9 1014.44
#Mann= 12 ,-1 , 0
  3659.7      .1       0    3798     .05       0  3952.9      .1       0
  4093.5     .05       0    4283     .16       0  4560.3     .05       0
    4856      .1       0  4992.7     .16       0  5059.6     .07       0
  5065.6     .16       0  5136.7     .05       0  5372.2      .1       0
Bank Sta=5059.6,5065.6
XS Rating Curve= 0 ,0
Exp/Cntr=0.3,0.1

Type RM Length L Ch R = 1 ,9298    ,43,43,43
BEGIN DESCRIPTION:
Mapping XS 48f367e1
END DESCRIPTION:
XS GIS Cut Line= 5
      2968670.16     10063907.05      2969852.19     10064059.03
      2969895.66     10064060.92      2969957.91     10064215.57
      2970371.59     10064320.26
#Sta/Elev= 30
  3706.7 1026.67  3869.9 1023.89  3925.7 1023.31  4027.6 1019.12  4222.5 1003.29
  4279.7  996.67  4299.8   991.2  4321.5  981.51  4340.2  974.14  4351.3     967
  4380.5  957.79  4455.2  952.64  4618.3  953.16  4733.4  954.26  4763.6  948.39
  4871.5  948.18  4874.3  947.68  4877.5  948.18    4915  949.04  5059.1  948.68
  5085.1  951.69  5093.7  954.05    5099  958.59  5111.6  958.45  5140.2  969.63
  5191.8  978.27  5212.3  984.53    5264  992.33  5410.7 1004.75  5535.4 1015.39
#Mann= 14 ,-1 , 0
  3706.7      .1       0  3869.9     .05       0  3925.7      .1       0
  4222.5     .16       0  4321.5     .05       0  4455.2      .1       0
  4618.3     .05       0  4871.5     .07       0  4877.5     .05       0
    4915     .16       0  5059.1      .1       0  5111.6     .16       0
  5212.3     .05       0  5410.7      .1       0
Bank Sta=4871.5,4877.5
XS Rating Curve= 0 ,0
Exp/Cntr=0.3,0.1

Type RM Length L Ch R = 1 ,9255    ,77,77,77
BEGIN DESCRIPTION:
Mapping XS 28ceafcd
END DESCRIPTION:
XS GIS Cut Line= 5
      2968645.83     10063937.43      2969802.13     10064105.84
      2969871.57     10064111.05      2969914.97     10064249.94
      2970366.23     10064369.23
#Sta/Elev= 30
  3742.9 1028.92  3846.6 1028.99  4048.7 1022.55  4101.6 1020.08  4139.7 1014.04
  4282.7 1004.55  4301.4 1002.73  4331.7  994.58  4381.8  968.43  4412.5  959.19
  4441.8  954.94  4549.2  951.81  4766.2  952.97  4797.1  947.03    4834  943.25
  4836.7  942.75    4840  943.25  4877.3  949.21  4917.7  955.97  5040.1  954.59
  5058.4  953.45  5085.7  955.08  5090.9  953.07  5123.4  954.39  5140.5  956.55
  5171.9  966.14  5272.9  986.01  5314.3  991.99  5455.9 1003.93  5593.3 1016.19
#Mann= 11 ,-1 , 0
  3742.9      .1       0  4282.7     .16       0  4381.8     .05       0
  4549.2      .1       0    4834     .07       0    4840      .1       0
  4877.3     .16       0  5040.1      .1       0  5171.9     .16       0
  5272.9     .05       0  5455.9      .1       0
Bank Sta=4834,4840
XS Rating Curve= 0 ,0
Exp/Cntr=0.3,0.1

Type RM Length L Ch R = 1 ,9178    ,291,291,291
BEGIN DESCRIPTION:
SYCAMORE CREEK 16.0
END DESCRIPTION:
XS GIS Cut Line= 4
      2968641.55     10064016.43      2969799.52     10064137.96
      2969875.91     10064301.15      2970353.38     10064407.06
#Sta/Elev= 30
  3806.9  1044.4  3897.8 1036.55  3922.1  1031.9  4044.1 1026.35  4175.8 1020.64
  4211.6 1014.53  4309.8 1008.73  4345.8 1004.03  4366.9  998.34  4417.2  969.42
  4444.6  960.31  4507.6  953.29  4644.2  951.64  4809.3  952.03  4839.5  943.24
  4896.8  941.42  4899.5  940.92  4902.8  941.42  4938.5  948.63  4971.2  948.04
  5000.2  942.89  5073.2  945.08  5078.7  946.46    5088  954.64    5096  956.67
    5195  955.57  5233.9  968.08    5334     987  5459.4  999.07  5640.5 1014.64
#Mann= 13 ,-1 , 0
  3806.9      .1       0  3897.8     .05       0  4044.1      .1       0
  4345.8     .16       0  4444.6     .05       0  4644.2      .1       0
  4896.8     .07       0  4902.8      .1       0  4938.5     .16       0
  5000.2      .1       0  5233.9     .16       0    5334     .05       0
  5459.4      .1       0
Bank Sta=4896.8,4902.8
XS Rating Curve= 0 ,0
Exp/Cntr=0.3,0.1

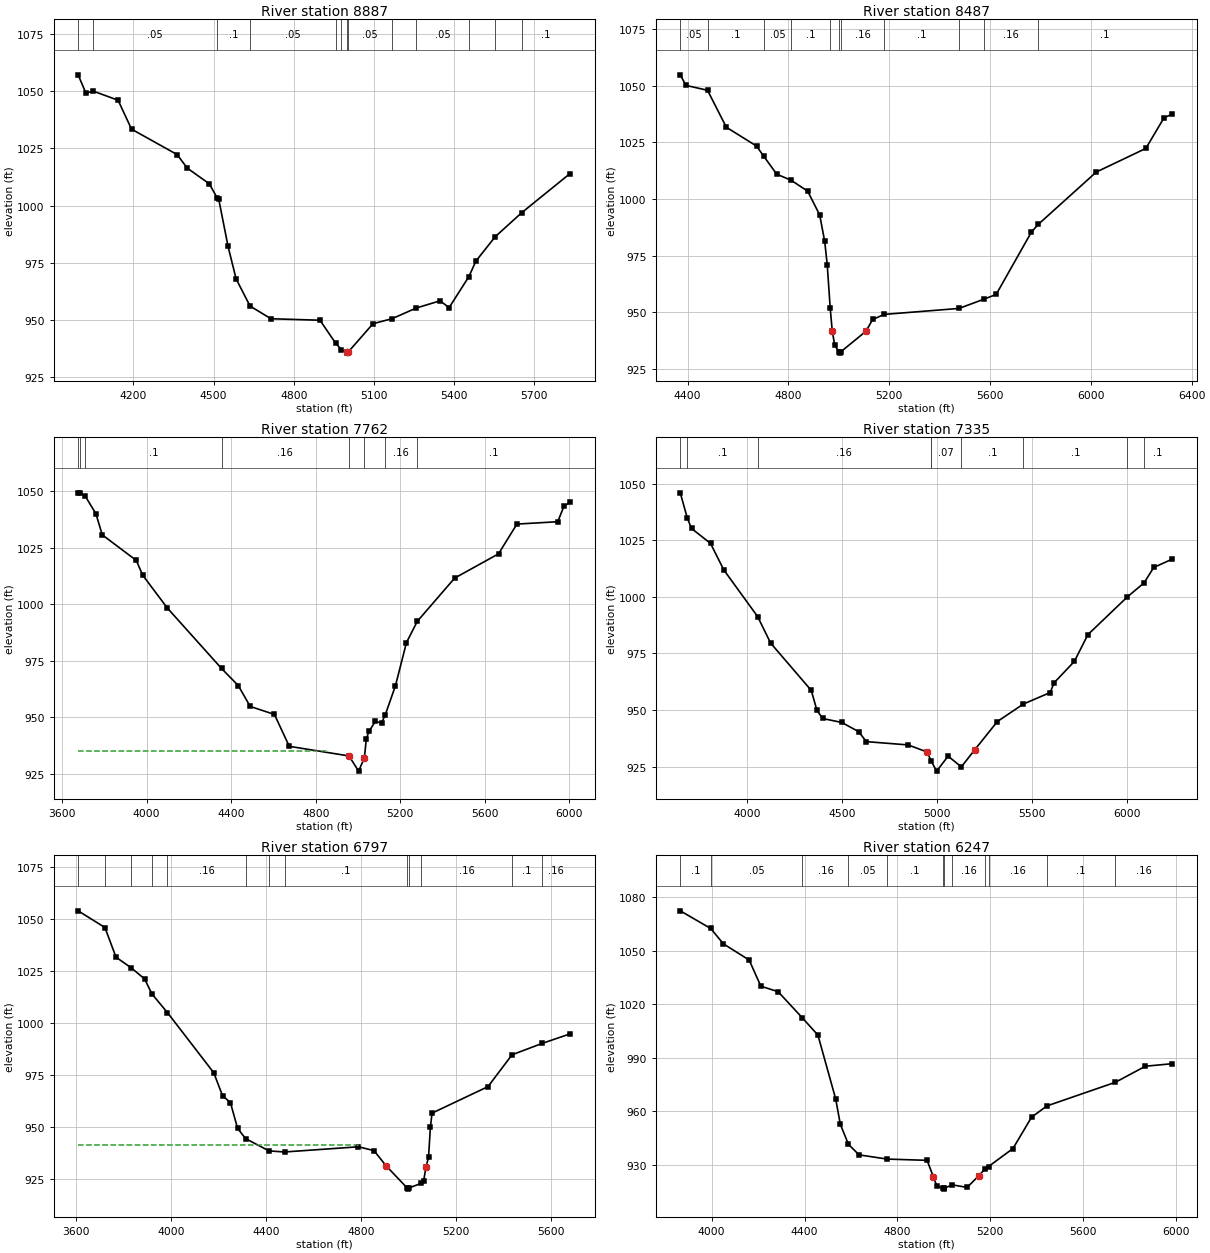
Type RM Length L Ch R = 1 ,8887    ,400,400,400
BEGIN DESCRIPTION:
SYCAMORE CREEK 15.0
END DESCRIPTION:
XS GIS Cut Line= 4
      2968629.41     10064264.69      2969520.01     10064186.57
      2969598.13     10064384.49      2970329.08     10064455.67
#Sta/Elev= 30
  3993.1  1057.1  4022.3 1049.06  4048.6 1050.03  4142.7 1046.01  4192.9 1033.39
  4363.6 1022.29  4401.7 1016.37    4484 1009.54  4513.8 1003.33  4519.1    1003
  4554.3  982.18  4584.4  968.04  4636.6  956.17  4714.9  950.63  4898.4  949.98
  4956.7     940  4978.7  937.12  4998.2  936.12    5001  935.62  5004.2  936.12
  5096.8  948.46  5168.5  950.66  5258.2  955.28  5348.2  958.47  5381.6  955.45
  5455.6  968.98    5482  975.79  5554.4  986.44  5653.1  996.88  5834.3 1013.99
#Mann= 13 ,-1 , 0
  3993.1      .1       0  4048.6     .05       0  4513.8      .1       0
  4636.6     .05       0  4956.7      .1       0  4978.7     .05       0
  4998.2    .035       0  5004.2     .05       0  5168.5      .1       0
  5258.2     .05       0  5455.6      .1       0  5554.4     .16       0
  5653.1      .1       0
Bank Sta=4998.2,5004.2
XS Rating Curve= 0 ,0
Exp/Cntr=0.3,0.1

Type RM Length L Ch R = 1 ,8487    ,725,725,725
BEGIN DESCRIPTION:
SYCAMORE CREEK 14.0
END DESCRIPTION:
XS GIS Cut Line= 4
      2968645.82     10064560.29      2969697.92     10064515.15
      2970284.73     10064501.26      2970590.26     10064438.76
#Sta/Elev= 30
  4370.6 1054.81  4393.3 1050.15  4478.8 1047.99  4553.4 1031.69  4673.5 1023.36
  4701.7  1018.9  4753.6 1010.96    4810 1008.32  4876.1 1003.48  4923.8  993.01
  4943.8  981.32  4953.8  971.08  4965.5  952.09  4973.8  941.63  4983.8  935.42
  5000.8   932.5  5003.6     932  5006.8   932.5  5107.8  941.68    5134  946.84
  5179.9  949.09  5476.6  951.72  5575.4  955.79  5624.3  957.91  5764.3  985.46
  5791.3  988.82  6021.4  1011.9  6218.2 1022.34    6290 1035.79  6322.5 1037.51
#Mann= 11 ,-1 , 0
  4370.6     .05       0  4478.8      .1       0  4701.7     .05       0
    4810      .1       0  4965.5     .16       0  5000.8     .07       0
  5006.8     .16       0  5179.9      .1       0  5476.6     .05       0
  5575.4     .16       0  5791.3      .1       0
Bank Sta=4973.8,5107.8
XS Rating Curve= 0 ,0
Exp/Cntr=0.3,0.1

Type RM Length L Ch R = 1 ,7762    ,427,427,427
BEGIN DESCRIPTION:
SYCAMORE CREEK 13.0
END DESCRIPTION:
XS GIS Cut Line= 4
      2968704.91     10065101.95      2969753.48     10064994.31
      2969965.28     10064664.45      2970814.71     10064432.16
#Sta/Elev= 30
  3676.1 1049.36  3683.5 1049.32  3710.7 1047.75  3760.1 1040.12  3790.3 1030.77
  3951.1 1019.47  3981.3 1012.96  4098.1   998.4  4354.4  971.68  4433.6  964.11
    4490  954.88  4604.5  951.35  4674.9  937.24  4957.4  932.98  5002.8  926.27
  5030.1  932.11  5039.4  940.61  5051.7   943.8  5081.6  948.24  5111.2  947.55
  5128.9  951.16    5177  964.02  5229.2  983.12  5280.3  992.51  5457.2 1011.65
  5664.6 1022.37  5751.6 1035.54  5944.8 1036.58  5974.2 1043.46  6002.8 1045.14
#Mann= 8 ,-1 , 0
  3676.1     .16       0  3683.5     .05       0  3710.7      .1       0
  4354.4     .16       0  4957.4     .07       0  5030.1      .1       0
  5128.9     .16       0  5280.3      .1       0
#XS Ineff= 2 , 0
         4849.58  935.32
Permanent Ineff=
       T       T
Bank Sta=4957.4,5030.1
XS Rating Curve= 0 ,0
Exp/Cntr=0.3,0.1

Type RM Length L Ch R = 1 ,7335    ,538,538,538
BEGIN DESCRIPTION:
SYCAMORE CREEK 12.0
END DESCRIPTION:
XS GIS Cut Line= 4
      2968799.32     10065139.43      2969931.26     10065066.51
      2970514.59     10065101.23      2971080.59     10065767.93
#Sta/Elev= 30
  3645.9 1045.93    3683 1034.81  3705.2 1030.19  3805.4  1023.6  3875.5 1011.88
    4054  991.25  4122.2  979.58  4336.5  958.66  4366.5  949.84  4396.6  946.25
  4496.8  944.51    4586  940.47  4627.1  936.03  4847.5  934.57  4947.7  931.44
  4967.7  927.62  4997.5     923  5057.9  929.61    5128  924.89  5198.1   932.4
  5317.9  944.92  5454.3  952.61    5596  957.71  5617.1  962.05  5723.4  971.43
  5794.8  983.28  6003.4  999.99  6091.5 1006.18  6141.9 1012.96  6239.1 1016.63
#Mann= 9 ,-1 , 0
  3645.9     .05       0    3683      .1       0    4054     .16       0
  4967.7     .05       0  4967.7     .07       0    5128      .1       0
  5454.3      .1       0  6003.4     .05       0  6091.5      .1       0
Bank Sta=4947.7,5198.1
XS Rating Curve= 0 ,0
Exp/Cntr=0.3,0.1

Type RM Length L Ch R = 1 ,6797    ,550,550,550
BEGIN DESCRIPTION:
SYCAMORE CREEK 11.0
END DESCRIPTION:
XS GIS Cut Line= 4
       2968719.4     10065236.64      2969872.23     10065316.51
      2970129.17     10065684.56      2970545.87     10065889.44
#Sta/Elev= 30
  3610.6 1053.73  3723.3 1045.72    3770 1031.46  3834.6 1026.32  3890.3 1021.02
  3920.5 1013.92  3986.1  1004.9    4181  976.02  4217.8  965.05  4251.2  961.66
  4281.3  949.31    4315   944.4  4413.6   938.5  4478.7  937.99  4789.6  940.48
    4855  938.64  4905.6  931.38    4995  920.66  4997.8  920.16    5001  920.66
  5051.6  922.87  5063.5  923.98 5073.86  930.86  5084.4  935.53  5092.1  949.78
  5099.2  956.64  5334.6  969.37  5435.5  984.64  5561.8  990.08  5679.4  994.67
#Mann= 13 ,-1 , 0
  3610.6     .16       0  3723.3      .1       0  3834.6     .05       0
  3920.5      .1       0  3986.1     .16       0    4315      .1       0
  4413.6     .05       0  4478.7      .1       0    4995     .07       0
    5001      .1       0  5051.6     .16       0  5435.5      .1       0
  5561.8     .16       0
#XS Ineff= 2 , 0
         4789.77  941.55
Permanent Ineff=
       T       T
Bank Sta=4905.6,5073.86
XS Rating Curve= 0 ,0
Exp/Cntr=0.3,0.1

Type RM Length L Ch R = 1 ,6247    ,682,682,682
BEGIN DESCRIPTION:
SYCAMORE CREEK 10.0
END DESCRIPTION:
XS GIS Cut Line= 4
      2968493.78     10065479.71      2969410.42     10065587.34
      2969674.31     10065958.87      2970413.69     10065969.28
#Sta/Elev= 30
  3864.9 1072.38  3995.9 1062.49  4050.9 1053.85  4161.6 1044.79    4212 1030.12
  4286.4 1027.04  4391.3 1012.29  4457.7 1002.71  4534.2  966.92  4554.3  952.66
    4589  941.52  4634.8  935.56  4755.7   933.2  4927.9  932.49  4955.1  923.14
  4969.7  918.15  4996.2  916.85  4998.9  916.35  5002.2  916.85  5035.5  918.76
  5100.1  917.32  5150.5  923.85  5176.9  927.62  5192.3  929.01  5297.7  939.12
  5377.7  956.69  5443.7  962.99  5738.7  976.25  5867.8  985.25    5983  986.67
#Mann= 12 ,-1 , 0
  3864.9      .1       0  3995.9     .05       0  4391.3     .16       0
    4589     .05       0  4755.7      .1       0  4996.2     .07       0
  5002.2      .1       0  5035.5     .16       0  5176.9      .1       0
  5192.3     .16       0  5443.7      .1       0  5738.7     .16       0
Bank Sta=4955.1,5150.5
XS Rating Curve= 0 ,0
Exp/Cntr=0.3,0.1

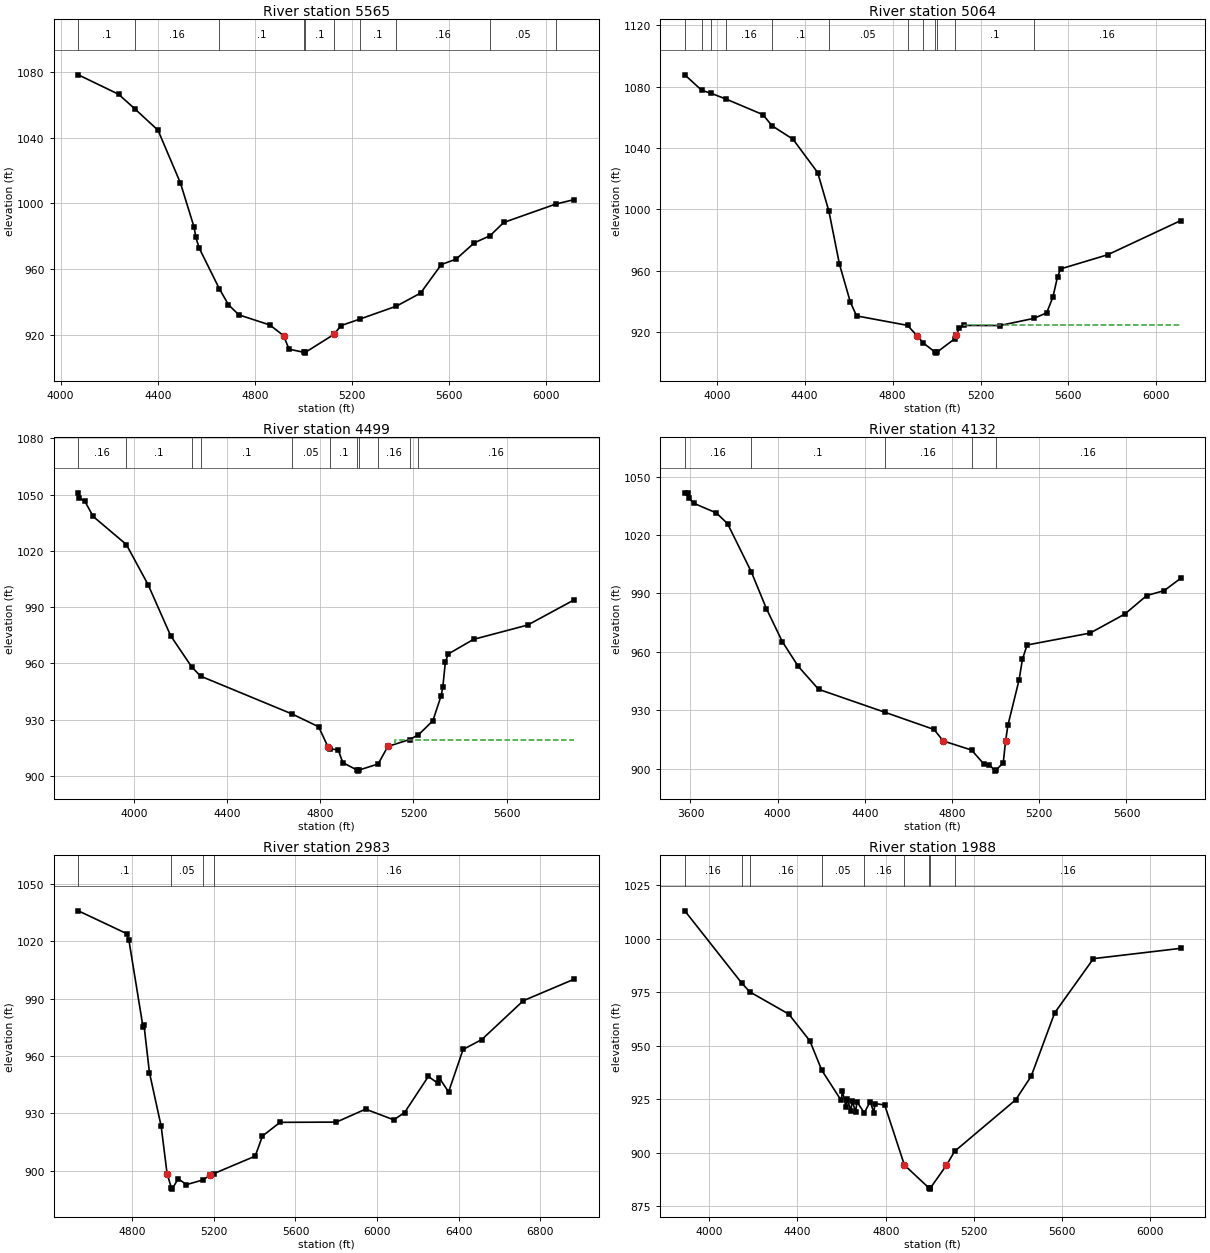
Type RM Length L Ch R = 1 ,5565    ,501,501,501
BEGIN DESCRIPTION:
SYCAMORE CREEK 9.0
END DESCRIPTION:
XS GIS Cut Line= 4
      2968393.05     10065535.25      2968900.01     10066021.37
      2969406.95     10066677.62      2969879.18     10066868.59
#Sta/Elev= 30
    4073 1078.11  4238.4 1066.32  4304.4 1057.58    4401 1044.43  4493.1 1012.43
  4549.7   985.4  4556.7  979.27  4570.8   972.7  4653.1  948.18  4690.9  938.39
  4733.4  932.25  4861.7  926.04  4917.8  919.56  4940.5  911.32  5001.8  909.45
  5004.5  908.95  5007.8  909.45  5125.2  920.33  5125.4  920.37  5154.2  925.67
  5230.5  929.57  5382.4  937.51    5482  945.46  5567.2  962.81  5627.8  966.06
  5703.3  976.03  5767.3  980.27  5824.2  988.37  6037.9  999.54    6114 1002.26
#Mann= 10 ,-1 , 0
    4073      .1       0  4304.4     .16       0  4653.1      .1       0
  5001.8     .07       0  5007.8      .1       0  5125.4     .05       0
  5230.5      .1       0  5382.4     .16       0  5767.3     .05       0
  6037.9     .16       0
Bank Sta=4917.8,5125.2
XS Rating Curve= 0 ,0
Exp/Cntr=0.3,0.1

Type RM Length L Ch R = 1 ,5064    ,565,565,565
BEGIN DESCRIPTION:
SYCAMORE CREEK 8.0
END DESCRIPTION:
XS GIS Cut Line= 4
      2968090.97     10065486.63      2968264.59     10066059.56
      2969011.12      10066917.2      2969493.63      10067111.6
#Sta/Elev= 30
  3854.6 1087.65  3931.7 1077.54  3975.2 1075.57  4043.4 1071.78    4210 1061.69
  4251.6 1054.43  4346.9 1045.66  4459.3 1023.91  4510.3  998.69  4558.2  964.26
  4607.6  939.59    4636  930.49  4867.9  924.32  4912.3   917.4  4940.2  912.77
  4994.8  906.72  4997.5  906.22  5000.8  906.72  5083.5  915.65  5089.9  917.98
  5104.1  922.74    5125  924.28  5288.3  924.21  5442.1  928.86    5501  932.46
  5529.5   942.8  5550.4  955.98  5564.6  961.13  5778.9  970.36  6110.5  992.59
#Mann= 12 ,-1 , 0
  3854.6      .1       0  3931.7     .16       0  3975.2      .1       0
  4043.4     .16       0  4251.6      .1       0  4510.3     .05       0
  4867.9      .1       0  4940.2     .16       0  4994.8     .07       0
  5000.8     .16       0  5083.5      .1       0  5442.1     .16       0
#XS Ineff= 2 , 0
                          5123.7          924.47
Permanent Ineff=
       T       T
Bank Sta=4912.3,5089.9
XS Rating Curve= 0 ,0
Exp/Cntr=0.3,0.1

Type RM Length L Ch R = 1 ,4499    ,367,367,367
BEGIN DESCRIPTION:
SYCAMORE CREEK 7.0
END DESCRIPTION:
XS GIS Cut Line= 2
      2967459.07     10066517.91      2969444.34     10067284.95
#Sta/Elev= 30
  3761.6 1050.93  3765.1 1048.18  3789.7 1046.38  3825.3 1038.33  3967.7 1023.35
  4061.1 1001.93  4157.7  974.76    4248   958.1  4286.5  953.14  4680.5  932.89
    4793  926.14    4833  915.48  4840.3  914.52  4877.5   913.7  4896.7  907.03
    4959  902.98  4961.8  902.48    4965  902.98  5048.4   906.3  5090.3  915.65
    5184  919.35  5221.5  921.86  5283.3  929.31  5319.2  942.81  5326.1  947.25
  5336.9  960.56  5349.2  964.96  5458.3  972.78  5690.6  980.41  5889.9  993.84
#Mann= 11 ,-1 , 0
  3761.6     .16       0  3967.7      .1       0    4248     .05       0
  4286.5      .1       0  4680.5     .05       0  4840.3      .1       0
    4959     .07       0    4965      .1       0  5048.4     .16       0
    5184      .1       0  5221.5     .16       0
#XS Ineff= 2 , 0
                         5122.16          918.82
Permanent Ineff=
       T       T
Bank Sta=4833,5090.3
XS Rating Curve= 0 ,0
Exp/Cntr=0.3,0.1

Type RM Length L Ch R = 1 ,4132    ,1149,1149,1149
BEGIN DESCRIPTION:
SYCAMORE CREEK 6.0
END DESCRIPTION:
XS GIS Cut Line= 3
       2967403.5     10066549.16      2968747.23     10067413.73
      2969423.88      10067417.2
#Sta/Elev= 30
    3574 1041.39  3588.8 1041.69  3594.7 1038.83  3615.9 1036.28  3718.9 1031.36
  3770.2 1025.83    3879 1001.11  3948.7  982.09  4021.3  965.23  4093.9  952.59
  4187.7  940.73  4491.3  928.95  4717.3  920.09  4759.5  914.18  4889.6  909.51
  4947.4  902.13  4971.2     902  4998.3  898.68  5001.6  899.18  5034.9  903.02
 5045.45  914.02    5056  922.17  5107.5  945.58  5122.7  956.06  5143.9  963.49
  5433.1  969.61  5593.1  979.43  5693.1  988.92  5773.1  991.42  5848.5  997.73
#Mann= 5 ,-1 , 0
    3574     .16       0    3879      .1       0  4491.3     .16       0
  4889.6     .05       0  5001.6     .16       0
Bank Sta=4759.5,5045.45
XS Rating Curve= 0 ,0
Exp/Cntr=0.3,0.1

Type RM Length L Ch R = 1 ,2983    ,995,995,995
BEGIN DESCRIPTION:
SYCAMORE CREEK 5.0
END DESCRIPTION:
XS GIS Cut Line= 4
       2967122.2     10067462.34      2967698.62     10067528.31
       2968188.2     10067708.87       2969493.6     10067469.32
#Sta/Elev= 30
  4536.2 1035.96    4774 1023.97  4784.1 1020.55  4852.9  975.29  4857.9  976.05
  4884.7  951.23  4942.1  923.14    4971  898.34  4992.4  890.76  4995.2  890.26
  5025.6  895.69  5065.9  892.61  5144.7  895.01  5180.4   897.4    5200  898.38
  5402.6  907.53  5438.4  918.07  5524.4  925.22  5800.6  925.35  5943.5  932.14
  6081.5  926.55  6134.6  930.34    6251  949.26    6299  945.57  6304.1  948.53
  6350.2  941.16  6421.3  963.38  6512.8  968.57  6716.2   988.9  6965.4 1000.17
#Mann= 4 ,-1 , 0
  4536.2      .1       0  4992.4     .05       0  5144.7      .1       0
    5200     .16       0
Bank Sta=4971,5180.4
XS Rating Curve= 0 ,0
Exp/Cntr=0.3,0.1

Type RM Length L Ch R = 1 ,1988    ,452,452,452
BEGIN DESCRIPTION:
SYCAMORE CREEK 4.0
END DESCRIPTION:
XS GIS Cut Line= 4
      2967233.37     10067830.41      2968045.84      10068267.9
       2968500.7     10068076.93      2969323.59     10068194.98
#Sta/Elev= 30
  3889.3 1013.08  4147.6  979.28  4183.9   975.2  4360.7   964.8  4456.3  952.29
  4510.1  938.58  4598.2  924.46  4603.9  928.89  4620.1  921.26  4625.8  925.13
    4642  919.58  4647.7  924.19  4663.9  919.19  4669.6  923.81  4702.9  918.65
  4729.7  923.91  4745.9  918.76  4751.6  922.99  4795.4  922.35  4884.6  894.27
  4996.3  883.51    4999  883.01  5002.3  883.51  5075.2  894.16  5112.4  900.69
  5388.8  924.73  5459.3  935.77  5565.8  965.38  5741.6  990.74  6136.7  995.54
#Mann= 9 ,-1 , 0
  3889.3     .16       0  4147.6      .1       0  4183.9     .16       0
  4510.1     .05       0  4702.9     .16       0  4884.6     .05       0
  4996.3    .035       0  5002.3     .05       0  5112.4     .16       0
Bank Sta=4884.6,5075.2
XS Rating Curve= 0 ,0
Exp/Cntr=0.3,0.1

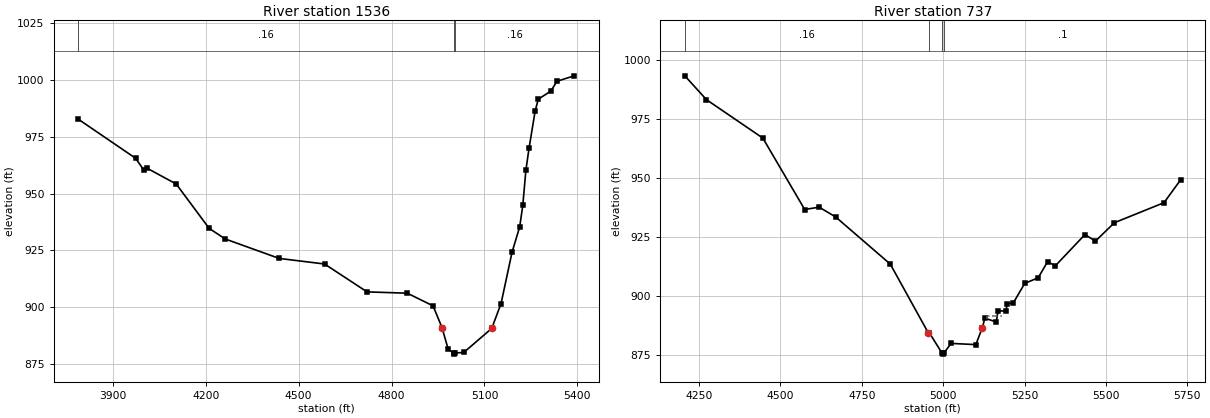
Type RM Length L Ch R = 1 ,1536    ,799,799,799
BEGIN DESCRIPTION:
SYCAMORE CREEK 3.0
END DESCRIPTION:
XS GIS Cut Line= 4
       2967389.6     10067979.71       2968188.2     10068472.76
       2968375.7     10068549.15      2968833.78     10068583.85
#Sta/Elev= 30
  3789.1   982.7  3973.8  965.55  4000.9  960.28  4010.4   961.2    4105  954.23
  4211.4  934.71  4263.4  930.05  4437.2  921.52  4583.9  919.06    4721  906.81
  4850.8  906.23    4934  900.68    4963   891.1    4983  881.55  5000.1  879.95
  5002.8  879.45  5006.1  879.95  5033.2  880.19  5123.4  890.74  5153.5  901.67
    5189  924.23  5213.7  935.38  5223.7  944.83  5233.7  960.29  5243.8  969.89
  5263.8   986.5  5273.9  991.53    5314  995.02    5334  999.38  5389.5 1001.77
#Mann= 3 ,-1 , 0
  3789.1     .16       0  5000.1     .07       0  5006.1     .16       0
Bank Sta=4963,5123.4
XS Rating Curve= 0 ,0
Exp/Cntr=0.3,0.1

Type RM Length L Ch R = 1 ,737     ,499,499,499
BEGIN DESCRIPTION:
SYCAMORE CREEK 2.0
END DESCRIPTION:
XS GIS Cut Line= 4
       2967285.4     10067983.16      2967722.92     10068285.26
      2967778.48     10068674.15      2968328.74     10068909.48
#Sta/Elev= 30
  4206.4   993.4    4273  983.27  4446.1  966.96  4574.7  936.63  4619.1  937.63
  4669.8  933.46  4837.6  913.44  4953.9  884.35    4958  884.17  4996.2  875.71
  4998.9  875.21  5002.2  875.71  5024.6  879.76  5100.4  879.25  5120.4   886.5
  5128.2  890.49  5163.1  888.85  5168.5  893.54  5192.1  893.54  5197.5  896.65
  5215.7  897.01  5250.5  905.24  5291.9  907.64  5320.9   914.5  5344.5   912.7
  5435.4  925.97  5467.9  923.23    5526  931.02  5678.4  939.53  5729.4  949.22
#Mann= 4 ,-1 , 0
  4206.4     .16       0    4958      .1       0  4996.2     .07       0
  5002.2      .1       0
#XS Ineff= 1 ,-1
 5133.64 5180.91  891.19
Permanent Ineff=
       T
Bank Sta=4953.9,5120.4
XS Rating Curve= 0 ,0
Exp/Cntr=0.3,0.1