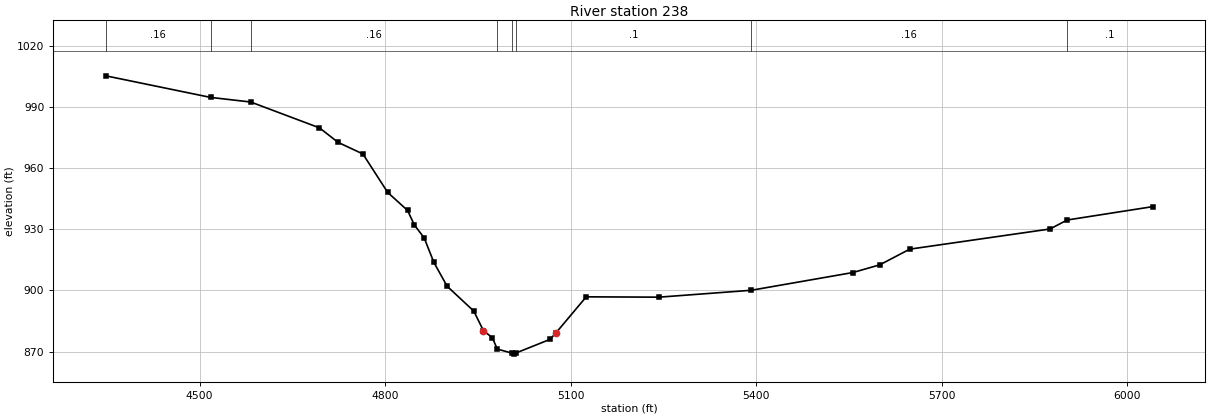
HEC-RAS study SYCAMORE CREEK.prj: SYCAMORE CREEK Base Level Engineering

--- SYCAMORE CREEK.g01 (geometry) --- (continued)

Type RM Length L Ch R = 1 ,238     ,0,0,0
BEGIN DESCRIPTION:
SYCAMORE CREEK 1.0
END DESCRIPTION:
XS GIS Cut Line= 4
        2967150.     10067969.24       2967188.2     10068451.93
      2967358.34     10068743.59      2968209.01     10068934.56
#Sta/Elev= 30
  4348.2 1005.28  4517.6   994.7  4582.6  992.43  4693.8  979.75  4723.9  972.63
    4764  966.95  4804.1  948.09  4836.3  939.22  4847.3  932.07  4863.1  925.78
  4878.8  913.75  4900.3  902.03  4943.3  889.87    4959  880.23  4973.4  876.81
  4981.3  871.21  5005.1  869.24  5007.9  868.74  5011.1  869.24  5066.5  875.96
  5076.4  879.22  5125.2  896.85  5243.1  896.69  5392.2  900.07  5556.6  908.78
    5600  912.56  5648.4  920.24  5875.3  930.14    5903  934.54  6041.9  941.13
#Mann= 8 ,-1 , 0
  4348.2     .16       0  4517.6      .1       0  4582.6     .16       0
  4981.3      .1       0  5005.1     .07       0  5011.1      .1       0
  5392.2     .16       0    5903      .1       0
Bank Sta=4959,5076.4
XS Rating Curve= 0 ,0
Exp/Cntr=0.3,0.1

Chan Stop Cuts=-1
Use User Specified Reach Order=0
Composite Channel Slope=5