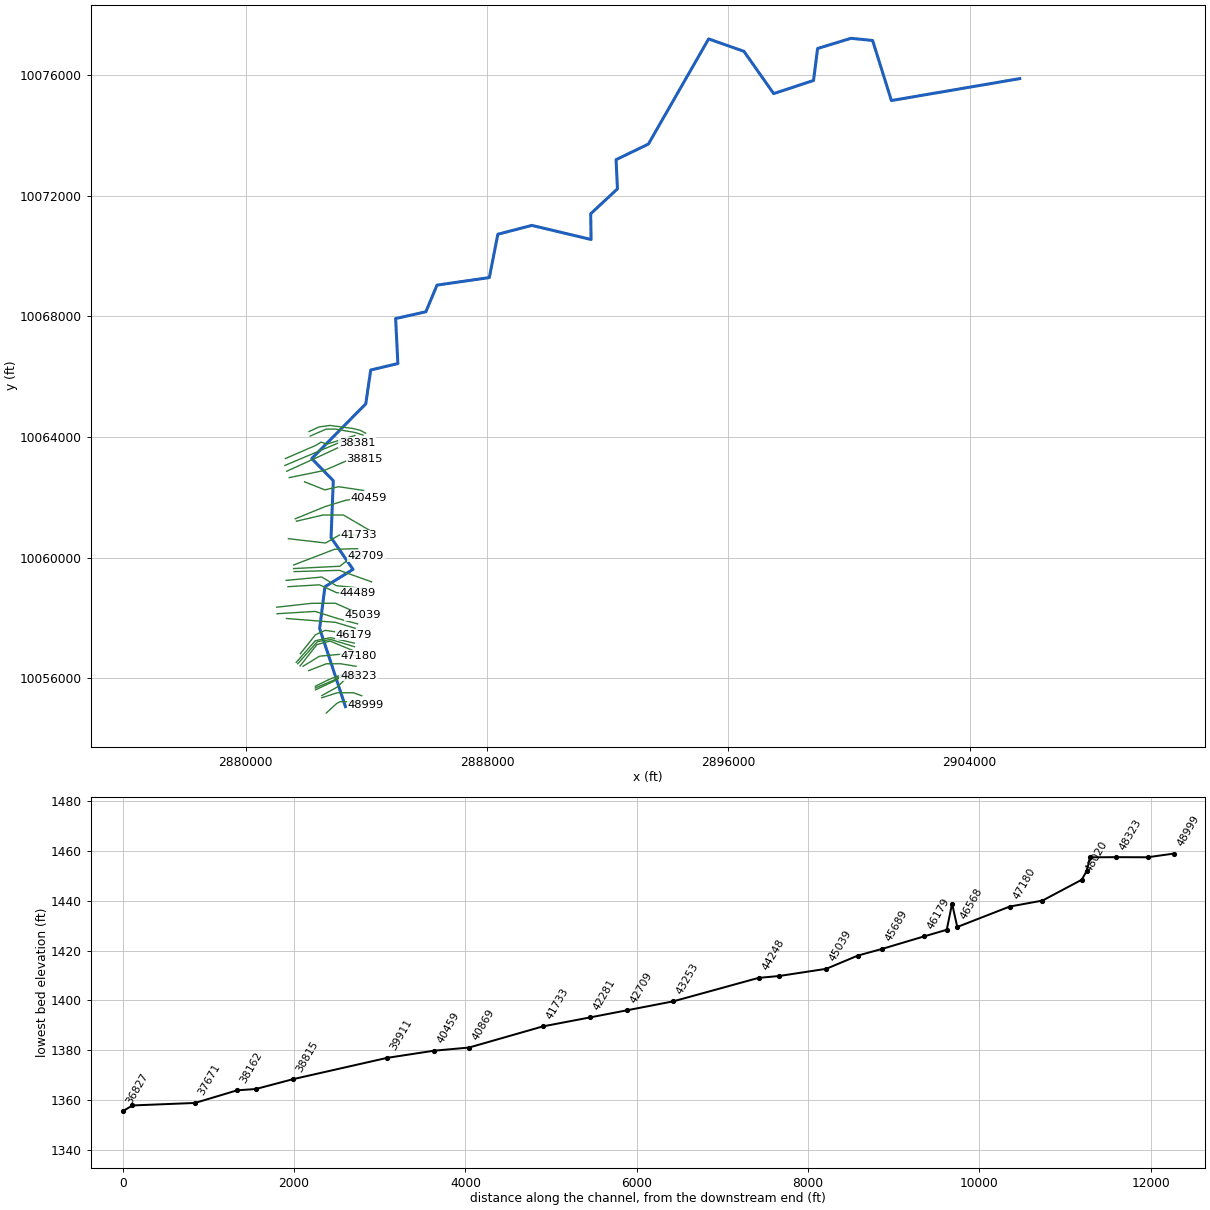
--- TOWHEAD CREEK.prj (project) ---

Proj Title=TOWHEAD CREEK Base Level Engineering
Current Plan=p01
Default Exp/Contr=0.3,0.1
English Units
Geom File=g01
Flow File=f01
Plan File=p01
Y Axis Title=Elevation
X Axis Title(PF)=Main Channel Distance
X Axis Title(XS)=Station
BEGIN DESCRIPTION:
TOWHEAD CREEK
END DESCRIPTION:
DSS Export Rating Curves= 0
DSS Export Rating Curve Sorted= 0
DSS Export Volume Flow Curves= 0
DXF OffsetX= 0
DXF OffsetY= 0
DXF ScaleX= 1
DXF ScaleY= 10

--- TOWHEAD CREEK.p01 (plan) ---

Plan Title=Multiple Run
Short Identifier=Multiple
Geom File=g01
Flow File=f01
Subcritical Flow
K Sum by GR= 0
Std Step Tol= 0.01
Critical Tol= 0.01
Num of Std Step Trials= 20
Max Error Tol= 0.3
Flow Tol Ratio= 0.001
Split Flow NTrial= 30
Split Flow Tol= 0.02
Split Flow Ratio= 0.02
Log Output Level= 0
Friction Slope Method= 1
Unsteady Friction Slope Method= 2
Unsteady Bridges Friction Slope Method= 1
Parabolic Critical Depth
Global Vel Dist=  1 , 1 , 1
Global Log Level= 0
CheckData=True
Encroach Param= -1, 0, 0, 0
BEGIN DESCRIPTION:
Multiple Run
END DESCRIPTION:

--- TOWHEAD CREEK.f01 (steady flow) ---

Flow Title=Multiple
Number of Profiles=7
Profile Names=10-year,25-year,50-year,1pct_min,100-year,1pct_plu,500-year
River Rch & RM= TOWHEAD CREEK,Reach-1,48999
    1205    1785    2299    2169    2934    3968    4792
River Rch & RM= TOWHEAD CREEK,Reach-1,45689
    2225    3386    4440    4252    5751    7777    9688
River Rch & RM= TOWHEAD CREEK,Reach-1,40869
    2405    3666    4813    4612    6238    8436   10524
River Rch & RM= TOWHEAD CREEK,Reach-1,38162
    2588    3946    5180    4962    6710    9075   11311
River Rch & RM= TOWHEAD CREEK,Reach-1,31956
    2741    4179    5485    5251    7102    9604   11959
River Rch & RM= TOWHEAD CREEK,Reach-1,26018
    3111    4769    6283    6035    8162   11038   13835
River Rch & RM= TOWHEAD CREEK,Reach-1,24514
    3398    5225    6899    6638    8977   12141   15274
River Rch & RM= TOWHEAD CREEK,Reach-1,21752
    3430    5262    6936    6662    9009   12184   15271
River Rch & RM= TOWHEAD CREEK,Reach-1,13874
    3938    6063    8011    7708   10424   14097   17734
River Rch & RM= TOWHEAD CREEK,Reach-1,3970
    6425   10060   13447   13077   17685   23917   30721
Boundary for River Rch & Prof#=TOWHEAD CREEK,Reach-1,1
Up Type=0
Dn Type=3
Dn Slope=0.005
Boundary for River Rch & Prof#=TOWHEAD CREEK,Reach-1,2
Up Type=0
Dn Type=3
Dn Slope=0.005
Boundary for River Rch & Prof#=TOWHEAD CREEK,Reach-1,3
Up Type=0
Dn Type=3
Dn Slope=0.005
Boundary for River Rch & Prof#=TOWHEAD CREEK,Reach-1,4
Up Type=0
Dn Type=3
Dn Slope=0.005
Boundary for River Rch & Prof#=TOWHEAD CREEK,Reach-1,5
Up Type=0
Dn Type=3
Dn Slope=0.005
Boundary for River Rch & Prof#=TOWHEAD CREEK,Reach-1,6
Up Type=0
Dn Type=3
Dn Slope=0.005
Boundary for River Rch & Prof#=TOWHEAD CREEK,Reach-1,7
Up Type=0
Dn Type=3
Dn Slope=0.005

--- TOWHEAD CREEK.g01 (geometry) ---

Geom Title=Existing Conditions
Program Version=4.10

River Reach=TOWHEAD CREEK   ,Reach-1
Reach XY= 30
      2883308.16     10055064.97       2882452.3     10057655.98
      2882628.62     10059038.67      2883558.53     10059613.62
      2882830.79     10060668.56      2882905.27      10062552.3
      2882190.51     10063284.92      2883981.47     10065099.31
      2884146.24     10066221.46        2885046.     10066434.58
      2884971.76     10067925.94       2885975.1     10068151.74
      2886343.32     10069034.14      2888078.84     10069284.83
      2888360.49     10070720.31      2889488.23     10071013.57
      2891451.82       10070547.      2891438.81     10071398.68
      2892325.79     10072224.77      2892280.53     10073192.87
      2893351.24     10073707.33      2895348.47     10077193.73
      2896518.99     10076782.69      2897505.28     10075381.39
      2898826.06     10075816.43      2898962.26     10076876.75
      2900068.48     10077213.84      2900784.99     10077142.51
      2901408.06      10075151.4      2905664.02     10075878.18

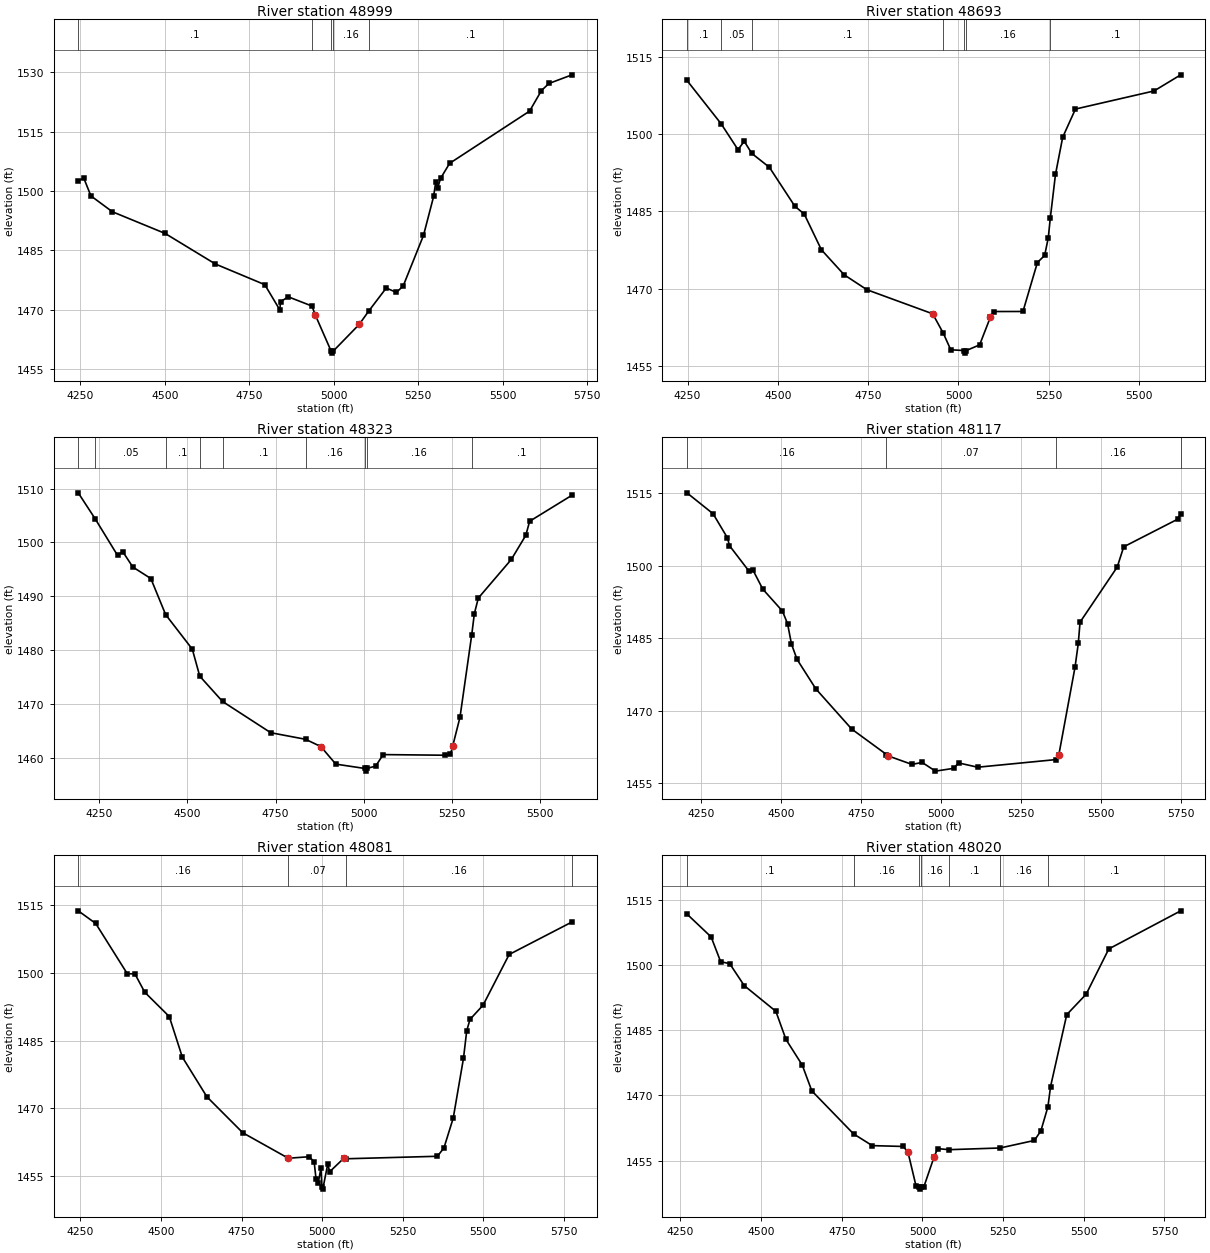
Type RM Length L Ch R = 1 ,48999   ,306,306,306
BEGIN DESCRIPTION:
TOWHEAD CREEK 92.0
END DESCRIPTION:
XS GIS Cut Line= 5
      2882674.94     10054854.25      2883013.98     10055167.04
      2883137.29     10055230.07      2883596.29     10055219.11
      2883984.48     10055116.59
#Sta/Elev= 30
  4244.1 1502.62  4260.6 1503.25  4281.6 1498.76  4345.1 1494.75    4501 1489.27
  4649.6 1481.54  4795.8 1476.31  4840.3 1469.93  4842.4 1471.99  4865.1 1473.24
  4935.3  1470.9  4945.1 1468.66  4992.1 1459.49  4994.8 1458.99  4998.1 1459.49
  5075.1 1466.25  5102.8 1469.58  5155.1 1475.47  5185.1 1474.34  5205.2 1475.99
  5265.2 1488.77  5295.2 1498.63  5301.6 1502.39  5307.5 1500.88  5315.6 1503.18
  5342.5    1507    5579 1520.21  5614.1 1525.42  5636.2  1527.2  5704.5 1529.39
#Mann= 5 ,-1 , 0
  4244.1      .1       0  4935.3     .16       0  4992.1     .07       0
  4998.1     .16       0  5102.8      .1       0
Bank Sta=4945.1,5075.1
XS Rating Curve= 0 ,0
Exp/Cntr=0.3,0.1

Type RM Length L Ch R = 1 ,48693   ,370,370,370
BEGIN DESCRIPTION:
Mapping XS b455c97e
END DESCRIPTION:
XS GIS Cut Line= 4
      2882523.76       10055360.       2883040.3     10055524.95
      2883574.15     10055524.95      2883847.61     10055425.11
#Sta/Elev= 30
  4248.1 1510.42  4342.9 1501.99  4389.5 1496.99  4406.8  1498.6  4427.9 1496.24
  4476.4 1493.56    4547    1486  4572.9 1484.49  4620.4 1477.56  4683.4 1472.71
  4746.4 1469.81  4928.5 1465.14  4958.1 1461.35  4978.5 1458.16  5015.5 1458.01
  5018.2 1457.51  5021.5 1458.01  5058.5 1459.11  5088.5 1464.52  5098.5 1465.58
  5178.5 1465.59  5218.5 1475.09  5238.5 1476.46  5248.5 1479.85  5254.1 1483.65
  5268.5 1492.17  5288.5 1499.39  5323.8 1504.86  5541.4 1508.37  5615.3  1511.5
#Mann= 7 ,-1 , 0
  4248.1      .1       0  4342.9     .05       0  4427.9      .1       0
  4958.1     .16       0  5015.5     .07       0  5021.5     .16       0
  5254.1      .1       0
Bank Sta=4928.5,5088.5
XS Rating Curve= 0 ,0
Exp/Cntr=0.3,0.1

Type RM Length L Ch R = 1 ,48323   ,303,303,303
BEGIN DESCRIPTION:
Mapping XS fd0030b0
END DESCRIPTION:
XS GIS Cut Line= 4
      2882528.12     10055433.78       2883040.3     10055715.92
      2883292.03     10055967.65      2883734.06     10056093.33
#Sta/Elev= 30
  4190.3 1509.21  4237.8 1504.44  4301.7 1497.61  4316.3 1498.31  4345.2 1495.43
  4396.2  1493.3  4438.2  1486.6  4513.8 1480.19  4534.9 1475.18  4599.5 1470.48
  4736.2 1464.68  4834.9 1463.46  4878.3 1462.11  4920.7 1458.85  5002.6 1458.05
  5005.3 1457.55  5008.6 1458.05  5033.8 1458.48    5055 1460.62  5231.3  1460.5
  5245.8 1460.67  5252.1 1462.17  5272.9 1467.56  5306.2 1482.87  5313.6 1486.78
  5324.9 1489.68  5418.4 1496.84  5459.5 1501.32  5470.4 1503.93  5590.6 1508.77
#Mann= 9 ,-1 , 0
  4190.3      .1       0  4237.8     .05       0  4438.2      .1       0
  4534.9     .16       0  4599.5      .1       0  4834.9     .16       0
  5002.6     .07       0  5008.6     .16       0  5306.2      .1       0
Bank Sta=4878.3,5252.1
XS Rating Curve= 0 ,0
Exp/Cntr=0.3,0.1

Type RM Length L Ch R = 1 ,48117   ,36,36,36
BEGIN DESCRIPTION:
Mapping XS 38ecc9e5
END DESCRIPTION:
XS GIS Cut Line= 4
      2882313.83     10055622.09      2882966.59     10055927.64
      2883086.38     10056009.23      2883754.15     10056120.24
#Sta/Elev= 30
  4205.7 1515.08  4287.4 1510.75  4332.3 1505.76  4338.6 1504.15  4398.5 1498.97
  4412.6 1499.02  4442.7 1495.15  4503.9 1490.63    4520 1488.02  4532.3 1483.79
  4549.6 1480.63  4608.3 1474.53  4720.5  1466.2  4829.1 1460.94  4834.7 1460.64
  4908.7 1458.89  4940.4  1459.3  4982.2  1457.5  5039.3 1458.08  5054.2  1459.2
    5114 1458.31  5357.3 1459.88  5367.5 1460.86  5418.1 1479.01  5428.3 1483.94
  5433.8 1488.32  5549.9 1499.72  5570.2 1503.91  5738.3 1509.61  5748.3 1510.79
#Mann= 4 ,-1 , 0
  4205.7     .16       0  4829.1     .07       0  5357.3     .16       0
  5748.3      .1       0
Bank Sta=4834.7,5367.5
XS Rating Curve= 0 ,0
Exp/Cntr=0.3,0.1

Type RM Length L Ch R = 1 ,48081   ,61,61,61
BEGIN DESCRIPTION:
Mapping XS 6a4cb265
END DESCRIPTION:
XS GIS Cut Line= 4
      2882308.63     10055681.12      2882931.87     10055946.73
      2883079.44     10056040.48       2883751.3     10056144.65
#Sta/Elev= 30
  4243.1 1513.68  4297.3 1510.89  4395.3 1499.78  4418.9 1499.75  4449.5 1495.69
  4525.6 1490.31  4566.1 1481.35  4642.4 1472.57  4753.8 1464.62  4894.9    1459
  4959.8 1459.33  4975.1 1458.21    4981 1454.43  4987.6 1453.48  4996.2 1456.79
  4999.2 1452.67  5001.9 1452.17  5017.4 1457.73  5023.3 1456.01  5069.1 1459.12
    5075 1458.88  5357.5 1459.43  5377.8 1461.27  5406.7 1467.88  5438.5 1481.09
  5448.6 1487.18  5458.7 1489.69  5499.2 1492.82  5580.2 1504.03  5775.3 1511.22
#Mann= 4 ,-1 , 0
  4243.1     .16       0  4894.9     .07       0    5075     .16       0
  5775.3      .1       0
Bank Sta=4894.9,5069.1
XS Rating Curve= 0 ,0
Exp/Cntr=0.3,0.1

Type RM Length L Ch R = 1 ,48020   ,458,458,458
BEGIN DESCRIPTION:
Mapping XS 44333cf5
END DESCRIPTION:
XS GIS Cut Line= 4
      2882311.11     10055741.95      2882788.56     10055976.33
      2883166.17     10056115.22      2883760.76     10056158.62
#Sta/Elev= 30
    4270 1511.72    4345 1506.45  4374.5 1500.76  4402.6  1500.3  4447.6 1495.26
  4545.6 1489.35  4576.9 1482.89  4627.4 1476.99    4657 1471.06  4786.4 1461.17
  4844.4 1458.47  4940.3 1458.28    4955 1456.99  4980.1 1449.18  4990.6 1448.97
  4993.3 1448.47  4996.6 1448.97  5004.2 1448.98  5035.7  1455.8  5046.8 1457.78
  5083.1 1457.54  5240.8 1457.93  5346.9 1459.66    5367 1461.87  5388.8 1467.41
    5397 1472.06  5447.2 1488.59  5507.3 1493.28  5577.5 1503.69  5800.4 1512.45
#Mann= 7 ,-1 , 0
    4270      .1       0  4786.4     .16       0  4990.6     .07       0
  4996.6     .16       0  5083.1      .1       0  5240.8     .16       0
  5388.8      .1       0
Bank Sta=4955,5035.7
XS Rating Curve= 0 ,0
Exp/Cntr=0.3,0.1

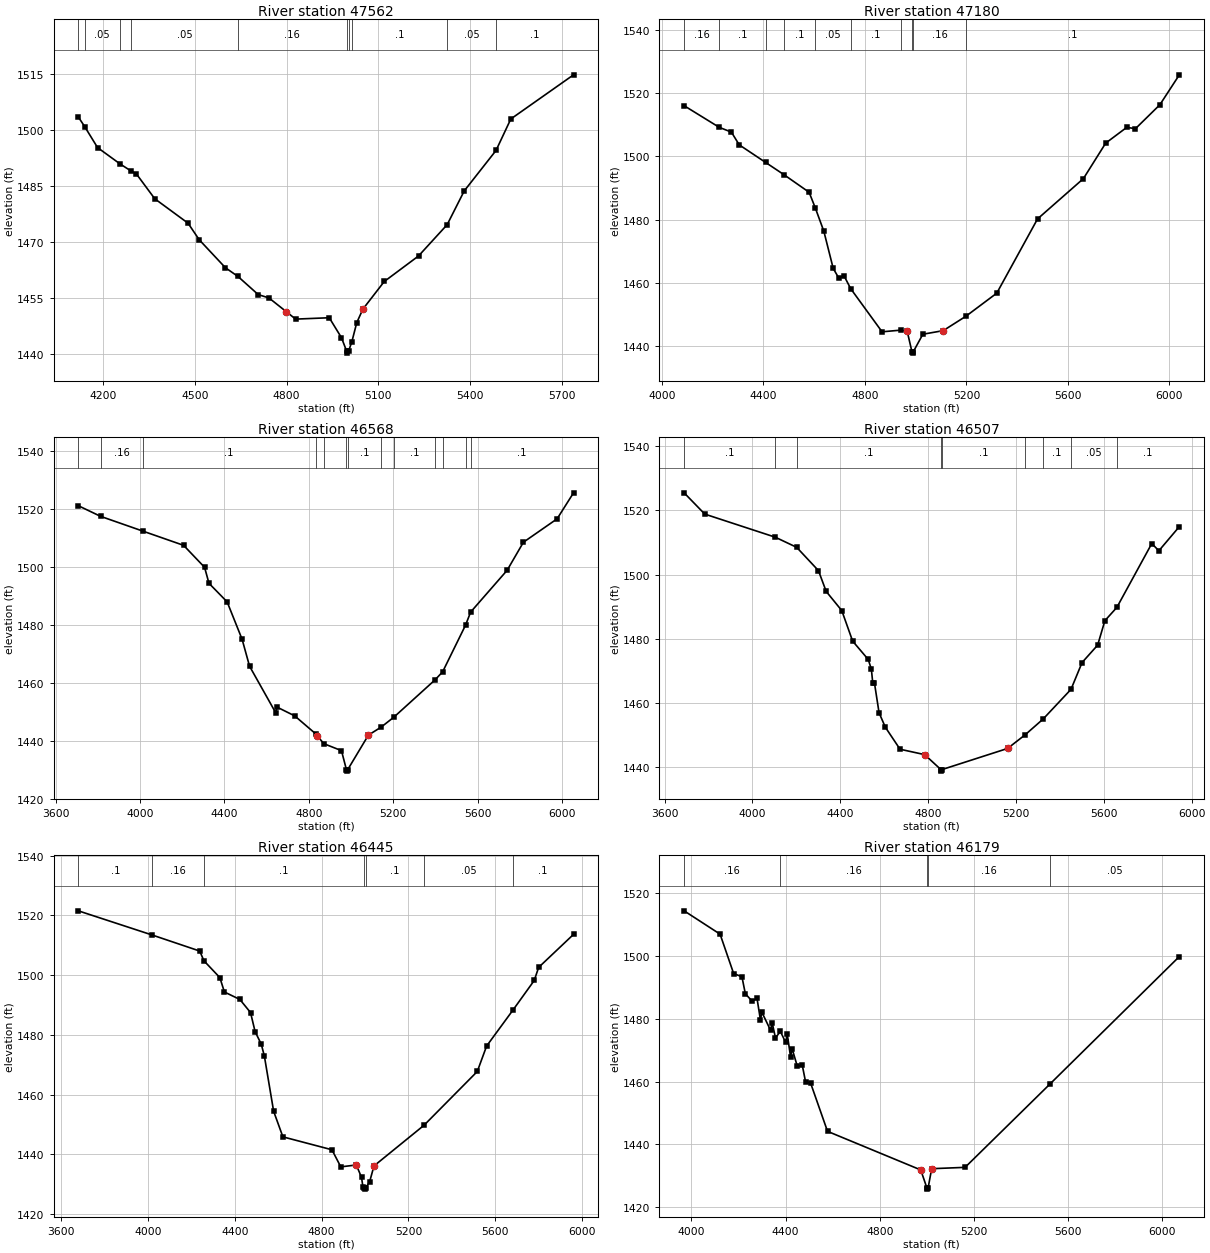
Type RM Length L Ch R = 1 ,47562   ,382,382,382
BEGIN DESCRIPTION:
TOWHEAD CREEK 91.0
END DESCRIPTION:
XS GIS Cut Line= 4
      2882089.76     10056258.45      2882671.37     10056484.15
      2883157.48     10056484.15        2883661.     10056401.67
#Sta/Elev= 30
  4118.5 1503.43  4139.3 1500.86  4181.5 1495.22  4254.6 1490.87  4291.2 1488.93
  4308.8 1488.13  4368.6  1481.5  4477.5 1474.95    4514 1470.51  4599.8    1463
  4640.7 1460.67  4707.1  1455.8  4742.4 1454.89  4799.5 1451.18  4829.5 1449.22
  4939.5 1449.59  4979.5 1444.24  4996.5  1440.6  4999.2  1440.1  5002.5  1440.6
  5013.4 1443.14  5029.5 1448.27  5049.5 1451.89  5119.5 1459.31  5231.5 1466.15
  5325.3 1474.55  5381.1  1483.6  5485.2 1494.46  5533.5 1502.89  5738.7 1514.73
#Mann= 10 ,-1 , 0
  4118.5      .1       0  4139.3     .05       0  4254.6      .1       0
  4291.2     .05       0  4640.7     .16       0  4996.5     .07       0
  5002.5     .16       0  5013.4      .1       0  5325.3     .05       0
  5485.2      .1       0
Bank Sta=4799.5,5049.5
XS Rating Curve= 0 ,0
Exp/Cntr=0.3,0.1

Type RM Length L Ch R = 1 ,47180   ,612,612,612
BEGIN DESCRIPTION:
TOWHEAD CREEK 90.0
END DESCRIPTION:
XS GIS Cut Line= 4
      2881902.45     10056403.11      2882451.07     10056736.45
      2883124.68     10056798.95        2883755.     10056743.54
#Sta/Elev= 30
  4087.9 1516.05  4226.2  1509.2  4274.2 1507.68  4305.1 1503.65  4408.7  1498.1
  4481.4  1494.2  4580.4 1488.64  4605.1 1483.61  4638.5 1476.28  4675.3 1464.54
  4696.6 1461.57    4718 1462.18  4744.3 1458.11  4867.8 1444.46  4941.7 1444.99
  4967.1 1444.56  4985.3 1438.21  4988.1 1437.71  4991.3 1438.21  5028.5 1443.69
  5108.9 1444.83  5198.6 1449.41  5319.8  1456.7  5480.4  1480.2  5661.1 1492.96
  5748.9  1504.2  5831.8 1509.18  5866.3 1508.78  5962.3 1516.34  6039.1 1525.82
#Mann= 10 ,-1 , 0
  4087.9     .16       0  4226.2      .1       0  4408.7     .16       0
  4481.4      .1       0  4605.1     .05       0  4744.3      .1       0
  4941.7     .16       0  4985.3     .07       0  4991.3     .16       0
  5198.6      .1       0
Bank Sta=4967.1,5108.9
XS Rating Curve= 0 ,0
Exp/Cntr=0.3,0.1

Type RM Length L Ch R = 1 ,46568   ,61,61,61
BEGIN DESCRIPTION:
TOWHEAD CREEK 89.0
END DESCRIPTION:
XS GIS Cut Line= 4
      2881801.53     10056410.29      2882364.03      10057122.1
      2882798.06     10057236.68      2883714.11     10056858.46
#Sta/Elev= 30
  3707.4 1521.24  3812.7 1517.57  4012.8 1512.47  4206.5 1507.54  4305.9 1499.94
  4326.7 1494.42  4412.8    1488  4483.8 1475.06    4519 1465.77  4642.9 1449.69
  4650.3 1451.59    4733  1448.6  4831.8 1442.43  4839.1 1441.76  4871.3 1438.98
  4954.7 1436.58  4978.2    1430    4981  1429.5  4984.2    1430  5082.3 1441.94
  5143.8 1444.77  5203.4 1448.17  5398.9 1461.09  5434.3 1463.84    5543 1479.99
  5566.8 1484.46  5739.8 1498.91    5817 1508.61  5976.7  1516.7  6054.6 1525.69
#Mann= 13 ,-1 , 0
  3707.4      .1       0  3812.7     .16       0  4012.8      .1       0
  4831.8     .05       0  4871.3      .1       0  4978.2     .07       0
  4984.2      .1       0  5143.8     .05       0  5203.4      .1       0
  5398.9     .05       0  5434.3      .1       0    5543     .05       0
  5566.8      .1       0
Bank Sta=4839.1,5082.3
XS Rating Curve= 0 ,0
Exp/Cntr=0.3,0.1

Type RM Length L Ch R = 1 ,46507   ,62,62,62
BEGIN DESCRIPTION:
TOWHEAD CREEK 88.0
END DESCRIPTION:
XS GIS Cut Line= 4
      2881724.93     10056483.95      2882378.11     10057219.59
      2882822.99     10057289.04      2883608.58     10057050.32
#Sta/Elev= 30
    3689 1525.45  3783.1 1518.83  4103.6 1511.66  4201.5  1508.5  4300.7 1501.25
  4335.9 1494.78    4407 1488.81  4456.3 1479.33  4527.4 1473.61  4541.6  1470.6
  4548.3 1466.15  4555.8 1466.27  4576.7 1457.03  4605.2 1452.54  4672.2 1445.68
  4784.5    1444    4858 1439.37  4860.8 1438.87    4864 1439.37  5161.9 1445.92
  5241.8 1450.16  5323.6 1455.06  5450.8 1464.32  5501.1 1472.65  5572.1 1478.07
    5605 1485.67  5659.7 1489.82  5818.6 1509.68  5850.8 1507.42  5944.1 1514.94
#Mann= 9 ,-1 , 0
    3689      .1       0  4103.6     .16       0  4201.5      .1       0
    4858     .07       0    4864      .1       0  5241.8     .05       0
  5323.6      .1       0  5450.8     .05       0  5659.7      .1       0
Bank Sta=4784.5,5161.9
XS Rating Curve= 0 ,0
Exp/Cntr=0.3,0.1

Type RM Length L Ch R = 1 ,46445   ,266,266,266
BEGIN DESCRIPTION:
TOWHEAD CREEK 87.0
END DESCRIPTION:
XS GIS Cut Line= 4
      2881678.31     10056534.47      2882311.45     10057251.87
      2882812.17     10057350.57      2883605.06     10057170.37
#Sta/Elev= 30
  3679.9 1521.49  4020.5 1513.39  4239.1 1508.03  4258.1  1504.8  4331.7 1499.15
  4352.6 1494.33  4423.7 1491.85    4473 1487.45  4493.9 1481.09  4522.4 1476.86
  4536.6 1472.92  4579.3 1454.43  4621.9 1445.87  4847.7 1441.55  4888.5 1435.83
  4959.9 1436.46  4983.9 1432.34  4990.4 1429.17  4997.6 1428.88  5000.4 1428.38
  5003.6 1428.88    5021 1430.76  5041.4 1436.14  5271.7 1449.74    5517 1467.74
  5560.1 1476.27  5680.4  1488.2  5779.1 1498.18  5799.6 1502.57  5960.2 1513.61
#Mann= 7 ,-1 , 0
  3679.9      .1       0  4020.5     .16       0  4258.1      .1       0
  4997.6     .07       0  5003.6      .1       0  5271.7     .05       0
  5680.4      .1       0
Bank Sta=4959.9,5041.4
XS Rating Curve= 0 ,0
Exp/Cntr=0.3,0.1

Type RM Length L Ch R = 1 ,46179   ,490,490,490
BEGIN DESCRIPTION:
TOWHEAD CREEK 86.0
END DESCRIPTION:
XS GIS Cut Line= 4
      2881810.72     10056816.14      2882316.26     10057449.27
      2882641.25     10057593.71      2883568.08     10057451.68
#Sta/Elev= 30
    3969 1514.42  4121.8 1506.98  4179.4 1494.42  4214.6 1493.41    4229    1488
  4257.9 1485.61  4278.7  1486.5  4293.1 1479.68  4299.5 1482.06  4336.3 1476.33
  4342.7 1478.81  4357.1 1473.92  4377.9 1475.98  4400.4 1472.47  4406.8 1475.26
  4421.2 1467.87  4427.6 1470.51    4450 1464.81  4470.8 1465.23  4485.2 1459.79
    4506 1459.57  4578.1 1444.13    4974 1431.83  4999.7 1426.21  5002.5 1425.71
  5005.7 1426.21  5020.5 1432.22  5162.4 1432.65  5521.3 1459.09  6072.5 1499.85
#Mann= 5 ,-1 , 0
    3969     .16       0  4377.9     .16       0  4999.7     .07       0
  5005.7     .16       0  5521.3     .05       0
Bank Sta=4974,5020.5
XS Rating Curve= 0 ,0
Exp/Cntr=0.3,0.1

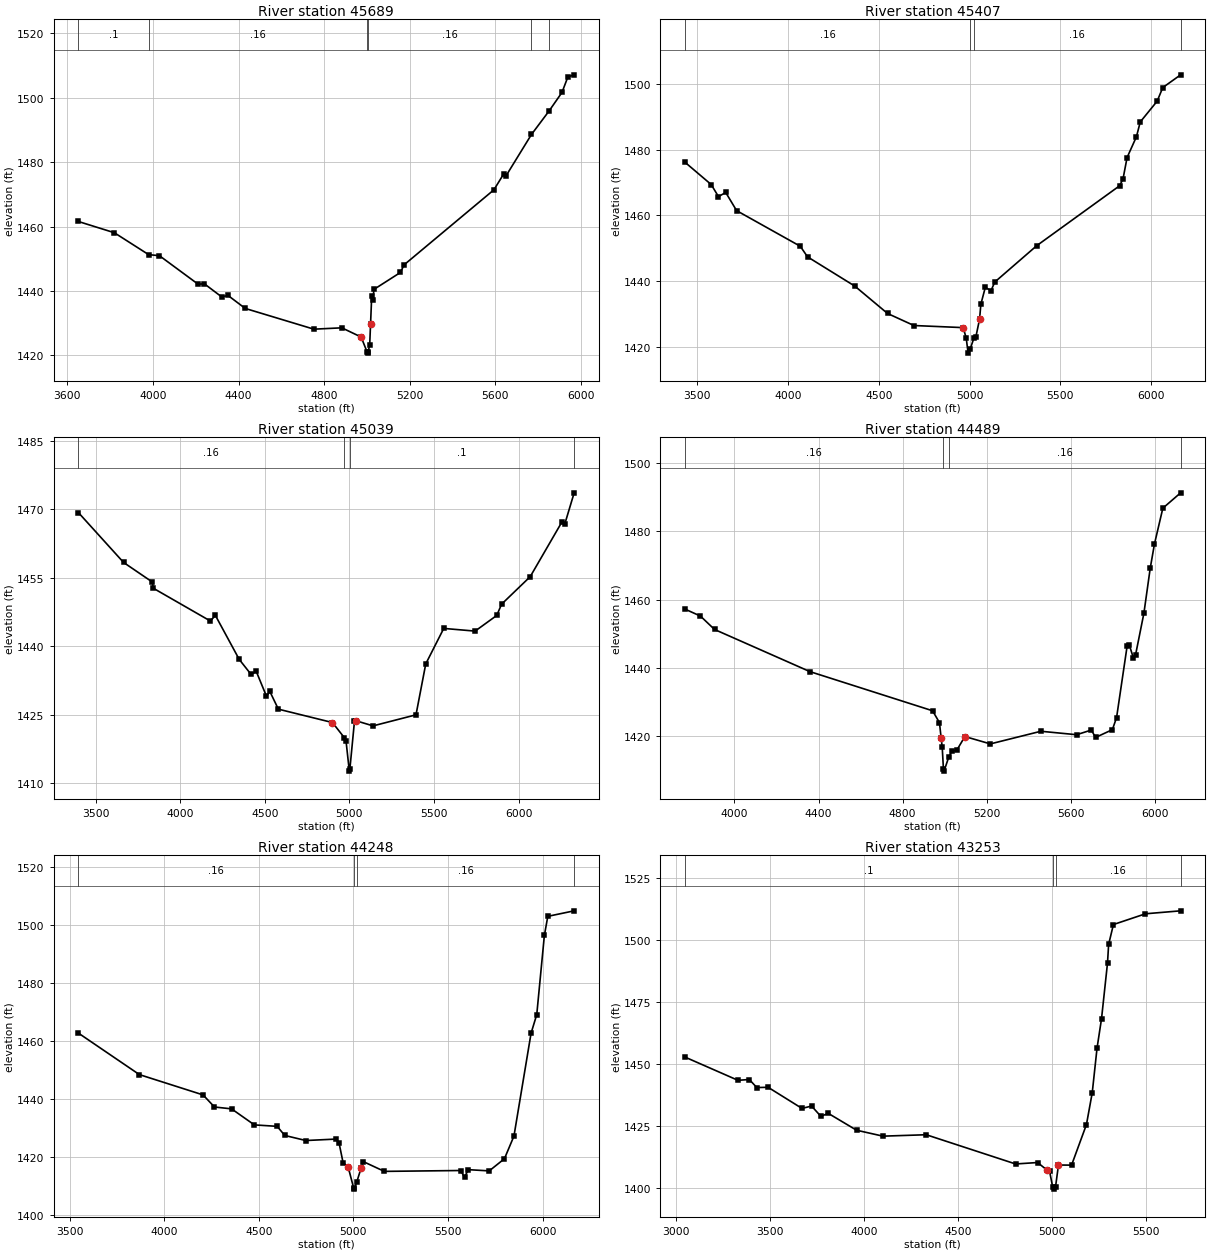
Type RM Length L Ch R = 1 ,45689   ,282,282,282
BEGIN DESCRIPTION:
TOWHEAD CREEK 85.0
END DESCRIPTION:
XS GIS Cut Line= 3
      2881350.75      10057986.3       2882977.7     10057858.69
      2883634.16     10057661.12
#Sta/Elev= 30
  3651.1 1461.57  3819.3 1458.08  3979.8 1451.27    4030 1450.95  4210.5 1442.11
  4240.6 1442.19  4320.9 1438.16    4351 1438.58  4431.2 1434.56  4752.2 1428.12
  4882.6 1428.54  4972.9 1425.68    5000 1421.18  5002.7 1420.68    5006 1421.18
    5013 1423.32    5017 1429.78  5022.4 1438.49  5027.4 1437.28  5033.1 1440.49
  5156.5 1445.73  5173.5 1448.09  5593.6 1471.41  5638.9  1476.3  5649.4 1475.66
  5769.1  1488.6  5851.6 1495.92  5911.6 1501.64  5939.4  1506.5  5968.6 1507.12
#Mann= 6 ,-1 , 0
  3651.1      .1       0  3979.8     .16       0    5000     .07       0
    5006     .16       0  5769.1     .05       0  5851.6      .1       0
Bank Sta=4972.9,5017
XS Rating Curve= 0 ,0
Exp/Cntr=0.3,0.1

Type RM Length L Ch R = 1 ,45407   ,368,368,368
BEGIN DESCRIPTION:
TOWHEAD CREEK 84.0
END DESCRIPTION:
XS GIS Cut Line= 4
      2881043.35      10058144.3      2882303.75     10058220.69
      2883025.97     10057991.53      2883713.45     10057807.51
#Sta/Elev= 30
    3431 1476.21  3576.4 1469.38  3616.5  1465.7  3656.5 1466.96  3716.6 1461.42
  4067.3 1450.57  4107.4 1447.34  4367.8 1438.43  4548.2 1430.09  4693.6 1426.42
  4965.4 1425.78  4981.9 1422.49  4992.2 1418.01    5003 1419.16  5023.9 1422.58
  5035.2 1423.05  5055.4 1428.41  5062.3 1432.91  5086.8 1438.03  5118.3 1437.06
  5139.3 1439.68  5370.1 1450.74  5826.7 1468.99  5845.6 1471.07  5868.1  1477.6
  5919.8 1483.97  5940.6 1488.44  6033.7 1494.77  6064.8 1498.92  6163.1  1502.8
#Mann= 4 ,-1 , 0
    3431     .16       0    5003     .07       0  5023.9     .16       0
  6163.1      .1       0
Bank Sta=4965.4,5055.4
XS Rating Curve= 0 ,0
Exp/Cntr=0.3,0.1

Type RM Length L Ch R = 1 ,45039   ,550,550,550
BEGIN DESCRIPTION:
TOWHEAD CREEK 83.0
END DESCRIPTION:
XS GIS Cut Line= 4
      2881032.97     10058359.59      2882182.22     10058488.05
      2882970.42     10058491.53      2883875.07     10058096.39
#Sta/Elev= 30
  3397.3 1469.33  3664.6  1458.4  3835.1  1454.1  3840.1 1452.76  4177.6 1445.58
  4207.8 1446.79  4348.7 1437.16  4419.1 1433.86  4449.3 1434.54  4509.7  1429.1
  4529.8 1430.14    4580 1426.27    4900 1423.34    4970 1420.03    4980 1419.36
  4999.7  1412.7    5003  1413.2    5030 1423.58    5040 1423.72    5140 1422.61
  5393.9 1425.03  5451.6 1436.18    5558 1443.95  5743.4 1443.36  5871.3 1446.79
  5900.1 1449.26  6069.4 1455.29  6256.4 1467.24    6273 1466.72  6329.1 1473.64
#Mann= 4 ,-1 , 0
  3397.3     .16       0    4970     .07       0    5003      .1       0
  6329.1      .1       0
Bank Sta=4900,5040
XS Rating Curve= 0 ,0
Exp/Cntr=0.3,0.1

Type RM Length L Ch R = 1 ,44489   ,241,241,241
BEGIN DESCRIPTION:
TOWHEAD CREEK 82.0
END DESCRIPTION:
XS GIS Cut Line= 4
      2881404.44     10059040.14      2882446.11     10059102.64
       2883022.5     10058838.75      2883703.03     10058838.75
#Sta/Elev= 30
  3763.8 1457.26    3838 1455.21  3905.2 1451.28  4358.9 1438.94  4942.1 1427.48
  4974.9 1424.01  4982.6 1419.65  4988.1 1416.74  4993.9 1410.31  4996.7 1409.81
  5018.9 1413.89  5034.2 1415.65  5057.2 1415.93  5095.9 1419.94  5216.9 1417.78
  5457.2 1421.48  5627.2 1420.47  5697.2 1421.84  5717.2 1419.67  5797.2 1421.95
  5817.2 1425.48  5867.2 1446.35  5877.2 1446.87  5897.2 1442.91  5907.2 1443.75
  5947.2 1456.05  5977.2  1469.2  5997.2 1476.25  6037.2 1486.78  6121.8 1491.28
#Mann= 4 ,-1 , 0
  3763.8     .16       0  4993.9     .07       0  5018.9     .16       0
  6121.8      .1       0
Bank Sta=4982.6,5095.9
XS Rating Curve= 0 ,0
Exp/Cntr=0.3,0.1

Type RM Length L Ch R = 1 ,44248   ,995,995,995
BEGIN DESCRIPTION:
TOWHEAD CREEK 81.0
END DESCRIPTION:
XS GIS Cut Line= 4
      2881341.96     10059248.47       2882522.5     10059359.58
      2883001.67     10059074.86       2883875.1     10058984.74
#Sta/Elev= 30
    3546 1462.87  3868.9 1448.54  4205.4 1441.54  4265.7 1437.37  4356.1 1436.73
  4476.6  1431.2  4597.1  1430.7  4637.3 1427.56  4748.8 1425.81  4908.5 1426.31
  4924.1 1425.03  4945.5 1418.21  4972.7 1416.63    5001 1409.55  5003.7 1409.05
  5017.9  1411.5    5041 1416.33  5052.8 1418.53  5163.7 1415.17  5567.4 1415.47
  5587.5 1413.13  5607.6 1415.76  5718.2 1415.34  5798.6 1419.53  5848.9 1427.34
  5939.4 1462.81  5969.5 1469.26  6009.7 1496.52  6027.9 1503.12  6167.2 1505.02
#Mann= 4 ,-1 , 0
    3546     .16       0    5001     .07       0  5017.9     .16       0
  6167.2      .1       0
Bank Sta=4972.7,5041
XS Rating Curve= 0 ,0
Exp/Cntr=0.3,0.1

Type RM Length L Ch R = 1 ,43253   ,544,544,544
BEGIN DESCRIPTION:
TOWHEAD CREEK 80.0
END DESCRIPTION:
XS GIS Cut Line= 3
      2881605.81     10059540.14      2883105.84      10059581.8
      2884174.33      10059200.2
#Sta/Elev= 30
  3049.1 1452.83  3331.9 1443.44  3391.9 1443.77  3431.9 1440.53  3491.9 1440.63
    3672 1432.13  3722.9 1433.09    3772 1428.96    3812 1430.12  3962.1 1423.35
  4102.2 1420.96  4332.3 1421.53  4807.3 1409.76  4924.1 1410.34  4973.5 1407.35
  4987.9  1406.8  5004.5 1400.41  5009.4 1399.63  5019.7 1400.67  5035.1 1409.34
  5104.7 1409.29  5183.8 1425.64  5214.6 1438.48    5240 1456.37  5263.9 1468.24
  5295.8 1490.75  5301.6 1498.14  5327.1 1506.17  5497.6  1510.5  5684.3 1511.69
#Mann= 4 ,-1 , 0
  3049.1      .1       0  5004.5     .07       0  5019.7     .16       0
  5684.3      .1       0
Bank Sta=4973.5,5035.1
XS Rating Curve= 0 ,0
Exp/Cntr=0.3,0.1

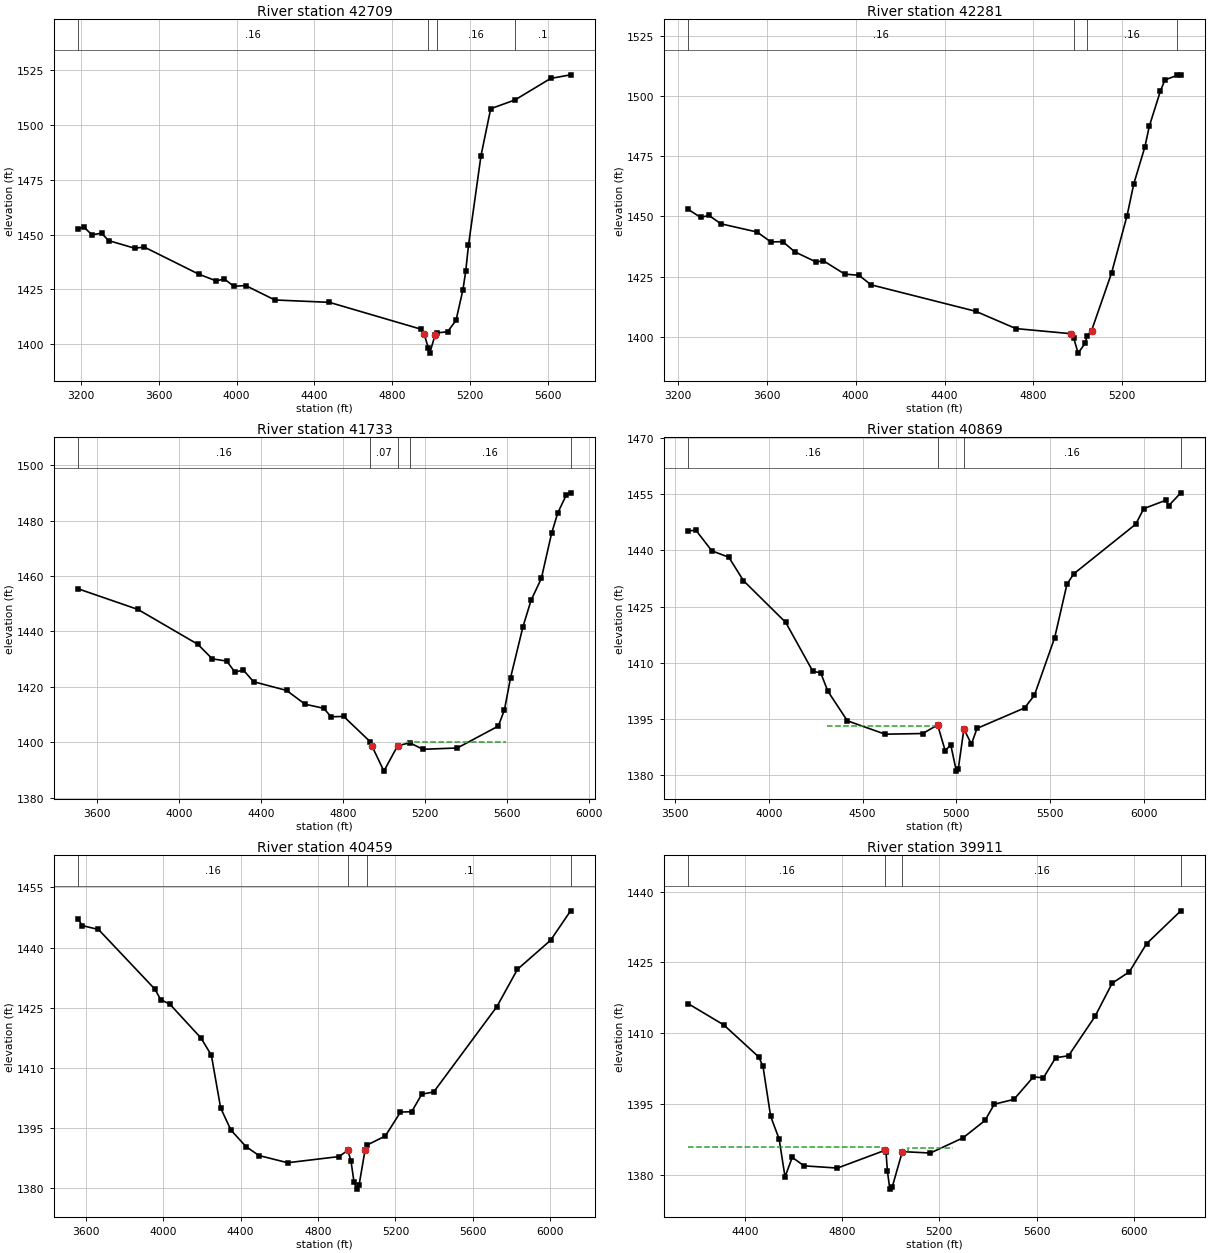
Type RM Length L Ch R = 1 ,42709   ,428,428,428
BEGIN DESCRIPTION:
TOWHEAD CREEK 78.0
END DESCRIPTION:
XS GIS Cut Line= 4
       2881588.5     10059640.83      2883119.72     10059717.22
      2883602.36     10060092.22       2883987.8     10060047.08
#Sta/Elev= 30
  3185.2 1452.57  3215.2 1453.37  3255.3 1449.92  3305.3 1450.56  3342.1 1447.23
  3475.5 1443.77  3525.6 1444.27  3805.9 1431.93    3896 1428.86  3936.1 1429.81
  3986.2  1426.4  4046.2 1426.79  4196.4 1420.21  4476.8 1419.13    4950 1406.86
  4964.5 1404.65  4985.3 1398.51  4993.2 1396.01  5020.7 1404.27  5028.7 1405.19
  5084.8 1405.74  5128.3 1410.91  5163.6 1424.75  5178.1  1433.2  5192.5 1445.18
  5256.8 1485.92  5306.6 1507.26  5431.4 1511.25    5615 1521.05  5717.6 1522.69
#Mann= 4 ,-1 , 0
  3185.2     .16       0  4985.3     .07       0  5028.7     .16       0
  5431.4      .1       0
Bank Sta=4964.5,5020.7
XS Rating Curve= 0 ,0
Exp/Cntr=0.3,0.1

Type RM Length L Ch R = 1 ,42281   ,548,548,548
BEGIN DESCRIPTION:
TOWHEAD CREEK 77.0
END DESCRIPTION:
XS GIS Cut Line= 3
      2881591.96     10059758.89      2882946.11     10060279.72
      2883709.97     10060300.55
#Sta/Elev= 30
  3247.8 1452.86    3303 1449.57  3340.5 1450.39  3394.1 1446.91    3557 1443.49
  3619.1 1439.37  3672.6 1439.49  3726.2 1435.28  3822.6 1431.04  3854.8 1431.56
  3951.2 1426.01  4015.5 1425.51    4069 1421.57  4540.5 1410.55    4721 1403.37
  4971.1 1401.22  4981.1 1399.42  5000.9 1393.17  5032.7 1397.28  5041.1 1400.31
  5061.2 1402.45  5151.2 1426.41  5221.2 1450.32  5251.2 1463.48  5301.2 1478.81
  5321.2 1487.48  5371.3 1502.11  5391.2 1506.69  5446.9 1508.61  5462.8 1508.81
#Mann= 4 ,-1 , 0
  3247.8     .16       0  4981.1     .07       0  5041.1     .16       0
  5446.9      .1       0
Bank Sta=4971.1,5061.2
XS Rating Curve= 0 ,0
Exp/Cntr=0.3,0.1

Type RM Length L Ch R = 1 ,41733   ,864,864,864
BEGIN DESCRIPTION:
TOWHEAD CREEK 76.0
END DESCRIPTION:
XS GIS Cut Line= 4
      2881418.29     10060630.42      2882650.97     10060488.05
      2883112.78     10060755.41      2883741.25     10060748.47
#Sta/Elev= 30
  3507.7 1455.36  3799.8 1447.91  4091.7 1435.34  4162.2 1430.09  4232.7 1429.29
  4272.9 1425.25  4313.2  1426.1  4363.5 1421.84  4524.6  1418.7  4615.2 1413.71
  4705.8 1412.26  4741.8 1409.19  4803.5 1409.31  4932.9 1400.18  4942.1 1398.52
  4999.6 1389.58  5066.4 1398.71  5125.9 1399.81  5189.8 1397.46  5357.9 1397.93
  5557.9 1405.83  5587.9 1411.72  5617.9 1423.35  5677.9  1441.6  5717.9 1451.27
  5767.9  1459.1  5817.9 1475.39  5847.9 1482.72  5889.9 1489.26  5910.7    1490
#Mann= 5 ,-1 , 0
  3507.7     .16       0  4932.9     .07       0  5066.4      .1       0
  5125.9     .16       0  5910.7      .1       0
#XS Ineff= 1 ,-1
 5113.64 5596.59 1400.13
Permanent Ineff=
       T
Bank Sta=4942.1,5066.4
XS Rating Curve= 0 ,0
Exp/Cntr=0.3,0.1

Type RM Length L Ch R = 1 ,40869   ,410,410,410
BEGIN DESCRIPTION:
TOWHEAD CREEK 74.0
END DESCRIPTION:
XS GIS Cut Line= 4
      2881682.27     10061210.28      2882567.64     10061415.14
      2883241.25     10061415.14      2884142.55     10060888.22
#Sta/Elev= 30
  3570.4 1445.18  3610.3 1445.42  3695.7 1439.89  3786.3 1438.18  3864.2 1431.93
    4090 1420.76  4233.9 1407.76  4276.6 1407.28  4314.2 1402.43  4418.4 1394.51
    4620 1390.93    4820 1391.11    4900 1393.39    4940 1386.55    4970 1388.06
  4999.7 1381.07    5010 1381.62    5040 1392.32    5080 1388.28    5110 1392.48
  5363.7 1397.94    5416 1401.32  5524.1 1416.69  5589.7 1430.97  5625.7 1433.74
  5956.3    1447  5999.3 1451.16  6116.7 1453.39  6132.4 1451.95  6196.8 1455.38
#Mann= 4 ,-1 , 0
  3570.4     .16       0    4900     .07       0    5040     .16       0
  6196.8      .1       0
#XS Ineff= 1 ,-1
 4309.66 4890.91 1393.22
Permanent Ineff=
       T
Bank Sta=4900,5040
XS Rating Curve= 0 ,0
Exp/Cntr=0.3,0.1

Type RM Length L Ch R = 1 ,40459   ,548,548,548
BEGIN DESCRIPTION:
TOWHEAD CREEK 73.0
END DESCRIPTION:
XS GIS Cut Line= 4
      2881644.04     10061290.14      2882640.56     10061696.39
      2883331.53     10061908.19       2884071.1     10061991.52
#Sta/Elev= 30
  3561.6 1447.06  3583.5 1445.48  3666.4 1444.52  3957.9 1429.64  3987.5 1427.06
  4035.4 1425.88  4195.9 1417.46  4249.4 1413.19  4297.5    1400  4350.9 1394.48
  4428.5 1390.39  4495.1 1388.17  4643.3 1386.37  4907.5  1387.9  4953.7 1389.42
  4970.3 1386.87  4986.5 1381.45  5001.4 1379.79  5012.1 1380.75  5043.5 1389.63
    5052 1390.74  5148.1 1393.04  5226.2    1399    5284 1399.09  5336.3 1403.47
  5397.6    1404  5723.6 1425.26  5830.3 1434.59  6001.4 1441.83  6104.7 1449.17
#Mann= 4 ,-1 , 0
  3561.6     .16       0  4953.7     .07       0    5052      .1       0
  6104.7      .1       0
Bank Sta=4953.7,5043.5
XS Rating Curve= 0 ,0
Exp/Cntr=0.3,0.1

Type RM Length L Ch R = 1 ,39911   ,1096,1096,1096
BEGIN DESCRIPTION:
TOWHEAD CREEK 71.0
END DESCRIPTION:
XS GIS Cut Line= 4
      2881953.05     10062515.83       2882623.2     10062248.47
      2883081.53     10062352.64      2883907.91     10062231.11
#Sta/Elev= 30
    4167 1416.24  4312.8 1411.75  4457.1 1404.94  4474.3 1402.93  4505.6 1392.38
  4540.6 1387.55  4564.9  1379.5  4594.5 1383.65    4643 1381.85  4780.5 1381.38
  4975.4 1385.13  4980.5 1384.82  4986.2 1380.77  4996.2 1376.91  5006.7 1377.46
  5047.7 1384.87    5163 1384.57  5297.4 1387.79  5388.1 1391.48  5426.2 1394.93
    5507 1395.95  5587.2 1400.73  5628.3 1400.52  5678.9  1404.8  5731.7  1405.2
  5840.6 1413.55  5911.4  1420.6  5982.1 1423.02  6052.9 1428.98  6193.8 1435.96
#Mann= 4 ,-1 , 0
    4167     .16       0  4975.4     .09       0  5047.7     .16       0
  6193.8      .1       0
#XS Ineff= 2 ,-1
 4119.32 4964.49 1385.94 5072.44  5257.1 1385.59
Permanent Ineff=
       T       T
Bank Sta=4975.4,5047.7
XS Rating Curve= 0 ,0
Exp/Cntr=0.3,0.1

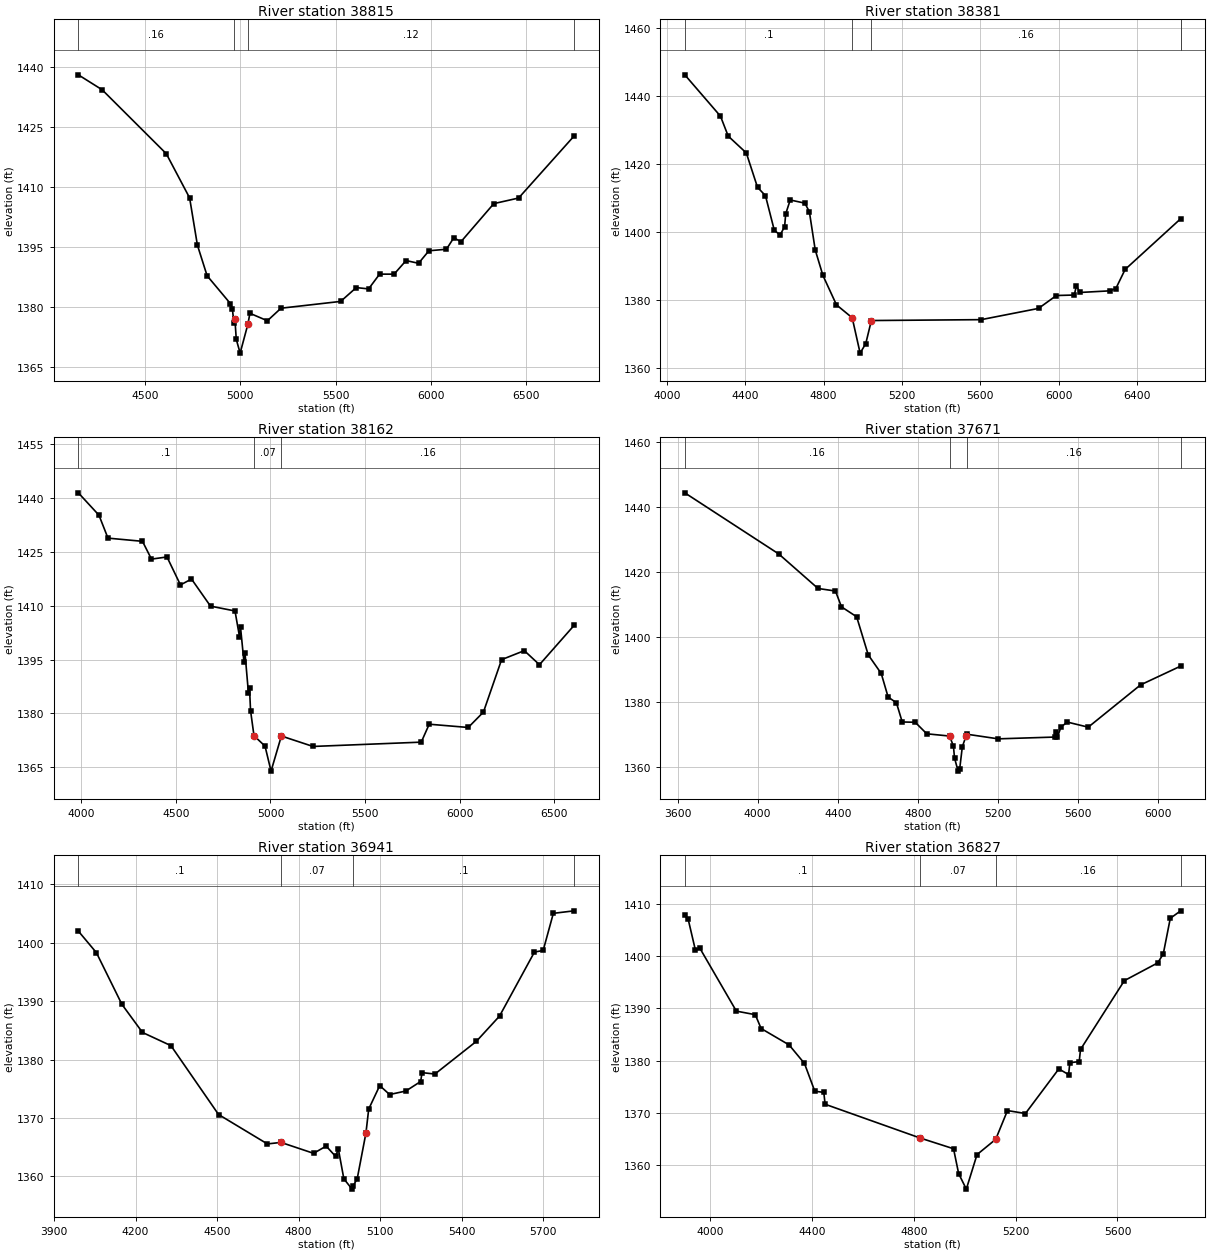
Type RM Length L Ch R = 1 ,38815   ,434,434,434
BEGIN DESCRIPTION:
TOWHEAD CREEK 70.0
END DESCRIPTION:
XS GIS Cut Line= 4
      2881446.11     10062654.72      2882602.36     10062890.83
      2883439.17     10063251.94       2883949.6     10063279.72
#Sta/Elev= 30
  4149.2    1438  4274.2 1434.26  4610.9 1418.26  4733.4  1407.2  4774.2 1395.39
  4825.2 1387.72  4947.7 1380.74  4957.9 1379.37    4966 1375.89  4971.1 1376.83
  4978.3  1371.8  4998.5 1368.36  5039.6 1375.66  5049.8 1378.33  5141.6 1376.46
  5213.1  1379.6  5526.2  1381.3  5608.2 1384.76  5672.8 1384.43  5730.7 1388.13
  5806.6 1388.12  5869.6 1391.52  5935.1 1390.84  5989.4 1393.97  6081.6 1394.36
  6120.1 1397.23  6157.6 1396.23  6330.1 1405.77  6460.3 1407.17  6751.9 1422.71
#Mann= 4 ,-1 , 0
  4149.2     .16       0    4966     .09       0  5039.6     .12       0
  6751.9      .1       0
Bank Sta=4971.1,5039.6
XS Rating Curve= 0 ,0
Exp/Cntr=0.3,0.1

Type RM Length L Ch R = 1 ,38381   ,219,219,219
BEGIN DESCRIPTION:
TOWHEAD CREEK 69.0
END DESCRIPTION:
XS GIS Cut Line= 4
      2881362.78     10062866.52      2882553.75     10063408.19
       2883272.5       10063745.      2883694.75     10063814.22
#Sta/Elev= 30
  4091.8 1446.13  4273.8 1433.99  4313.4 1428.13  4405.6  1423.2  4462.8 1413.11
  4503.4 1410.64  4548.5 1400.48  4578.1  1399.1  4601.1 1401.54  4606.6 1405.28
  4629.7 1409.38  4704.4 1408.45  4727.4 1405.94  4757.2 1394.74  4796.6 1387.22
  4865.8 1378.58    4946 1374.79  4986.4 1364.41  5015.2 1367.21  5043.7 1373.98
  5604.2 1374.24  5896.6 1377.54  5987.9 1381.33    6079 1381.47  6090.2 1384.18
  6107.5 1382.22  6260.8  1382.7  6291.2 1383.37  6338.7 1388.99  6621.8 1403.86
#Mann= 5 ,-1 , 0
  4091.8      .1       0    4946     .07       0  5043.7     .16       0
  6621.8     .08       0  6621.8     .05       0
Bank Sta=4946,5043.7
XS Rating Curve= 0 ,0
Exp/Cntr=0.3,0.1

Type RM Length L Ch R = 1 ,38162   ,491,491,491
BEGIN DESCRIPTION:
TOWHEAD CREEK 68.0
END DESCRIPTION:
XS GIS Cut Line= 4
      2881300.31     10063057.51        2882585.     10063599.16
       2883272.5     10063887.36      2883751.72     10063890.83
#Sta/Elev= 30
    3985 1441.47    4094 1435.23  4141.5 1428.84  4323.8 1427.95  4371.3 1422.99
  4453.3 1423.59  4524.4 1415.79  4582.7 1417.44  4683.1 1409.88  4812.5 1408.53
  4836.2  1401.4  4841.7 1403.98    4860 1394.21  4865.4 1396.74  4883.7 1385.53
  4889.1 1387.18  4894.6 1380.76  4912.8 1373.75  4971.1 1370.85  5002.9 1363.88
  5057.4 1373.67  5224.6 1370.76  5796.2 1371.96  5838.3 1376.96  6044.4 1376.05
  6124.7 1380.34  6220.6 1394.96  6340.6 1397.47  6420.6 1393.55  6603.9 1404.53
#Mann= 3 , 0 , 0
    3985      .1       0  4912.8     .07       0  5057.4     .16       0
Bank Sta=4912.8,5057.4
XS Rating Curve= 0 ,0
Exp/Cntr=0.3,0.1

Type RM Length L Ch R = 1 ,37671   ,730,730,730
BEGIN DESCRIPTION:
TOWHEAD CREEK 67.0
END DESCRIPTION:
XS GIS Cut Line= 5
      2881317.65     10063286.67      2882328.06     10063724.16
      2882501.67      10063831.8      2882692.64     10063765.83
      2883619.73     10064050.56
#Sta/Elev= 30
  3636.1 1444.42  4105.6 1425.61  4301.7    1415  4388.9 1414.21  4418.8 1409.35
  4494.7 1406.29  4552.6 1394.57  4617.5 1388.85  4651.9  1381.6  4693.4 1379.83
  4722.4 1373.93  4787.2 1373.84  4845.1 1370.29  4959.2  1369.6  4978.3 1366.47
  4983.6  1362.9  5001.3 1358.81  5009.4 1359.44  5022.7 1366.33  5040.6 1369.47
  5045.9 1370.16  5201.9 1368.74  5484.3 1369.29  5491.8 1370.77    5497 1369.19
  5515.7 1372.38  5547.1  1373.9  5651.7 1372.33  5913.2 1385.34  6113.3 1391.11
#Mann= 4 ,-1 , 0
  3636.1     .16       0  4959.2     .07       0  5045.9     .16       0
  6113.3     .05       0
Bank Sta=4959.2,5040.6
XS Rating Curve= 0 ,0
Exp/Cntr=0.3,0.1

Type RM Length L Ch R = 1 ,36941   ,114,114,114
BEGIN DESCRIPTION:
TOWHEAD CREEK 66.0
END DESCRIPTION:
XS GIS Cut Line= 5
      2882140.53     10064033.18      2882668.34     10064262.36
      2882984.31     10064262.36       2883623.2     10064151.25
      2883893.78     10064064.52
#Sta/Elev= 30
  3989.6    1402    4056 1398.31  4149.8 1389.46  4225.6 1384.64  4330.3 1382.38
  4505.4 1370.59  4685.1 1365.55  4735.1 1365.81  4855.1 1363.94  4901.3 1365.18
    4936 1363.42  4946.1 1364.69  4966.4 1359.57  4996.6 1357.81  4999.9 1358.31
  5015.5 1359.59  5047.6 1367.41  5057.8 1371.52  5098.4 1375.54  5134.7 1374.01
  5194.4 1374.61  5248.9 1376.24    5254 1377.76  5301.4 1377.52  5453.6 1383.11
    5539 1387.44  5667.5 1398.41  5699.6 1398.68    5737 1405.04  5813.6 1405.47
#Mann= 4 ,-1 , 0
  3989.6      .1       0  4735.1     .07       0  4999.9      .1       0
  5813.6     .08       0
Bank Sta=4735.1,5047.6
XS Rating Curve= 0 ,0
Exp/Cntr=0.3,0.1

Type RM Length L Ch R = 1 ,36827   ,463,463,463
BEGIN DESCRIPTION:
TOWHEAD CREEK 65.0
END DESCRIPTION:
XS GIS Cut Line= 6
      2882102.41     10064182.52      2882425.28      10064331.8
      2882789.86     10064383.89      2883550.28     10064283.19
      2883793.34     10064224.16      2883975.68     10064127.83
#Sta/Elev= 30
  3900.6 1407.73  3914.1 1406.96  3942.5 1401.05    3960 1401.45  4103.1 1389.46
  4177.4 1388.78  4200.3 1386.14  4310.2 1383.01  4370.7 1379.46  4411.1 1374.17
  4446.6 1373.94  4451.6 1371.68  4824.9 1365.23  4956.1 1363.18  4976.2 1358.43
  5006.3 1355.47  5048.3 1362.06  5121.7 1364.98  5167.9 1370.47  5238.5 1369.91
  5369.7 1378.43  5407.9 1377.34    5413  1379.6  5449.7 1379.83  5454.8 1382.14
    5627 1395.28  5757.7 1398.66  5779.7 1400.35  5807.4 1407.18    5848 1408.61
#Mann= 4 ,-1 , 0
  3900.6      .1       0  4824.9     .07       0  5121.7     .16       0
    5848     .08       0
Bank Sta=4824.9,5121.7
XS Rating Curve= 0 ,0
Exp/Cntr=0.3,0.1