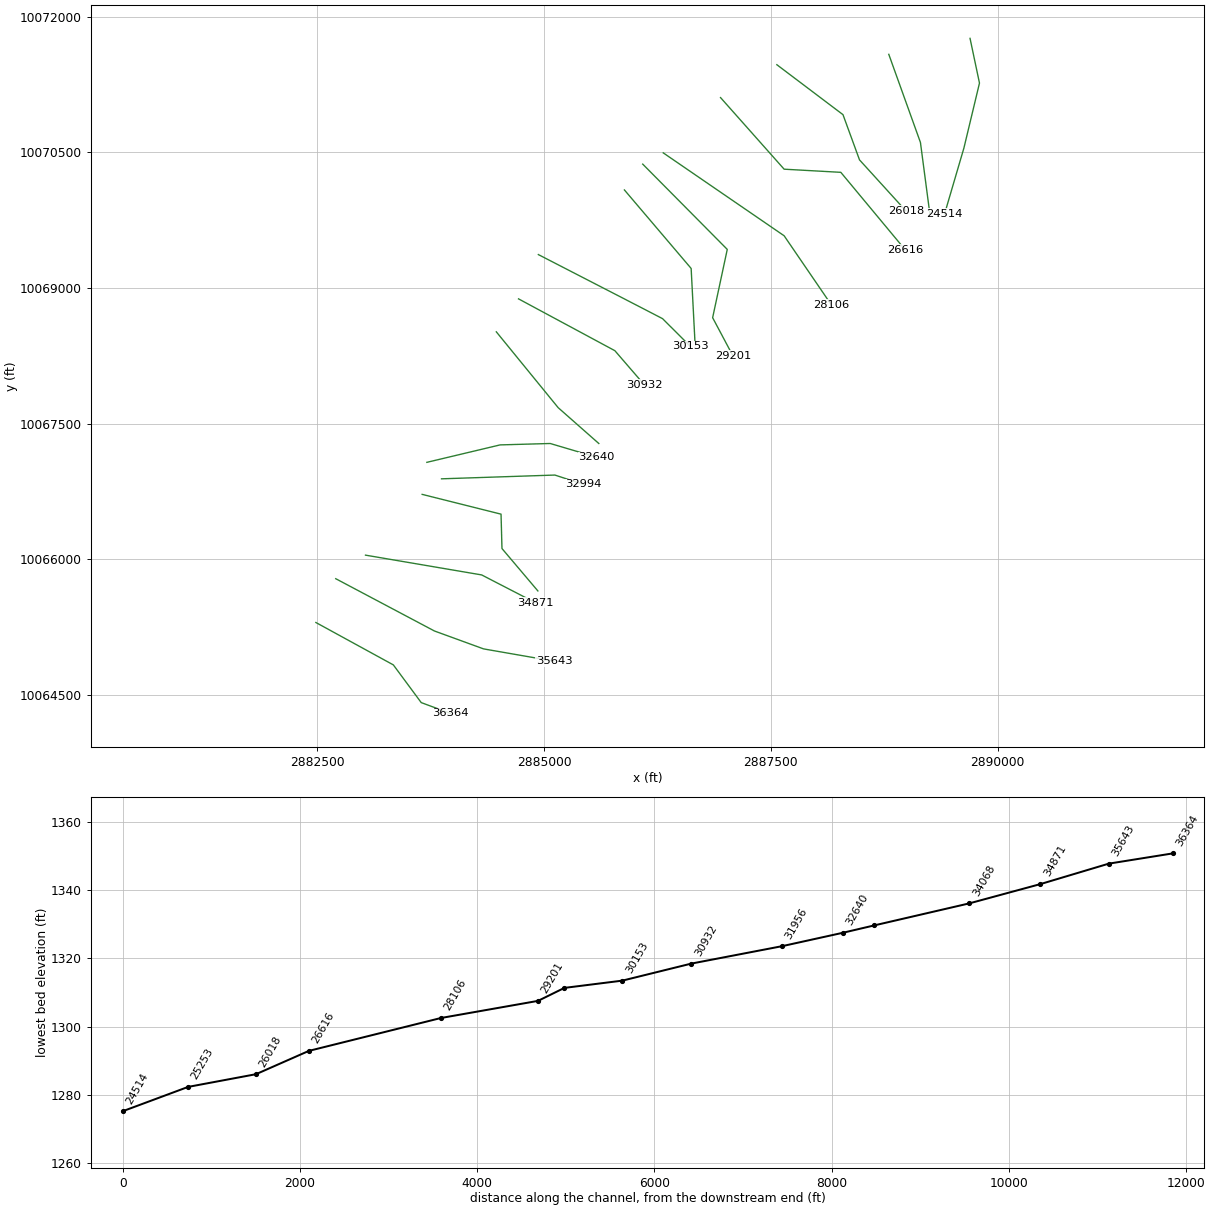
HEC-RAS study TOWHEAD CREEK.prj: TOWHEAD CREEK Base Level Engineering

--- TOWHEAD CREEK.g01 (geometry) --- (continued)

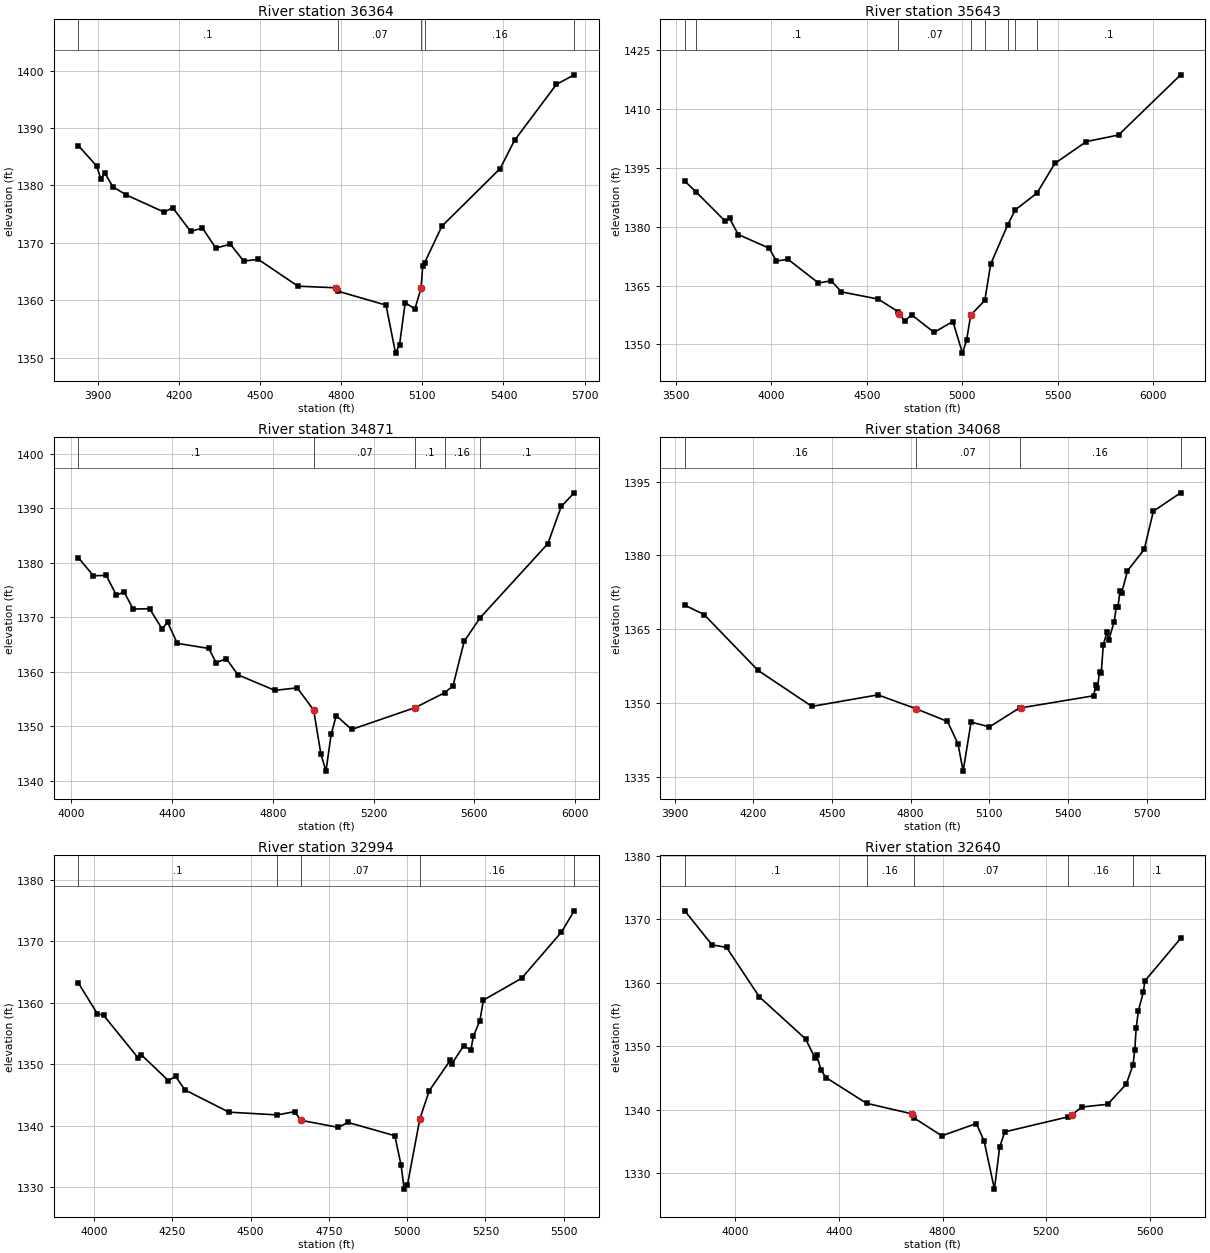
Type RM Length L Ch R = 1 ,36364   ,721,721,721
BEGIN DESCRIPTION:
TOWHEAD CREEK 64.0
END DESCRIPTION:
XS GIS Cut Line= 4
      2882482.54     10065300.57      2883336.74      10064831.8
      2883644.03     10064415.14      2883965.25     10064295.97
#Sta/Elev= 30
  3826.8 1386.93  3894.6 1383.36  3910.7 1381.04  3924.8 1382.16  3954.3 1379.77
  4004.7 1378.32  4144.8 1375.33  4175.8 1376.12  4242.4 1371.98    4286 1372.57
  4335.5 1369.07  4389.3 1369.76  4438.6 1366.81  4492.6 1367.11  4639.5 1362.44
  4780.3 1362.16  4786.4 1361.58  4965.3 1359.14  5000.6 1350.78  5015.4 1352.25
  5036.3 1359.57  5072.1 1358.47  5094.8 1362.04  5101.1 1365.88  5108.4 1366.54
    5172 1372.89  5387.6 1382.92  5440.9 1387.84  5595.8 1397.58  5661.5 1399.25
#Mann= 5 ,-1 , 0
  3826.8      .1       0  4786.4     .07       0  5094.8      .1       0
  5108.4     .16       0  5661.5     .05       0
Bank Sta=4780.3,5094.8
XS Rating Curve= 0 ,0
Exp/Cntr=0.3,0.1

Type RM Length L Ch R = 1 ,35643   ,772,772,772
BEGIN DESCRIPTION:
TOWHEAD CREEK 62.0
END DESCRIPTION:
XS GIS Cut Line= 4
      2882701.29     10065784.94      2883789.86      10065206.8
      2884331.53     10065008.89      2885107.54     10064873.48
#Sta/Elev= 30
  3546.9 1391.57  3604.7  1388.9  3758.8 1381.37  3781.5 1382.09  3826.8 1377.99
  3988.7 1374.51    4027 1371.23  4087.2 1371.68  4246.9 1365.65  4313.7  1366.2
  4367.4 1363.37  4559.6 1361.55  4663.9 1358.36  4669.5 1357.76  4698.6 1356.03
  4735.5 1357.52  4852.5 1353.07  4951.2 1355.83  5001.3 1347.78  5022.9 1351.07
  5044.2 1357.44  5118.4 1361.22    5149 1370.46  5238.9 1380.52  5277.8 1384.26
  5391.8 1388.56    5485  1396.1  5650.2 1401.66  5818.7 1403.33  6143.9 1418.66
#Mann= 8 ,-1 , 0
  3546.9     .16       0  3604.7      .1       0  4663.9     .07       0
  5044.2      .1       0  5118.4     .16       0  5238.9      .1       0
  5277.8     .16       0  5391.8      .1       0
Bank Sta=4669.5,5044.2
XS Rating Curve= 0 ,0
Exp/Cntr=0.3,0.1

Type RM Length L Ch R = 1 ,34871   ,803,803,803
BEGIN DESCRIPTION:
TOWHEAD CREEK 61.0
END DESCRIPTION:
XS GIS Cut Line= 3
      2883029.46     10066045.34       2884310.7     10065826.59
      2884903.98     10065519.55
#Sta/Elev= 30
    4028 1380.94  4087.9 1377.61  4138.6 1377.69  4179.2 1374.05  4209.6 1374.65
  4245.3 1371.52    4311 1371.56  4360.5 1367.86  4382.1  1369.1  4420.7 1365.22
    4546 1364.28  4574.8 1361.66  4615.4 1362.41  4661.3 1359.45  4808.1 1356.59
  4896.8 1357.06    4962 1352.97  4990.7 1344.89  5010.8 1341.78  5031.3  1348.5
  5051.6 1351.97  5112.5 1349.42  5365.7 1353.45  5481.3 1356.15    5515 1357.42
  5559.3 1365.59    5622 1369.87  5891.3  1383.5  5944.6 1390.33  5995.8 1392.83
#Mann= 5 ,-1 , 0
    4028      .1       0    4962     .07       0  5365.7      .1       0
  5481.3     .16       0    5622      .1       0
Bank Sta=4962,5365.7
XS Rating Curve= 0 ,0
Exp/Cntr=0.3,0.1

Type RM Length L Ch R = 1 ,34068   ,1074,1074,1074
BEGIN DESCRIPTION:
TOWHEAD CREEK 60.0
END DESCRIPTION:
XS GIS Cut Line= 4
      2883654.48     10066717.21      2884524.24     10066498.47
      2884534.65     10066118.26      2884930.48     10065649.52
#Sta/Elev= 30
  3938.7 1369.85  4012.1 1367.96  4217.8 1356.61  4423.4 1349.28  4675.3 1351.62
  4819.3 1348.83  4940.3 1346.22  4980.3  1341.7  5000.1 1336.12  5030.3 1346.09
  5100.4 1345.12  5215.7    1349  5222.1    1349  5498.1 1351.44  5505.9 1353.72
  5512.4 1353.09  5520.2 1356.37  5526.7 1356.12  5534.5 1361.77  5548.8 1364.39
  5555.3 1362.82  5576.1 1366.47  5583.9 1369.47  5590.4 1369.53  5598.2 1372.67
  5604.7 1372.38  5626.8 1376.86  5690.5 1381.18  5725.6 1388.97  5829.4  1392.7
#Mann= 4 ,-1 , 0
  3938.7     .16       0  4819.3     .07       0  5215.7     .16       0
  5829.4      .1       0
Bank Sta=4819.3,5222.1
XS Rating Curve= 0 ,0
Exp/Cntr=0.3,0.1

Type RM Length L Ch R = 1 ,32994   ,354,354,354
BEGIN DESCRIPTION:
TOWHEAD CREEK 58.0
END DESCRIPTION:
XS GIS Cut Line= 3
      2883868.01      10066889.1      2885117.99     10066930.76
      2885434.53     10066826.98
#Sta/Elev= 30
  3949.7 1363.25  4010.2 1358.24  4030.2 1357.98  4140.3 1351.06  4150.3 1351.56
  4237.1 1347.34  4260.3 1348.01  4290.3 1345.82  4430.4 1342.19  4585.5 1341.74
  4640.5 1342.27  4660.6 1340.86  4780.6 1339.71  4810.6 1340.52  4960.7 1338.35
  4980.7 1333.54  4990.5 1329.65  5000.7 1330.26  5040.8 1341.15  5070.8  1345.7
  5137.6 1350.62  5142.6 1350.05  5180.8 1353.03  5203.3 1352.29  5211.8 1354.59
  5232.4 1357.09  5243.6 1360.44  5365.7    1364    5493 1371.53  5533.5 1374.99
#Mann= 5 ,-1 , 0
  3949.7      .1       0  4585.5     .16       0  4660.6     .07       0
  5040.8     .16       0  5533.5      .1       0
Bank Sta=4660.6,5040.8
XS Rating Curve= 0 ,0
Exp/Cntr=0.3,0.1

Type RM Length L Ch R = 1 ,32640   ,684,684,684
BEGIN DESCRIPTION:
TOWHEAD CREEK 57.0
END DESCRIPTION:
XS GIS Cut Line= 4
      2883706.49     10067071.38      2884513.82     10067264.09
       2885065.9     10067279.72      2885574.78     10067129.13
#Sta/Elev= 30
  3805.2 1371.32    3910 1365.96  3966.3 1365.56  4092.6 1357.78  4271.3 1351.14
  4308.2 1348.08  4313.4 1348.65  4331.6 1346.18  4350.3 1345.05  4506.3 1341.01
  4679.9 1339.36  4689.9 1338.69    4797 1335.89    4930 1337.82    4960 1335.07
  4999.8 1327.49    5020 1334.11    5040 1336.51    5284 1338.87  5298.2 1339.17
  5336.7 1340.42  5436.5 1340.85  5508.2 1344.01  5534.3 1347.03  5541.5 1349.47
  5546.7 1352.85  5555.2 1355.58  5574.7 1358.57    5580 1360.27  5718.2 1366.98
#Mann= 5 ,-1 , 0
  3805.2      .1       0  4506.3     .16       0  4689.9     .07       0
    5284     .16       0  5534.3      .1       0
Bank Sta=4679.9,5298.2
XS Rating Curve= 0 ,0
Exp/Cntr=0.3,0.1

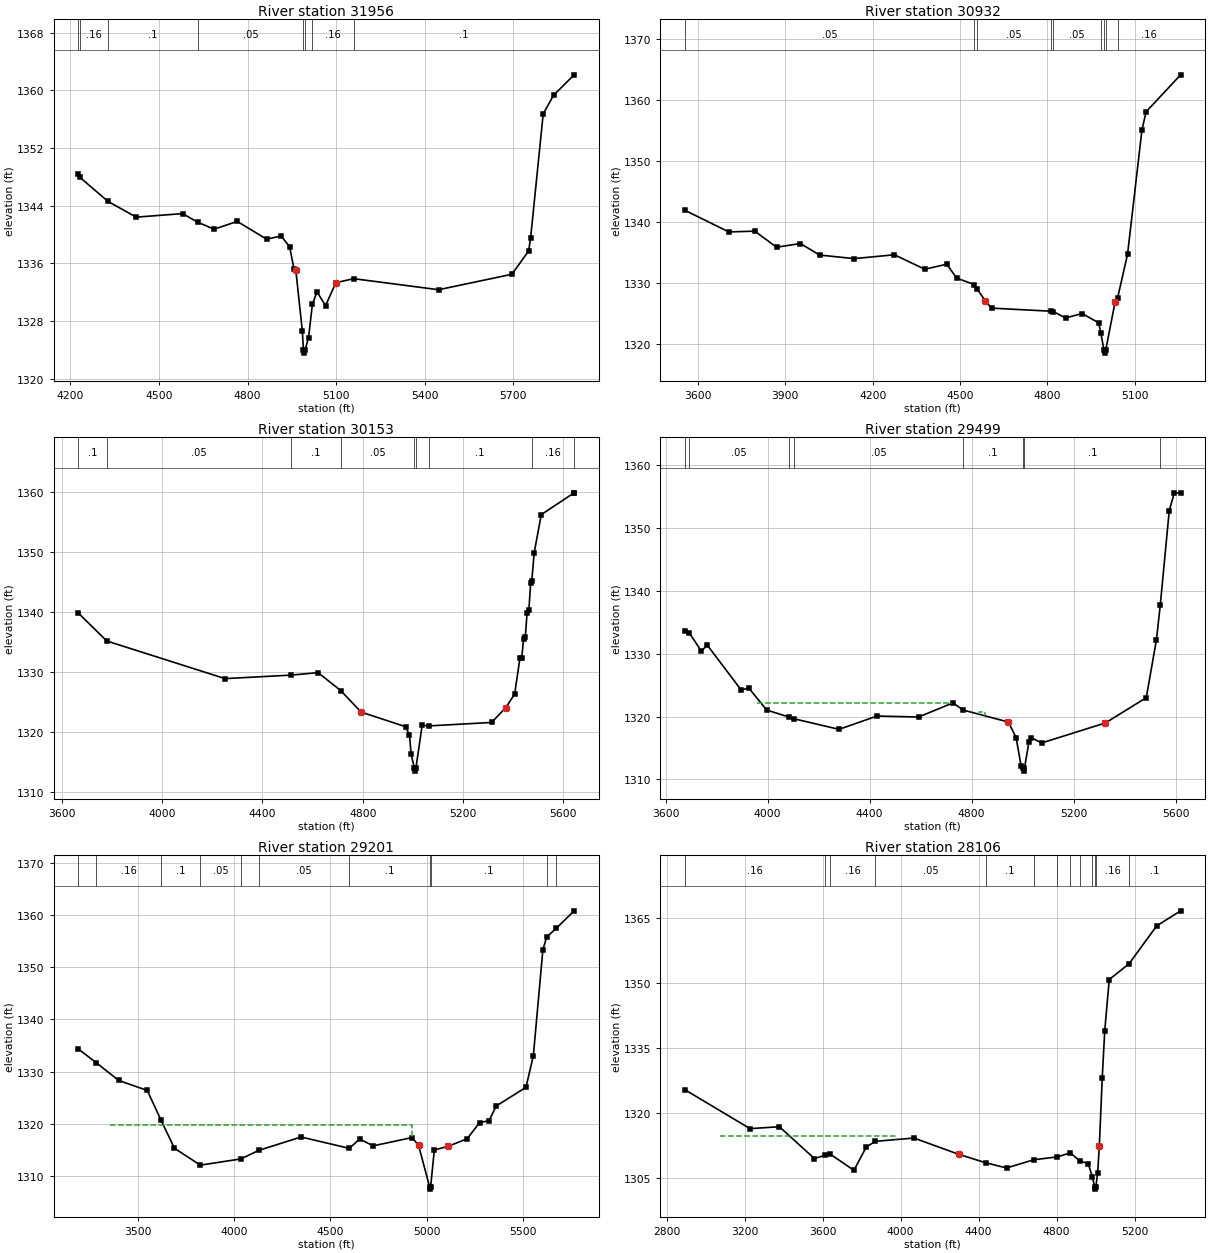
Type RM Length L Ch R = 1 ,31956   ,1024,1024,1024
BEGIN DESCRIPTION:
TOWHEAD CREEK 56.0
END DESCRIPTION:
XS GIS Cut Line= 3
      2884472.18     10068514.06      2885154.45     10067675.55
      2885602.39      10067279.7
#Sta/Elev= 30
  4227.1 1348.38  4232.7 1347.93  4327.9 1344.59  4423.3 1342.42  4579.9 1342.91
  4631.2 1341.72  4686.9 1340.75  4765.2 1341.83  4864.3 1339.37  4913.9  1339.8
  4942.6 1338.31    4957 1335.28  4963.4  1335.1  4985.7 1326.58  4989.1 1324.07
  4991.9 1323.57  4995.1 1324.07  5006.5 1325.69  5019.6 1330.33  5035.2 1332.07
    5064 1330.15  5099.2 1333.34  5159.5 1333.89  5446.9 1332.36  5694.9  1334.5
  5751.8 1337.73  5758.4 1339.51  5801.1 1356.74  5836.2 1359.32  5905.9 1362.15
#Mann= 8 ,-1 , 0
  4227.1      .1       0  4232.7     .16       0  4327.9      .1       0
  4631.2     .05       0  4989.1    .035       0  4995.1     .05       0
  5019.6     .16       0  5159.5      .1       0
Bank Sta=4963.4,5099.2
XS Rating Curve= 0 ,0
Exp/Cntr=0.3,0.1

Type RM Length L Ch R = 1 ,30932   ,779,779,779
BEGIN DESCRIPTION:
TOWHEAD CREEK 55.0
END DESCRIPTION:
XS GIS Cut Line= 3
      2884716.96     10068878.67      2885779.45     10068305.76
      2886102.38     10067930.75
#Sta/Elev= 30
    3555 1341.92  3706.2 1338.36  3795.3 1338.49    3870 1335.85  3951.9 1336.46
  4017.6 1334.57  4136.1 1333.98  4274.7 1334.61  4378.5 1332.24  4454.2 1333.06
  4488.3 1330.78  4548.7 1329.72  4558.4    1329  4586.1 1327.08    4608 1325.85
  4812.8 1325.34  4819.7 1325.29    4862 1324.24    4919 1324.96  4975.9 1323.43
  4983.1 1321.75  4993.9 1318.96  4996.7 1318.46  4999.9 1318.96  5032.1 1326.87
  5040.6  1327.5  5074.8  1334.7  5124.2  1355.1  5138.5 1358.09    5257 1364.16
#Mann= 9 ,-1 , 0
    3555     .05       0  4548.7      .1       0  4558.4     .05       0
  4812.8      .1       0  4819.7     .05       0  4983.1      .1       0
  4993.9     .07       0  4999.9      .1       0  5040.6     .16       0
Bank Sta=4586.1,5032.1
XS Rating Curve= 0 ,0
Exp/Cntr=0.3,0.1

Type RM Length L Ch R = 1 ,30153   ,654,654,654
BEGIN DESCRIPTION:
TOWHEAD CREEK 54.0
END DESCRIPTION:
XS GIS Cut Line= 4
      2884935.73     10069368.25      2885883.61     10068878.68
      2886305.49     10068659.93      2886612.75     10068352.66
#Sta/Elev= 30
  3666.4 1339.86    3780 1335.19  4251.4 1328.91  4515.7  1329.5  4622.4 1329.91
  4712.7  1326.9  4793.9 1323.32  4970.9 1320.88  4986.5 1319.52    4993  1316.3
  5006.1 1313.96  5008.8 1313.46  5012.1 1313.96  5037.2 1321.13  5063.3 1321.01
  5313.9 1321.59  5370.5 1324.06  5405.9 1326.35  5427.1 1332.41  5434.2  1332.4
  5441.2 1335.51  5448.3 1335.94  5455.4 1339.91  5462.4 1340.32  5469.5  1344.8
  5473.9 1345.15  5483.7 1349.94  5511.9  1356.3  5642.8 1359.94    5643 1359.94
#Mann= 9 ,-1 , 0
  3666.4      .1       0    3780     .05       0  4515.7      .1       0
  4712.7     .05       0  5006.1    .035       0  5012.1     .05       0
  5063.3      .1       0  5473.9     .16       0  5642.8      .1       0
Bank Sta=4793.9,5370.5
XS Rating Curve= 0 ,0
Exp/Cntr=0.3,0.1

Type RM Length L Ch R = 1 ,29499   ,298,298,298
BEGIN DESCRIPTION:
Mapping XS d2d70c3c
END DESCRIPTION:
XS GIS Cut Line= 3
      2885884.68     10070082.83      2886620.77     10069214.79
      2886662.44     10068409.19
#Sta/Elev= 30
  3675.1 1333.63  3691.7 1333.38  3740.6  1330.4  3762.6 1331.42  3896.8 1324.21
  3925.1  1324.6  3996.5 1321.05    4085 1319.92  4101.7 1319.68  4279.9 1317.98
  4429.3  1320.1  4591.9 1319.94    4727 1322.19  4766.9 1321.05  4944.5 1319.14
  4974.5 1316.67  4994.5 1312.11  5001.5 1311.83  5004.3 1311.33  5007.5 1311.83
  5024.6 1315.89  5034.6 1316.66  5074.6 1315.81    5325    1319  5485.2 1323.02
  5525.2 1332.27  5540.1 1337.77  5575.3 1352.79  5595.3 1355.62  5619.9 1355.55
#Mann= 8 ,-1 , 0
  3675.1      .1       0  3691.7     .05       0    4085      .1       0
  4101.7     .05       0  4766.9      .1       0  5001.5     .07       0
  5007.5      .1       0  5540.1     .16       0
#XS Ineff= 2 ,-1
 3958.08 4720.62 1322.16 4827.99 4853.56 1320.71
Permanent Ineff=
       T       T
Bank Sta=4944.5,5325
XS Rating Curve= 0 ,0
Exp/Cntr=0.3,0.1

Type RM Length L Ch R = 1 ,29201   ,1095,1095,1095
BEGIN DESCRIPTION:
TOWHEAD CREEK 52.0
END DESCRIPTION:
XS GIS Cut Line= 4
      2886086.75     10070368.25      2887019.03     10069425.55
      2886857.57     10068670.34      2887081.47     10068248.59
#Sta/Elev= 30
  3190.9 1334.34  3284.4 1331.71  3400.4 1328.32  3548.9 1326.41  3621.2 1320.66
  3690.3 1315.34  3824.6 1312.11  4035.2  1313.3  4128.4 1314.94  4347.9  1317.5
  4598.8 1315.32  4651.5  1317.1  4723.1 1315.81  4924.3 1317.39  4958.3  1315.9
  5015.1 1308.02  5017.8 1307.52  5021.1 1308.02  5040.1 1315.01  5111.7 1315.71
  5210.9 1317.17  5275.3 1320.26  5323.8 1320.61  5362.2 1323.45    5516    1327
  5554.4 1333.03    5604 1353.34    5624  1355.8  5674.2 1357.46  5766.5 1360.79
#Mann= 11 ,-1 , 0
  3190.9     .05       0  3284.4     .16       0  3621.2      .1       0
  3824.6     .05       0  4035.2      .1       0  4128.4     .05       0
  4598.8      .1       0  5015.1     .07       0  5021.1      .1       0
    5624     .16       0  5674.2      .1       0
#XS Ineff= 1 ,-1
 3354.55 4926.14 1319.71
Permanent Ineff=
       T
Bank Sta=4958.3,5111.7
XS Rating Curve= 0 ,0
Exp/Cntr=0.3,0.1

Type RM Length L Ch R = 1 ,28106   ,1490,1490,1490
BEGIN DESCRIPTION:
TOWHEAD CREEK 51.0
END DESCRIPTION:
XS GIS Cut Line= 3
      2886312.73     10070492.84      2887646.09     10069576.15
      2888166.91     10068812.29
#Sta/Elev= 30
  2893.6 1325.47  3228.2 1316.47  3378.7 1316.91  3557.9 1309.57  3614.6 1310.32
  3638.2 1310.61  3760.9 1306.85  3823.8 1312.19  3870.1 1313.53  4068.7  1314.3
  4298.7 1310.53  4439.4 1308.55  4543.7 1307.39  4683.6 1309.29  4802.2 1309.93
  4870.5 1310.87  4917.9 1309.07  4962.4 1308.37  4983.8 1305.33  4995.4    1303
  4998.1  1302.5  5001.4    1303  5010.8 1306.28  5019.3 1312.43  5034.3 1328.25
  5047.1 1339.11  5070.2 1350.91  5171.7 1354.54  5313.4 1363.29  5436.2 1366.77
#Mann= 13 ,-1 , 0
  2893.6     .16       0  3614.6      .1       0  3638.2     .16       0
  3870.1     .05       0  4439.4      .1       0  4683.6     .16       0
  4802.2      .1       0  4870.5     .16       0  4917.9      .1       0
  4983.8     .16       0  4995.4     .07       0  5001.4     .16       0
  5171.7      .1       0
#XS Ineff= 1 ,-1
 3074.43 3976.14 1314.81
Permanent Ineff=
       T
Bank Sta=4298.7,5019.3
XS Rating Curve= 0 ,0
Exp/Cntr=0.3,0.1

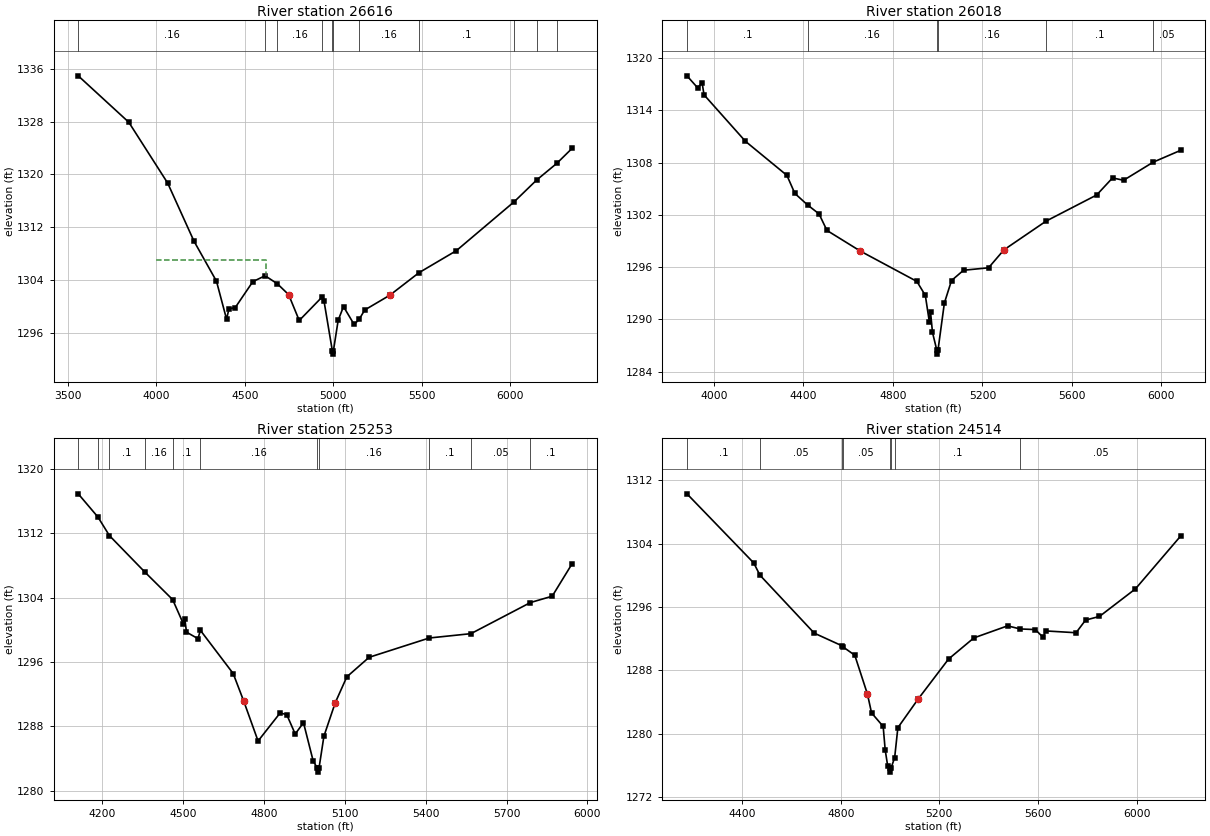
Type RM Length L Ch R = 1 ,26616   ,598,598,598
BEGIN DESCRIPTION:
TOWHEAD CREEK 50.0
END DESCRIPTION:
XS GIS Cut Line= 4
      2886944.73      10071103.9      2887646.09     10070312.26
      2888271.09     10070277.54      2888979.45     10069423.34
#Sta/Elev= 30
    3558  1334.9    3844 1327.89    4064  1318.7  4212.9 1309.92    4340 1303.88
  4396.9 1298.16  4411.1 1299.71  4446.2 1299.89  4545.8 1303.81  4615.2  1304.7
  4684.3 1303.49  4748.2 1301.85  4808.3 1297.94  4935.8 1301.44  4948.5 1300.87
  4995.6 1293.36  4998.3 1292.86  5001.6 1293.36  5028.6 1297.98  5058.7 1300.04
  5118.8 1297.34  5146.8  1298.1  5178.9 1299.53  5320.8 1301.76  5485.7 1305.16
  5697.2 1308.49  6025.6 1315.91  6151.4 1319.16  6265.5 1321.68  6351.3 1323.93
#Mann= 11 ,-1 , 0
    3558     .16       0  4615.2      .1       0  4684.3     .16       0
  4935.8      .1       0  4995.6     .07       0  5001.6      .1       0
  5146.8     .16       0  5485.7      .1       0  6025.6     .16       0
  6151.4     .05       0  6265.5     .16       0
#XS Ineff= 1 ,-1
 3999.43 4618.18 1307.15
Permanent Ineff=
       T
Bank Sta=4748.2,5320.8
XS Rating Curve= 0 ,0
Exp/Cntr=0.3,0.1

Type RM Length L Ch R = 1 ,26018   ,765,765,765
BEGIN DESCRIPTION:
TOWHEAD CREEK 48.0
END DESCRIPTION:
XS GIS Cut Line= 4
      2887565.94     10071467.19      2888295.07     10070915.14
      2888477.36     10070415.14      2888987.78     10069852.64
#Sta/Elev= 30
  3879.8 1317.96  3926.9  1316.6  3947.7 1317.12    3956 1315.78  4141.2 1310.44
  4326.4 1306.53  4361.8 1304.46  4418.5 1303.14  4469.9 1302.11  4505.3 1300.21
  4655.1 1297.83    4907 1294.36  4944.9 1292.75  4962.8 1289.72  4968.1 1290.85
  4976.8 1288.51  4995.7 1286.51  4998.5 1286.01  5001.7 1286.51    5030 1291.88
  5061.9 1294.46  5115.6 1295.64  5227.3 1295.92  5296.1 1297.98  5485.1 1301.29
  5710.5 1304.28  5781.4 1306.24  5830.8 1305.97  5963.2 1308.05  6086.1 1309.41
#Mann= 6 ,-1 , 0
  3879.8      .1       0  4418.5     .16       0  4995.7     .07       0
  5001.7     .16       0  5485.1      .1       0  5963.2     .05       0
Bank Sta=4655.1,5296.1
XS Rating Curve= 0 ,0
Exp/Cntr=0.3,0.1

Type RM Length L Ch R = 1 ,25253   ,739,739,739
BEGIN DESCRIPTION:
TOWHEAD CREEK 47.0
END DESCRIPTION:
XS GIS Cut Line= 3
      2888800.27     10071581.84      2889149.24     10070607.84
      2889253.23     10069817.48
#Sta/Elev= 30
  4110.8  1316.9    4184 1314.01  4226.6  1311.7  4358.3 1307.16  4461.2 1303.74
  4501.1 1300.71  4506.4 1301.31  4512.4  1299.7  4554.9 1298.89  4564.1 1299.92
  4685.7 1294.55  4724.9 1291.11    4778 1286.16  4859.6 1289.64  4884.2 1289.45
  4915.8 1287.03  4946.5 1288.44  4982.6 1283.66  4998.1 1282.79  5000.8 1282.29
  5004.1 1282.79  5022.3 1286.76  5064.3 1290.92  5107.3 1294.14  5189.9 1296.57
  5412.9 1298.97  5567.6 1299.51  5788.5 1303.38  5869.2 1304.17  5942.6 1308.18
#Mann= 11 ,-1 , 0
  4110.8      .1       0    4184     .05       0  4226.6      .1       0
  4358.3     .16       0  4461.2      .1       0  4564.1     .16       0
  4998.1     .07       0  5004.1     .16       0  5412.9      .1       0
  5567.6     .05       0  5788.5      .1       0
Bank Sta=4724.9,5064.3
XS Rating Curve= 0 ,0
Exp/Cntr=0.3,0.1

Type RM Length L Ch R = 1 ,24514   ,680,680,680
BEGIN DESCRIPTION:
TOWHEAD CREEK 45.0
END DESCRIPTION:
XS GIS Cut Line= 4
      2889696.11     10071758.92      2889800.28     10071264.09
       2889628.4     10070545.34      2889415.22     10069817.41
#Sta/Elev= 30
  4176.2 1310.29  4447.2 1301.56  4471.9 1300.03  4692.5  1292.7  4803.9 1291.12
    4808 1290.99    4857 1289.91  4908.5 1284.99    4925 1282.63  4972.2 1280.92
  4980.4 1277.95  4990.7  1275.9    4998 1275.65  5000.7 1275.15    5004 1275.65
  5018.8 1276.98  5031.8 1280.76  5114.1 1284.38  5237.5 1289.43  5340.3  1292.1
    5477 1293.62  5527.6 1293.23  5589.3 1293.15  5621.1 1292.17    5631 1292.98
  5754.7 1292.75  5793.4 1294.35  5849.8 1294.81  5995.7 1298.29  6179.4 1304.97
#Mann= 8 ,-1 , 0
  4176.2      .1       0  4471.9     .05       0  4803.9      .1       0
    4808     .05       0    4998    .035       0    5004     .05       0
  5018.8      .1       0  5527.6     .05       0
Bank Sta=4908.5,5114.1
XS Rating Curve= 0 ,0
Exp/Cntr=0.3,0.1