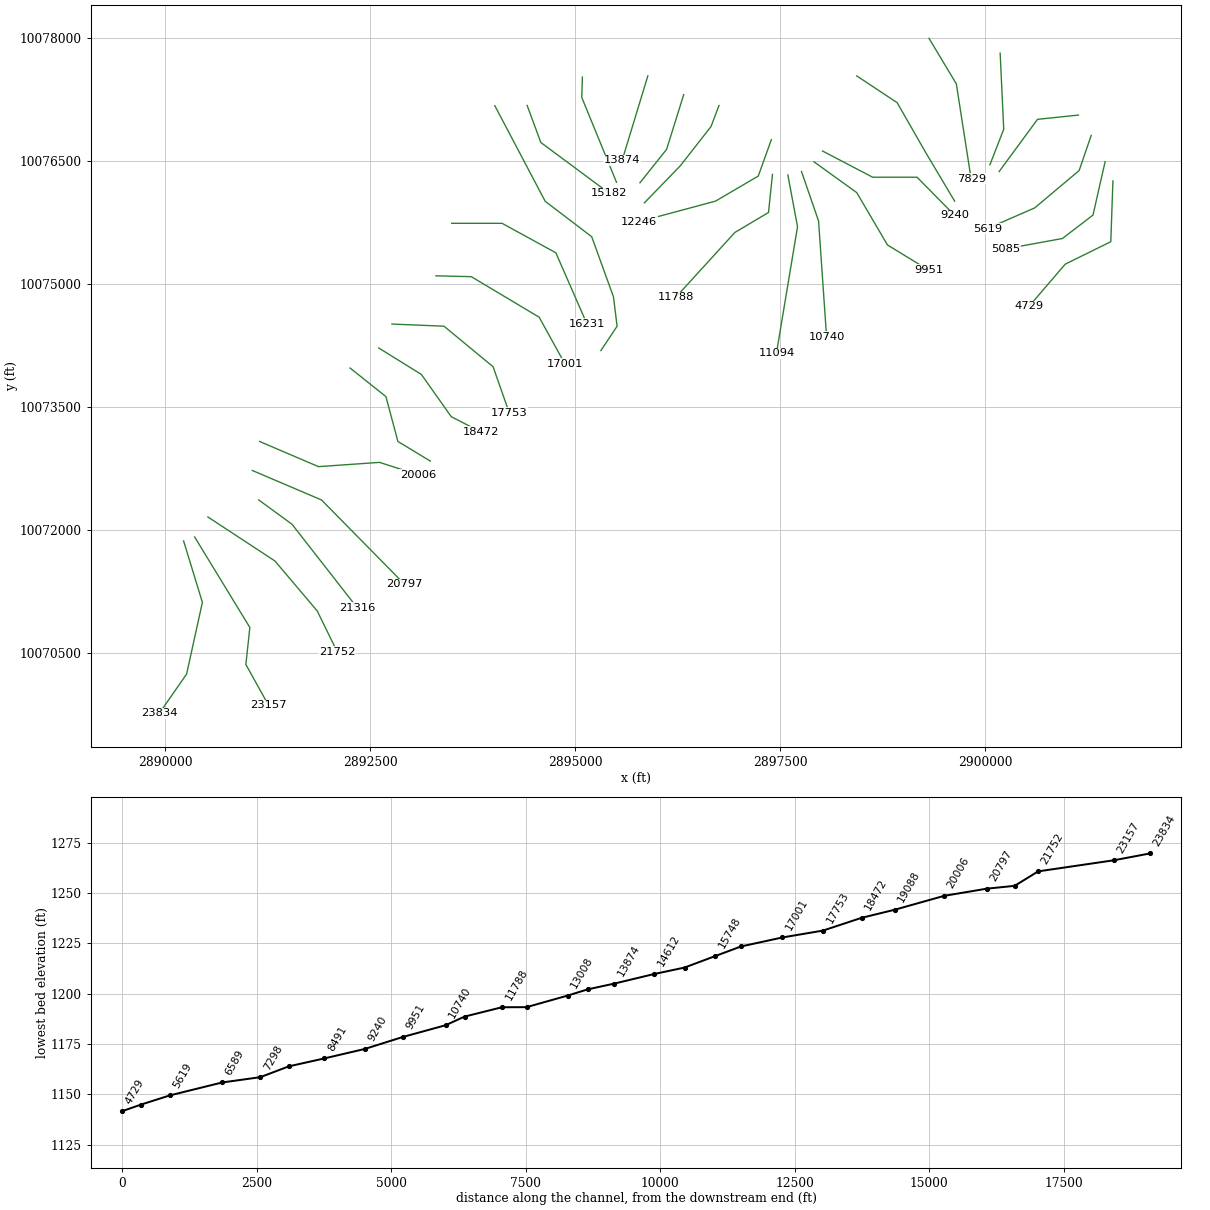
HEC-RAS study TOWHEAD CREEK.prj: TOWHEAD CREEK Base Level Engineering

--- TOWHEAD CREEK.g01 (geometry) --- (continued)

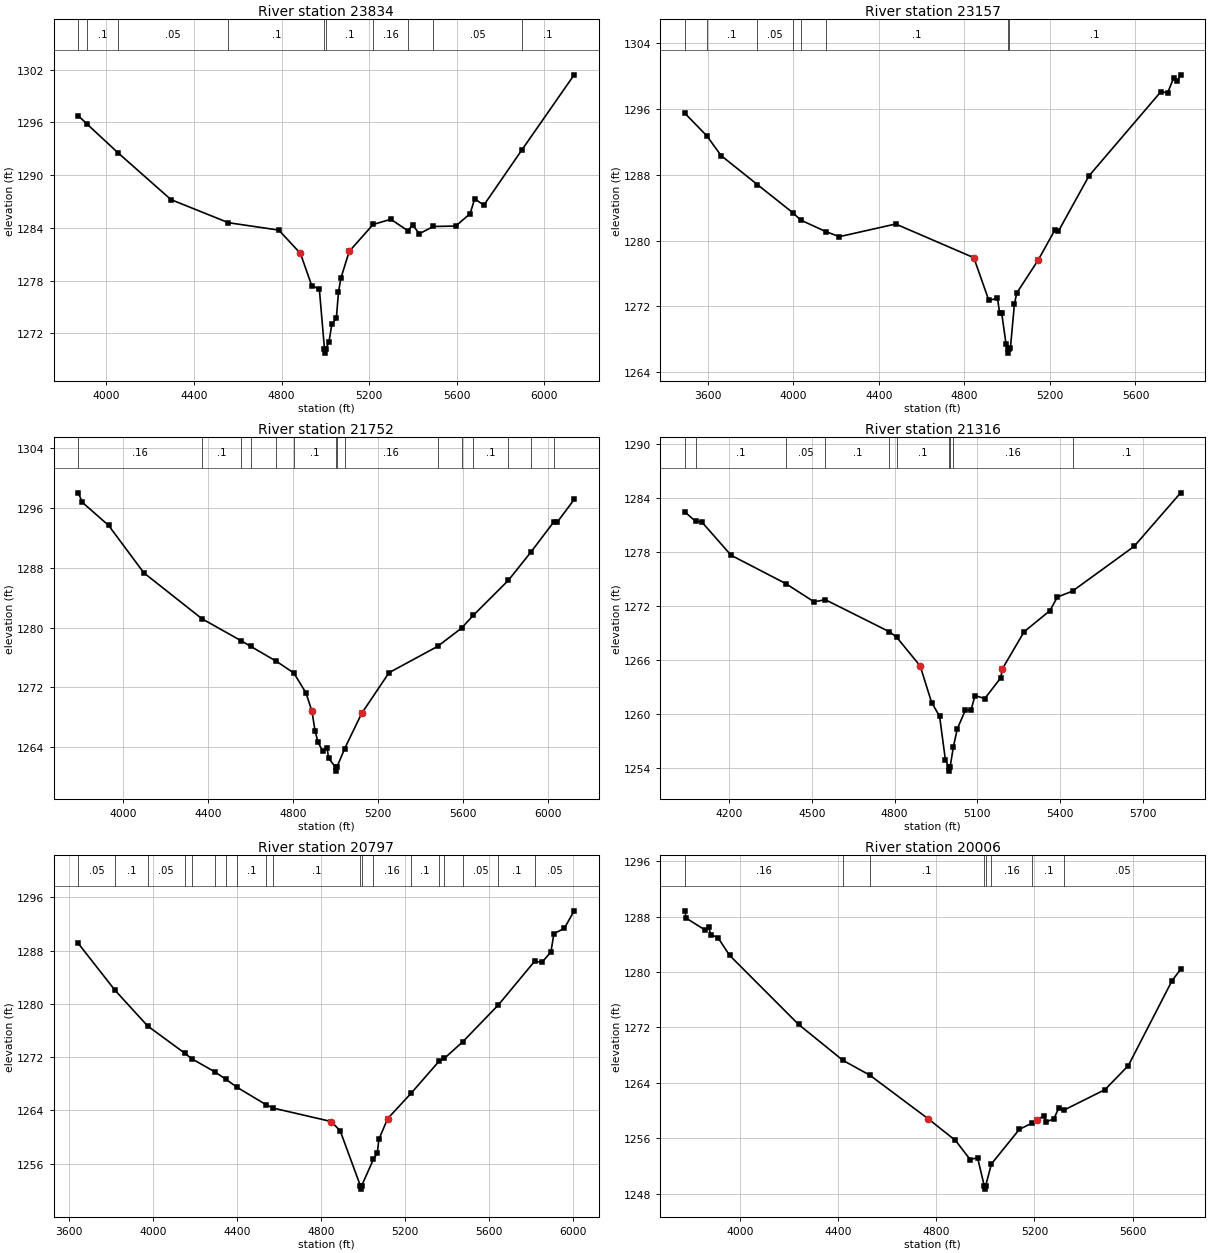
Type RM Length L Ch R = 1 ,23834   ,677,677,677
BEGIN DESCRIPTION:
TOWHEAD CREEK 43.0
END DESCRIPTION:
XS GIS Cut Line= 4
      2890222.14     10071868.29      2890451.32     10071118.26
      2890258.61     10070243.26       2889925.3     10069764.13
#Sta/Elev= 30
  3871.9 1296.76  3909.2 1295.87  4053.6 1292.53  4294.9 1287.21  4557.4 1284.58
  4787.2 1283.74  4886.1 1281.08  4937.3 1277.43  4972.4 1277.01  4995.7 1270.23
  4998.5 1269.73  5001.7 1270.23  5016.1 1270.98  5029.4 1273.01  5049.9 1273.71
  5059.8 1276.68  5070.4 1278.24  5108.7 1281.31  5217.7 1284.38  5298.9 1284.97
  5376.8 1283.66  5398.1 1284.34  5428.8 1283.33    5493 1284.15  5595.2  1284.2
  5660.7 1285.61  5681.6  1287.3  5723.5 1286.58  5897.1 1292.87  6135.8 1301.42
#Mann= 10 ,-1 , 0
  3871.9     .16       0  3909.2      .1       0  4053.6     .05       0
  4557.4      .1       0  4995.7     .07       0  5001.7      .1       0
  5217.7     .16       0  5376.8      .1       0    5493     .05       0
  5897.1      .1       0
Bank Sta=4886.1,5108.7
XS Rating Curve= 0 ,0
Exp/Cntr=0.3,0.1

Type RM Length L Ch R = 1 ,23157   ,1405,1405,1405
BEGIN DESCRIPTION:
TOWHEAD CREEK 42.0
END DESCRIPTION:
XS GIS Cut Line= 4
      2890356.89     10071916.17      2891030.49     10070812.02
      2890981.88     10070360.63      2891259.66     10069860.62
#Sta/Elev= 30
  3491.8  1295.5  3595.4 1292.73  3661.3 1290.35  3831.7 1286.81  3997.2 1283.39
  4033.9  1282.5  4151.2  1281.1    4215 1280.48  4478.2 1282.02  4843.8 1277.92
  4914.2 1272.72  4954.5    1273  4964.5 1271.19  4974.6 1271.14  4994.7 1267.36
  5001.8 1266.81  5004.5 1266.31  5007.8 1266.81  5014.8 1266.89  5033.8 1272.31
    5045 1273.64  5145.6 1277.66  5222.7 1281.28  5239.2 1281.13  5382.6 1287.88
    5719 1298.12  5750.4 1297.98  5778.4 1299.77  5794.5 1299.39  5811.2 1300.17
#Mann= 8 ,-1 , 0
  3491.8     .16       0  3595.4      .1       0  3831.7     .05       0
  3997.2      .1       0  4033.9     .05       0  4151.2      .1       0
  5001.8     .07       0  5007.8      .1       0
Bank Sta=4843.8,5145.6
XS Rating Curve= 0 ,0
Exp/Cntr=0.3,0.1

Type RM Length L Ch R = 1 ,21752   ,436,436,436
BEGIN DESCRIPTION:
TOWHEAD CREEK 40.0
END DESCRIPTION:
XS GIS Cut Line= 4
      2890519.01     10072159.94      2891336.74     10071623.47
      2891852.36     10071014.09      2892097.17     10070514.06
#Sta/Elev= 30
  3791.3 1298.02  3810.2 1296.74  3933.8 1293.66  4099.5 1287.32  4372.9 1281.18
  4555.2 1278.27  4602.8 1277.48  4723.5 1275.48  4805.5 1273.92  4862.2 1271.27
  4890.7  1268.8    4905 1266.18  4919.3 1264.67  4940.2 1263.52  4962.2 1263.85
  4968.7 1262.55  5001.7  1261.3  5004.5  1260.8  5007.7  1261.3  5044.2  1263.8
  5124.7 1268.53  5253.4 1273.97  5481.6 1277.48  5594.6 1279.93  5650.5 1281.66
  5815.2 1286.33  5922.4 1290.15  6029.7 1294.18  6044.4 1294.08  6124.3 1297.13
#Mann= 15 ,-1 , 0
  3791.3     .16       0  4372.9      .1       0  4555.2     .05       0
  4602.8      .1       0  4723.5     .05       0  4805.5      .1       0
  5001.7     .07       0  5007.7      .1       0  5044.2     .16       0
  5481.6      .1       0  5594.6     .16       0  5650.5      .1       0
  5815.2     .16       0  5922.4     .05       0  6029.7      .1       0
Bank Sta=4890.7,5124.7
XS Rating Curve= 0 ,0
Exp/Cntr=0.3,0.1

Type RM Length L Ch R = 1 ,21316   ,519,519,519
BEGIN DESCRIPTION:
TOWHEAD CREEK 39.0
END DESCRIPTION:
XS GIS Cut Line= 3
      2891138.81     10072368.27      2891545.07     10072071.39
      2892341.94     10071050.57
#Sta/Elev= 30
  4039.4 1282.48  4078.7 1281.42  4100.6 1281.37  4207.1 1277.65  4405.2  1274.5
  4508.3 1272.46    4549  1272.7  4781.3 1269.13  4807.3 1268.54    4893 1265.32
  4934.6 1261.25  4963.5 1259.71  4984.4 1254.88  4995.8 1254.11  4998.6 1253.61
  5001.8 1254.11  5013.6 1256.34  5027.8 1258.33  5056.7 1260.38  5077.5 1260.43
    5092 1262.02  5127.3 1261.69  5185.1 1263.99  5191.5 1265.02  5270.2 1269.14
  5363.3 1271.47  5390.5 1272.99  5445.7 1273.66  5668.7 1278.63  5837.6  1284.6
#Mann= 10 ,-1 , 0
  4039.4     .05       0  4078.7      .1       0  4405.2     .05       0
    4549      .1       0  4781.3     .05       0  4807.3      .1       0
  4995.8     .07       0  5001.8      .1       0  5013.6     .16       0
  5445.7      .1       0
Bank Sta=4893,5191.5
XS Rating Curve= 0 ,0
Exp/Cntr=0.3,0.1

Type RM Length L Ch R = 1 ,20797   ,791,791,791
BEGIN DESCRIPTION:
TOWHEAD CREEK 38.0
END DESCRIPTION:
XS GIS Cut Line= 3
      2891060.73     10072727.62      2891904.45     10072368.26
      2892919.19     10071337.91
#Sta/Elev= 30
  3644.2 1289.06  3818.7 1282.05  3974.3 1276.69  4151.7 1272.59  4184.6 1271.77
  4293.8 1269.81  4345.7 1268.73  4399.2 1267.51  4538.2 1264.88    4573 1264.36
  4850.1 1262.34  4892.5 1260.93  4988.5  1252.7  4991.3  1252.2  4994.5  1252.7
  5050.9 1256.69  5069.4 1257.62  5076.4 1259.66  5118.8 1262.79  5230.5 1266.59
  5363.4 1271.39  5388.3 1271.81  5475.8 1274.29    5646 1279.83  5818.6 1286.38
  5854.3 1286.24  5896.7 1287.79  5910.9 1290.54  5960.3 1291.32  6007.4 1293.96
#Mann= 19 ,-1 , 0
  3644.2     .05       0  3818.7      .1       0  3974.3     .05       0
  4151.7      .1       0  4184.6     .05       0  4293.8      .1       0
  4345.7     .05       0  4399.2      .1       0  4538.2     .05       0
    4573      .1       0  4988.5     .07       0  4994.5      .1       0
  5050.9     .16       0  5230.5      .1       0  5363.4     .05       0
  5388.3      .1       0  5475.8     .05       0    5646      .1       0
  5818.6     .05       0
Bank Sta=4850.1,5118.8
XS Rating Curve= 0 ,0
Exp/Cntr=0.3,0.1

Type RM Length L Ch R = 1 ,20006   ,918,918,918
BEGIN DESCRIPTION:
TOWHEAD CREEK 37.0
END DESCRIPTION:
XS GIS Cut Line= 4
      2891149.21     10073081.82      2891867.99     10072774.51
      2892612.78     10072826.59      2893081.52     10072675.56
#Sta/Elev= 30
  3774.8 1288.85    3781 1287.78  3857.3 1286.08  3871.9 1286.49  3880.9  1285.4
  3909.9 1284.98  3957.1 1282.43  4238.4 1272.44  4419.4 1267.24  4528.7 1265.11
  4767.5 1258.78  4877.8 1255.68  4937.9 1252.91    4968 1253.18  4995.1 1249.14
  4997.8 1248.64  5001.1 1249.14  5024.5 1252.28  5138.4 1257.28  5191.2  1258.2
  5208.6 1258.69  5238.7 1259.19  5248.7 1258.37  5278.8 1258.79  5298.5 1260.32
  5321.5 1260.08  5487.1 1263.01  5582.3 1266.48  5760.9 1278.77  5795.6 1280.39
#Mann= 8 ,-1 , 0
  3774.8     .16       0  4419.4     .05       0  4528.7      .1       0
  4995.1     .07       0  5001.1      .1       0  5024.5     .16       0
  5191.2      .1       0  5321.5     .05       0
Bank Sta=4767.5,5208.6
XS Rating Curve= 0 ,0
Exp/Cntr=0.3,0.1

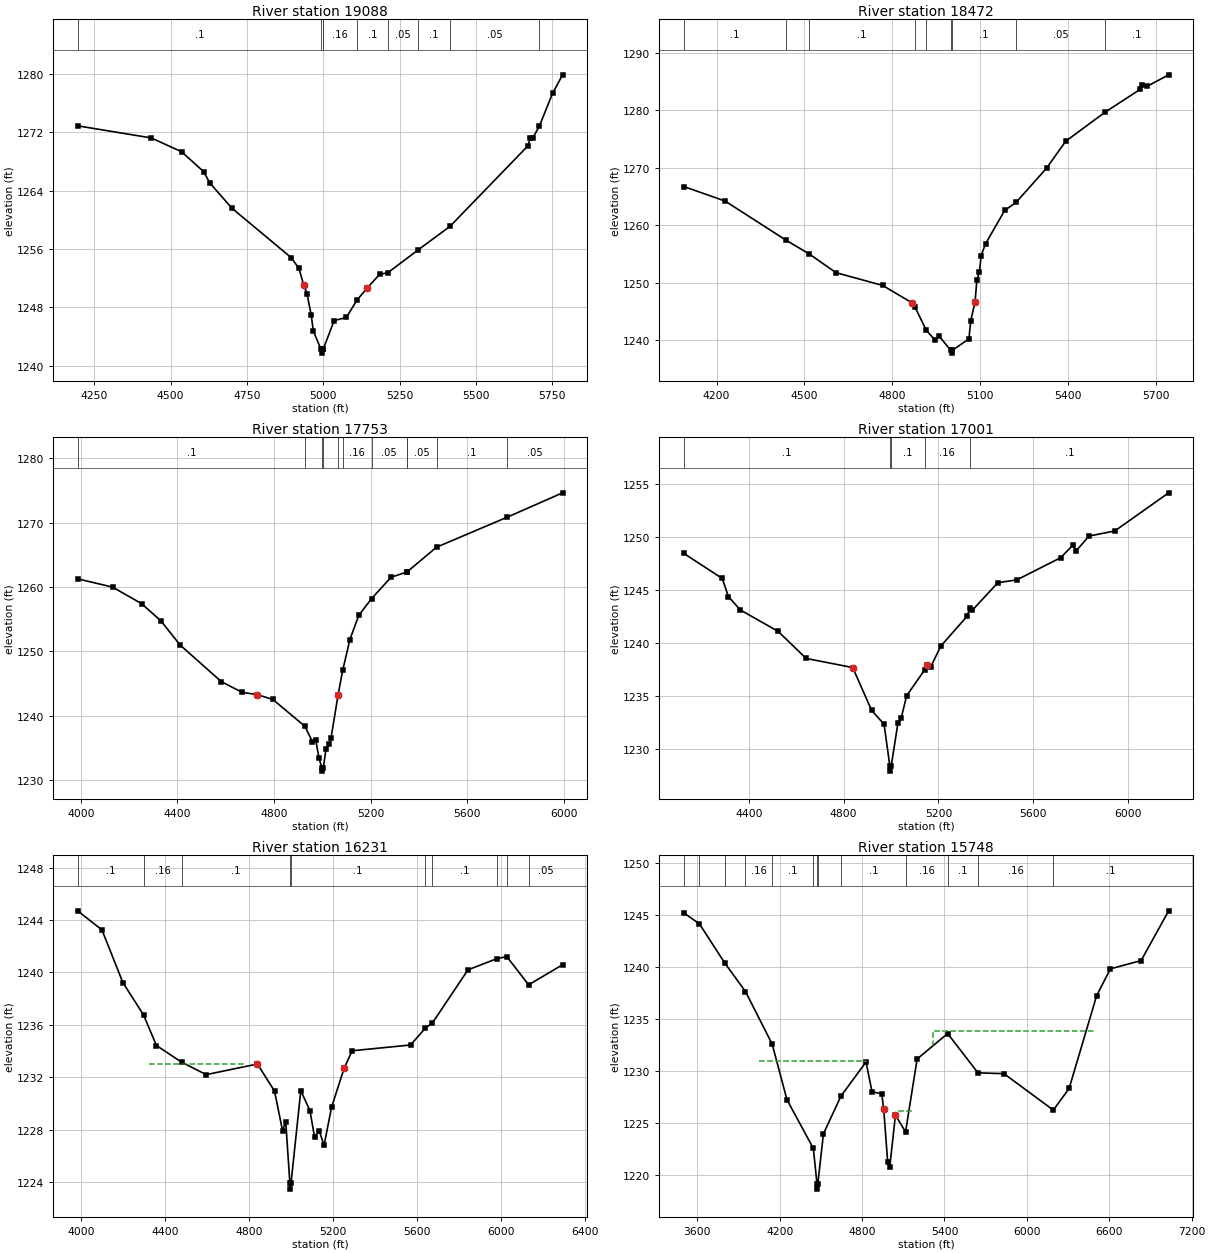
Type RM Length L Ch R = 1 ,19088   ,616,616,616
BEGIN DESCRIPTION:
TOWHEAD CREEK 34.0
END DESCRIPTION:
XS GIS Cut Line= 4
      2892253.44     10073977.61       2892690.9     10073628.68
      2892836.74      10073081.8      2893232.61      10072842.2
#Sta/Elev= 30
  4195.4  1272.9  4436.3 1271.24  4535.6 1269.35  4607.7 1266.63  4628.5 1265.05
  4700.5 1261.61  4894.6 1254.84  4920.3 1253.35    4936 1251.04  4946.4 1249.91
  4960.4 1246.94  4967.1  1244.8  4992.4 1242.24  4995.1 1241.74  4998.4 1242.24
  4999.4 1242.25  5035.5  1246.2  5075.6 1246.63  5110.2 1249.01    5143 1250.63
  5184.4 1252.54  5210.9 1252.75  5311.5 1255.92    5415 1259.12  5671.2  1270.2
    5677 1271.23  5685.3 1271.18  5707.1 1272.81  5750.7 1277.34  5783.7 1279.89
#Mann= 9 ,-1 , 0
  4195.4      .1       0  4992.4     .07       0  4998.4      .1       0
  4999.4     .16       0  5110.2      .1       0  5210.9     .05       0
  5311.5      .1       0    5415     .05       0  5707.1      .1       0
Bank Sta=4936,5143
XS Rating Curve= 0 ,0
Exp/Cntr=0.3,0.1

Type RM Length L Ch R = 1 ,18472   ,719,719,719
BEGIN DESCRIPTION:
TOWHEAD CREEK 32.0
END DESCRIPTION:
XS GIS Cut Line= 4
      2892602.38     10074222.42       2893123.2     10073899.51
      2893487.78     10073383.89      2893852.39     10073196.37
#Sta/Elev= 30
  4088.1 1266.72  4229.3 1264.19  4437.9 1257.35  4515.2 1255.02  4607.3 1251.73
  4766.9  1249.5  4867.2 1246.47  4876.3 1245.81  4915.7 1241.69  4945.3    1240
  4960.1 1240.63  4998.9 1238.22  5001.7 1237.72  5004.9 1238.22  5061.1 1240.21
  5067.2 1243.34    5082 1246.67  5088.1  1250.4  5096.8 1251.88  5102.9 1254.71
  5117.7 1256.75  5182.9 1262.55  5221.6 1263.94  5325.7  1269.9  5391.2  1274.6
  5525.3 1279.65  5646.1 1283.66  5651.7 1284.43  5668.3 1284.14  5742.4 1286.16
#Mann= 9 ,-1 , 0
  4088.1      .1       0  4437.9     .05       0  4515.2      .1       0
  4876.3     .05       0  4915.7      .1       0  4998.9     .07       0
  5004.9      .1       0  5221.6     .05       0  5525.3      .1       0
Bank Sta=4867.2,5082
XS Rating Curve= 0 ,0
Exp/Cntr=0.3,0.1

Type RM Length L Ch R = 1 ,17753   ,752,752,752
BEGIN DESCRIPTION:
TOWHEAD CREEK 31.0
END DESCRIPTION:
XS GIS Cut Line= 4
      2892763.81      10074514.1      2893399.24     10074488.05
       2893998.2     10073993.26      2894196.12     10073430.73
#Sta/Elev= 30
  3986.5 1261.27  4131.3 1259.98  4251.4 1257.41  4331.4 1254.73  4411.5 1250.96
  4581.7 1245.28  4667.7 1243.62  4731.5 1243.25  4795.3 1242.51  4928.4 1238.32
  4958.7 1235.96  4972.5 1236.27  4986.8 1233.34  4998.2 1231.86  5000.9 1231.36
  5004.2 1231.86  5015.5  1234.8  5029.8 1235.53  5036.5 1236.55  5065.5 1243.23
  5084.7 1247.06  5114.5 1251.83    5151 1255.58  5204.1 1258.19  5285.2 1261.52
  5350.1 1262.32  5350.9 1262.34  5473.3 1266.19  5766.9 1270.87  5995.7 1274.65
#Mann= 11 ,-1 , 0
  3986.5      .1       0  4928.4     .16       0  4998.2     .07       0
  5004.2     .16       0  5065.5     .05       0  5084.7     .16       0
  5204.1     .05       0  5350.1     .16       0  5350.9     .05       0
  5473.3      .1       0  5766.9     .05       0
Bank Sta=4731.5,5065.5
XS Rating Curve= 0 ,0
Exp/Cntr=0.3,0.1

Type RM Length L Ch R = 1 ,17001   ,770,770,770
BEGIN DESCRIPTION:
TOWHEAD CREEK 29.0
END DESCRIPTION:
XS GIS Cut Line= 4
      2893300.23     10075102.64      2893732.57     10075092.22
       2894560.7     10074597.43      2894873.21      10074029.7
#Sta/Elev= 30
  4125.7  1248.5  4288.4 1246.13    4314 1244.43    4364 1243.17    4524 1241.14
  4641.9 1238.59  4838.4 1237.73  4918.1 1233.69  4970.7 1232.38  4994.9 1228.46
  4997.6 1227.96  5000.9 1228.46    5029 1232.47  5042.6 1232.94  5065.9 1235.07
  5141.4  1237.5  5151.6 1237.99  5167.2 1237.77    5210 1239.76  5320.9 1242.57
  5332.9 1243.38  5342.3 1243.12  5450.4 1245.73  5530.7    1246  5715.3 1248.09
  5766.8 1249.27  5780.7 1248.73  5834.6 1250.13  5943.5 1250.61  6170.9 1254.21
#Mann= 5 ,-1 , 0
  4125.7      .1       0  4994.9     .07       0  5000.9      .1       0
  5141.4     .16       0  5332.9      .1       0
Bank Sta=4838.4,5151.6
XS Rating Curve= 0 ,0
Exp/Cntr=0.3,0.1

Type RM Length L Ch R = 1 ,16231   ,483,483,483
BEGIN DESCRIPTION:
TOWHEAD CREEK 27.0
END DESCRIPTION:
XS GIS Cut Line= 4
      2893492.96     10075743.26      2894107.57     10075743.26
      2894763.82     10075383.89      2895143.76     10074514.71
#Sta/Elev= 30
  3982.8  1244.7  4098.3 1243.25  4198.3 1239.23  4296.9 1236.76  4358.3 1234.43
  4479.4 1233.15  4595.4 1232.21  4839.7 1233.02  4921.2 1230.95  4959.2 1227.95
  4974.7 1228.59  4994.1 1223.98  4996.8 1223.48  5000.1 1223.98  5046.4 1230.99
    5090 1229.46  5111.8 1227.46  5134.3 1227.93  5157.1 1226.81  5193.4 1229.75
  5253.1  1232.7    5291 1234.03  5569.5 1234.47  5640.2 1235.76  5673.7 1236.15
  5843.2  1240.2  5980.2 1241.05  6028.2 1241.21  6132.3 1239.06  6294.2 1240.59
#Mann= 10 ,-1 , 0
  3982.8      .1       0  4296.9     .16       0  4479.4      .1       0
  4994.1     .07       0  5000.1      .1       0  5640.2     .05       0
  5673.7      .1       0  5980.2     .05       0  6028.2      .1       0
  6132.3     .05       0
#XS Ineff= 1 ,-1
 4321.59  4773.3 1233.05
Permanent Ineff=
       T
Bank Sta=4839.7,5253.1
XS Rating Curve= 0 ,0
Exp/Cntr=0.3,0.1

Type RM Length L Ch R = 1 ,15748   ,566,566,566
BEGIN DESCRIPTION:
TOWHEAD CREEK 26.0
END DESCRIPTION:
XS GIS Cut Line= 6
      2894019.24     10077178.58      2894633.83     10076011.91
      2895201.54     10075579.62      2895467.16     10074845.24
       2895511.1     10074487.07      2895313.31     10074190.37
#Sta/Elev= 30
  3501.4 1245.21  3615.6 1244.15  3800.1 1240.39  3950.9 1237.65  4145.7 1232.59
  4252.9 1227.26  4445.3 1222.58  4471.6 1219.17  4474.4 1218.67  4477.6 1219.17
  4518.7 1223.99  4646.8 1227.62  4828.7 1230.88  4872.3 1228.02  4943.1 1227.83
  4957.6 1226.32  4986.7 1221.24  5001.2 1220.76  5042.9 1225.79  5116.4 1224.16
  5200.8 1231.17  5422.8 1233.61  5643.7 1229.84  5832.8 1229.76  6192.5 1226.26
  6307.3 1228.34  6507.5 1237.24  6607.9 1239.83  6831.5 1240.62    7032  1245.4
#Mann= 13 ,-1 , 0
  3501.4      .1       0  3615.6     .05       0  3800.1      .1       0
  3950.9     .16       0  4145.7      .1       0  4445.3     .16       0
  4471.6     .07       0  4477.6     .16       0  4646.8      .1       0
  5116.4     .16       0  5422.8      .1       0  5643.7     .16       0
  6192.5      .1       0
#XS Ineff= 3 ,-1
  4049.3 4828.45 1230.94 5056.62 5169.86 1226.13 5318.18 6490.91 1233.84
Permanent Ineff=
       T       T       T
Bank Sta=4957.6,5042.9
XS Rating Curve= 0 ,0
Exp/Cntr=0.3,0.1

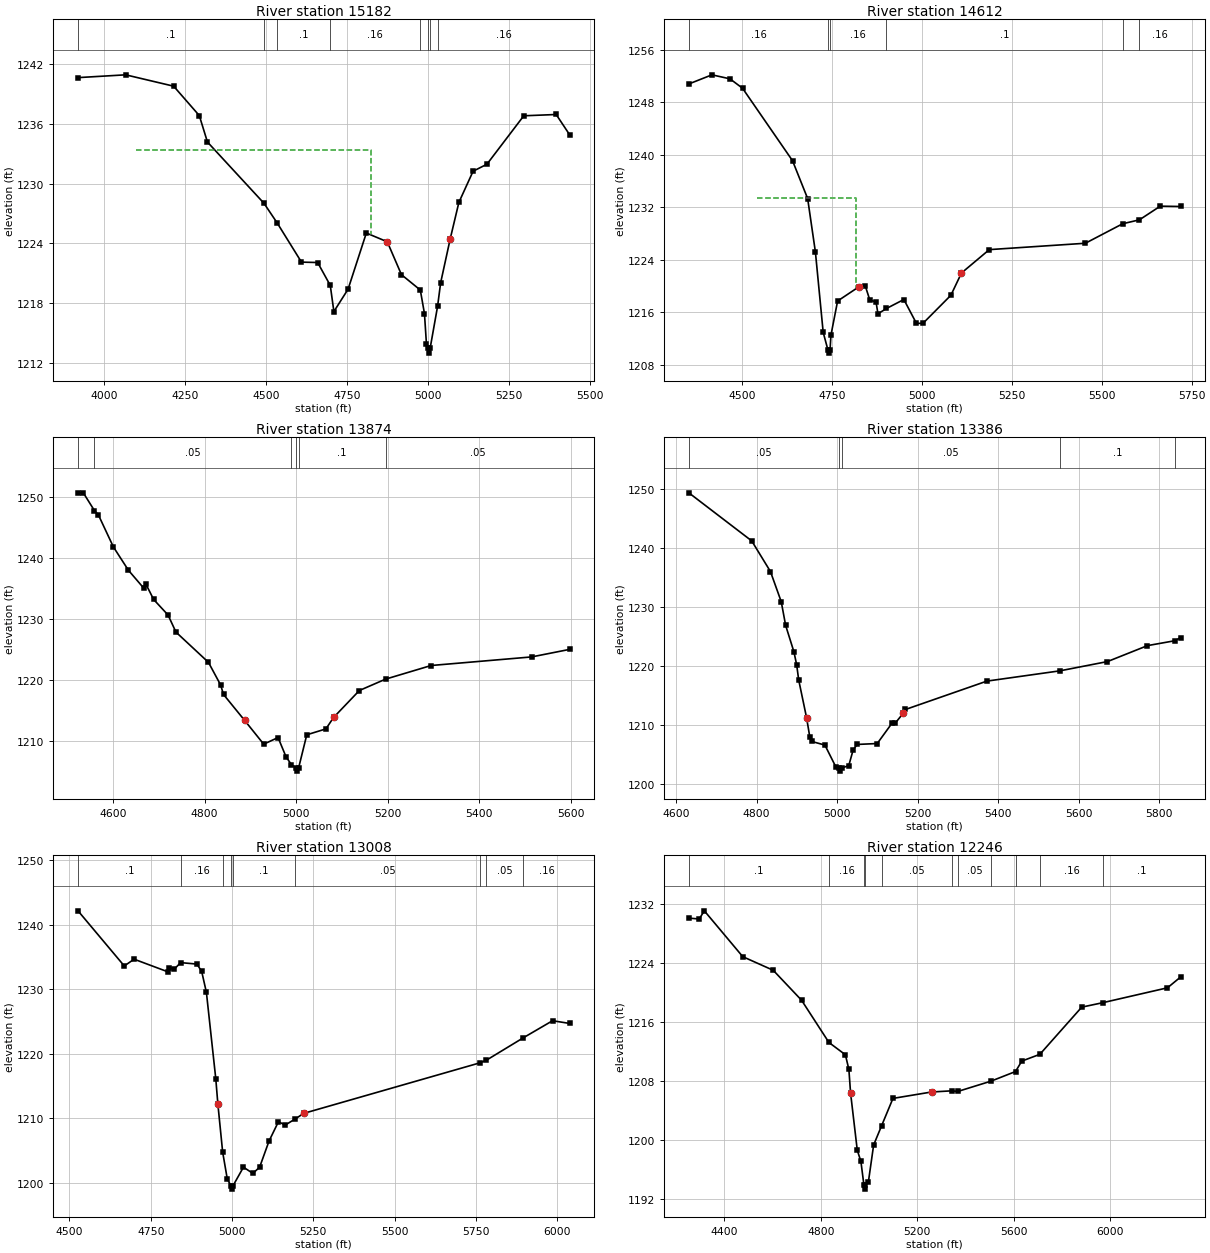
Type RM Length L Ch R = 1 ,15182   ,570,570,570
BEGIN DESCRIPTION:
TOWHEAD CREEK 25.0
END DESCRIPTION:
XS GIS Cut Line= 3
      2894413.98      10077180.8      2894580.66     10076729.37
      2895413.73     10076111.52
#Sta/Elev= 30
  3920.2 1240.63  4067.4 1240.91  4215.6 1239.77  4294.8 1236.82  4319.9 1234.17
  4494.6 1228.02  4535.5 1226.04  4610.3 1222.12  4660.3 1222.08  4699.3 1219.78
  4710.4 1217.16  4754.3 1219.41  4810.6 1225.04  4875.3 1224.16  4919.1 1220.86
  4977.3 1219.32  4990.1 1216.96  4996.3 1213.88  5001.7 1213.49  5004.4 1212.99
  5007.7 1213.49  5030.6 1217.68  5040.1 1220.05  5069.4 1224.42  5096.4 1228.11
  5140.3 1231.24    5183 1231.94  5296.8  1236.8  5396.9 1236.93  5438.6 1234.89
#Mann= 8 ,-1 , 0
  3920.2      .1       0  4494.6     .16       0  4535.5      .1       0
  4699.3     .16       0  4977.3      .1       0  5001.7     .07       0
  5007.7      .1       0  5030.6     .16       0
#XS Ineff= 1 ,-1
 4100.68  4825.8 1233.35
Permanent Ineff=
       T
Bank Sta=4875.3,5069.4
XS Rating Curve= 0 ,0
Exp/Cntr=0.3,0.1

Type RM Length L Ch R = 1 ,14612   ,738,738,738
BEGIN DESCRIPTION:
TOWHEAD CREEK 24.0
END DESCRIPTION:
XS GIS Cut Line= 3
      2895087.61     10077527.94      2895080.66     10077277.98
      2895503.88     10076244.21
#Sta/Elev= 30
  4352.1 1250.76  4416.3 1252.15  4466.4 1251.54  4501.3 1250.11  4640.3 1239.07
  4682.4  1233.3    4704 1225.14  4725.6 1212.92  4738.7 1210.25  4741.4 1209.75
  4744.7 1210.25  4747.2  1212.5  4765.7 1217.69  4824.5 1219.84  4843.1 1219.91
  4855.3 1217.83  4872.5 1217.55  4877.9 1215.74  4901.5 1216.55  4949.9 1217.92
  4984.9 1214.28  5003.3  1214.3  5080.7 1218.57  5110.1 1221.96  5187.5 1225.52
  5454.6 1226.49  5558.3 1229.46  5604.9 1230.06  5662.8 1232.14  5719.2 1232.09
#Mann= 6 ,-1 , 0
  4352.1     .16       0  4738.7     .07       0  4744.7     .16       0
  4901.5      .1       0  5558.3     .05       0  5604.9     .16       0
#XS Ineff= 1 ,-1
 4540.91 4818.18 1233.42
Permanent Ineff=
       T
Bank Sta=4824.5,5110.1
XS Rating Curve= 0 ,0
Exp/Cntr=0.3,0.1

Type RM Length L Ch R = 1 ,13874   ,488,488,488
BEGIN DESCRIPTION:
TOWHEAD CREEK 23.0
END DESCRIPTION:
XS GIS Cut Line= 2
      2895886.22     10077541.88      2895573.73     10076514.14
#Sta/Elev= 30
  4523.6 1250.72  4535.2 1250.75  4559.6 1247.82  4568.1 1247.13  4600.9 1241.86
  4633.8 1238.02  4666.7 1235.13  4671.9 1235.75  4688.9 1233.22  4720.3 1230.67
  4737.6 1227.86  4808.6 1222.89  4835.2 1219.17  4841.5 1217.61  4887.5 1213.36
  4929.3 1209.44  4960.7 1210.53  4978.1 1207.36  4989.9 1206.08  4999.5 1205.51
  5002.2 1205.01  5005.5 1205.51  5023.4 1210.98  5065.2 1211.95    5082 1213.83
  5138.3 1218.26  5195.6 1220.13  5295.1 1222.37  5514.6 1223.78  5597.8 1225.02
#Mann= 6 ,-1 , 0
  4523.6      .1       0  4559.6     .05       0  4989.9      .1       0
  4999.5     .07       0  5005.5      .1       0  5195.6     .05       0
Bank Sta=4887.5,5082
XS Rating Curve= 0 ,0
Exp/Cntr=0.3,0.1

Type RM Length L Ch R = 1 ,13386   ,378,378,378
BEGIN DESCRIPTION:
TOWHEAD CREEK 22.0
END DESCRIPTION:
XS GIS Cut Line= 3
      2896323.72     10077312.71      2896115.38     10076646.04
      2895789.93     10076237.49
#Sta/Elev= 30
    4632  1249.3  4788.1 1241.16  4834.6 1235.97  4861.4 1230.86  4872.3 1226.86
  4892.9 1222.37  4899.6 1220.21  4904.8 1217.59  4924.3 1211.22  4932.1 1208.04
  4937.3  1207.2  4969.8 1206.59    4997 1202.89  5005.1 1202.68  5007.8 1202.18
  5011.1 1202.68  5029.1 1203.13    5040 1205.79    5050  1206.7  5099.7 1206.85
  5137.4 1210.39  5144.3  1210.3  5164.6    1212  5169.9 1212.62  5371.9 1217.42
  5553.3 1219.16  5671.4 1220.73  5770.7 1223.43  5838.8 1224.26  5852.8 1224.79
#Mann= 5 ,-1 , 0
    4632     .05       0  5005.1    .035       0  5011.1     .05       0
  5553.3      .1       0  5838.8     .16       0
Bank Sta=4924.3,5164.6
XS Rating Curve= 0 ,0
Exp/Cntr=0.3,0.1

Type RM Length L Ch R = 1 ,13008   ,762,762,762
BEGIN DESCRIPTION:
TOWHEAD CREEK 21.0
END DESCRIPTION:
XS GIS Cut Line= 4
      2896754.27     10077180.74      2896657.05     10076923.82
      2896282.05     10076444.65      2895844.54     10075993.25
#Sta/Elev= 30
  4526.3 1242.16  4668.6 1233.62  4698.8 1234.67  4803.9 1232.69  4807.1 1233.38
  4821.6 1233.09  4841.9 1234.14  4892.1 1233.91  4906.6 1232.77  4921.1 1229.53
    4950 1216.12  4956.3 1212.26  4971.1 1204.79  4985.3 1200.63  4996.7 1199.56
  4999.5 1199.06  5002.7 1199.56    5035 1202.46  5063.9  1201.5  5084.7 1202.45
  5113.7 1206.51  5142.6  1209.5  5163.4 1208.98  5193.9 1209.92  5220.2 1210.79
  5761.5 1218.61  5781.8 1219.02  5895.6  1222.5  5985.4 1225.14  6038.1 1224.72
#Mann= 9 ,-1 , 0
  4526.3      .1       0  4841.9     .16       0  4971.1      .1       0
  4996.7     .07       0  5002.7      .1       0  5193.9     .05       0
  5761.5      .1       0  5781.8     .05       0  5895.6     .16       0
Bank Sta=4956.3,5220.2
XS Rating Curve= 0 ,0
Exp/Cntr=0.3,0.1

Type RM Length L Ch R = 1 ,12246   ,458,458,458
BEGIN DESCRIPTION:
TOWHEAD CREEK 20.0
END DESCRIPTION:
XS GIS Cut Line= 4
      2897393.17     10076764.12      2897233.44     10076319.65
      2896712.61     10076014.09      2895782.73     10075764.28
#Sta/Elev= 30
  4252.7 1230.14  4295.6 1230.02  4316.9 1231.13  4476.3  1224.9  4602.6 1223.05
  4720.1 1218.98  4833.6 1213.24  4901.8 1211.57  4916.3 1209.58  4923.3 1206.38
  4951.1  1198.6  4966.2 1197.07  4978.9 1193.81  4981.6 1193.31  4984.9 1193.81
  4997.4 1194.33    5019 1199.31  5052.1 1201.93  5099.1 1205.64  5259.3 1206.51
    5344 1206.67  5367.6 1206.58  5506.3 1207.99  5607.3 1209.29  5633.4 1210.71
  5708.3 1211.63  5881.9 1218.04  5969.7 1218.65  6237.6 1220.67  6291.7 1222.13
#Mann= 11 ,-1 , 0
  4252.7      .1       0  4833.6     .16       0  4978.9     .07       0
  4984.9     .16       0  5052.1     .05       0    5344     .16       0
  5367.6     .05       0  5506.3      .1       0  5607.3     .05       0
  5708.3     .16       0  5969.7      .1       0
Bank Sta=4923.3,5259.3
XS Rating Curve= 0 ,0
Exp/Cntr=0.3,0.1

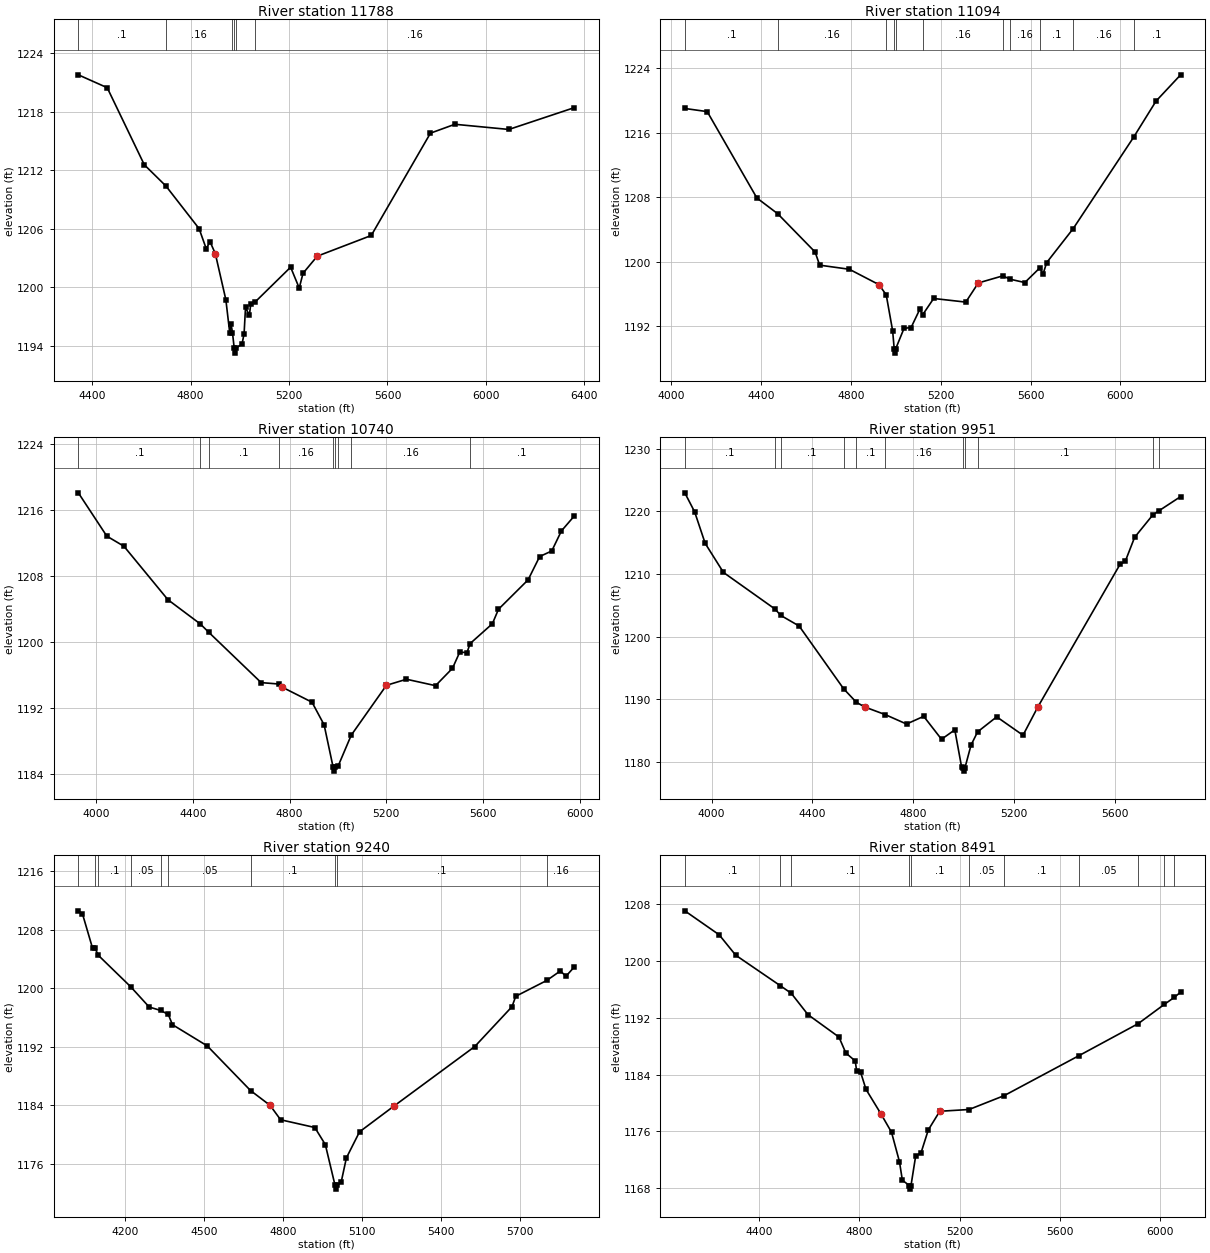
Type RM Length L Ch R = 1 ,11788   ,694,694,694
BEGIN DESCRIPTION:
TOWHEAD CREEK 19.0
END DESCRIPTION:
XS GIS Cut Line= 4
      2897407.05     10076340.49      2897358.44     10075875.21
      2896948.72     10075632.15      2896226.51     10074840.49
#Sta/Elev= 30
  4343.3 1221.79  4460.7 1220.47  4611.5 1212.57  4699.5 1210.39  4834.3 1206.02
  4863.2 1203.97  4878.8 1204.68  4900.2 1203.46  4943.1 1198.73  4958.7 1195.37
  4964.5  1196.2    4970 1195.35  4977.1 1193.76  4979.9 1193.26  4983.1 1193.76
  5008.7 1194.18  5017.2 1195.25    5023 1197.95  5038.6 1197.13  5044.4  1198.3
  5061.9  1198.5  5206.4 1202.07  5241.3 1199.93  5256.9 1201.45  5314.7  1203.2
  5534.2 1205.32  5774.8 1215.81  5874.1 1216.72  6093.6 1216.19  6359.1 1218.42
#Mann= 6 ,-1 , 0
  4343.3      .1       0  4699.5     .16       0    4970      .1       0
  4977.1     .07       0  4983.1      .1       0  5061.9     .16       0
Bank Sta=4900.2,5314.7
XS Rating Curve= 0 ,0
Exp/Cntr=0.3,0.1

Type RM Length L Ch R = 1 ,11094   ,354,354,354
BEGIN DESCRIPTION:
TOWHEAD CREEK 18.0
END DESCRIPTION:
XS GIS Cut Line= 3
      2897594.55     10076333.56      2897712.61     10075701.59
      2897455.67     10074159.95
#Sta/Elev= 30
  4061.9 1219.02  4161.6 1218.63  4382.5  1207.9  4475.2 1205.94  4641.6 1201.18
  4661.9 1199.55  4793.9 1199.04  4925.7 1197.13    4958 1195.86  4986.5  1191.4
  4993.6 1189.12  4996.4 1188.62  4999.6 1189.12  5037.2  1191.7  5068.6  1191.8
  5108.1 1194.11  5119.6 1193.37    5169 1195.41  5311.9 1194.96  5367.7 1197.34
  5476.4 1198.22  5509.8  1197.8  5574.5 1197.39  5641.3 1199.21  5655.6 1198.43
  5671.8 1199.87    5790  1204.1  6059.3 1215.48  6158.4 1219.94  6267.7  1223.2
#Mann= 11 ,-1 , 0
  4061.9      .1       0  4475.2     .16       0    4958      .1       0
  4993.6     .07       0  4999.6      .1       0  5119.6     .16       0
  5476.4      .1       0  5509.8     .16       0  5641.3      .1       0
    5790     .16       0  6059.3      .1       0
Bank Sta=4925.7,5367.7
XS Rating Curve= 0 ,0
Exp/Cntr=0.3,0.1

Type RM Length L Ch R = 1 ,10740   ,789,789,789
BEGIN DESCRIPTION:
TOWHEAD CREEK 17.0
END DESCRIPTION:
XS GIS Cut Line= 3
      2897761.21     10076375.22      2897969.55     10075771.04
      2898066.78     10074361.28
#Sta/Elev= 30
  3925.4 1218.11  4043.3 1212.85  4114.2 1211.62  4296.2 1205.13    4430 1202.19
  4464.6 1201.19  4682.1 1195.06  4754.9 1194.89    4767 1194.54  4892.6 1192.68
  4942.7 1189.93  4979.8 1184.81  4982.5 1184.31  4985.8 1184.81  5000.6 1184.92
    5055 1188.68  5200.5 1194.73  5283.5 1195.47  5403.8 1194.69    5474  1196.8
    5504 1198.76  5534.1 1198.71  5546.9  1199.8  5639.1 1202.21  5664.4 1203.97
  5786.9 1207.54  5834.8 1210.37  5884.9 1211.05  5924.8 1213.48  5977.6 1215.28
#Mann= 9 ,-1 , 0
  3925.4      .1       0    4430     .16       0  4464.6      .1       0
  4754.9     .16       0  4979.8     .07       0  4985.8     .16       0
  5000.6      .1       0    5055     .16       0  5546.9      .1       0
Bank Sta=4767,5200.5
XS Rating Curve= 0 ,0
Exp/Cntr=0.3,0.1

Type RM Length L Ch R = 1 ,9951    ,711,711,711
BEGIN DESCRIPTION:
TOWHEAD CREEK 16.0
END DESCRIPTION:
XS GIS Cut Line= 4
        2897914.     10076493.26      2898434.83     10076118.26
      2898809.83     10075479.37      2899309.85      10075173.8
#Sta/Elev= 30
  3893.3 1222.96  3932.4 1219.92  3974.2 1214.89  4046.7 1210.25  4252.2 1204.38
  4273.7  1203.4  4347.3 1201.69  4523.9 1191.67  4574.6 1189.51  4607.8 1188.76
  4688.9 1187.55  4773.7 1186.04  4841.8 1187.27  4912.5 1183.61  4965.3 1185.11
  4992.6 1179.11  4999.4 1179.02  5002.2 1178.52  5005.4 1179.02  5029.7 1182.67
  5055.8 1184.79  5131.7 1187.19  5236.1 1184.25  5294.1  1188.7  5621.2 1211.53
  5642.5 1212.06  5679.2 1215.85  5751.2 1219.42  5777.2 1220.13  5861.9 1222.36
#Mann= 11 ,-1 , 0
  3893.3      .1       0  4252.2     .05       0  4273.7      .1       0
  4523.9     .05       0  4574.6      .1       0  4688.9     .16       0
  4999.4     .07       0  5005.4     .16       0  5055.8      .1       0
  5751.2     .16       0  5777.2     .05       0
Bank Sta=4607.8,5294.1
XS Rating Curve= 0 ,0
Exp/Cntr=0.3,0.1

Type RM Length L Ch R = 1 ,9240    ,749,749,749
BEGIN DESCRIPTION:
TOWHEAD CREEK 15.0
END DESCRIPTION:
XS GIS Cut Line= 4
      2898018.17      10076625.2      2898629.27     10076305.76
      2899170.94     10076305.76      2899629.25     10075840.51
#Sta/Elev= 30
  4021.2  1210.6  4036.8  1210.2  4075.3 1205.48  4084.4 1205.51    4097 1204.52
  4220.3 1200.21  4290.5 1197.44  4334.1 1196.97    4363 1196.43  4378.8 1195.03
  4511.2 1192.12  4675.8 1186.01  4749.9 1183.99  4789.9 1182.02  4919.9 1180.96
  4959.9 1178.62  4996.9 1173.03  4999.7 1172.53  5002.9 1173.03  5019.9 1173.46
  5039.9  1176.8  5089.9 1180.37  5219.9 1183.87  5527.9 1192.04  5669.3 1197.49
  5683.5 1198.91  5801.2 1201.07  5853.2 1202.38  5874.3 1201.65  5905.5  1202.9
#Mann= 10 ,-1 , 0
  4021.2      .1       0  4084.4     .05       0    4097      .1       0
  4220.3     .05       0  4334.1      .1       0    4363     .05       0
  4675.8      .1       0  4996.9     .07       0  5002.9      .1       0
  5801.2     .16       0
Bank Sta=4749.9,5219.9
XS Rating Curve= 0 ,0
Exp/Cntr=0.3,0.1

Type RM Length L Ch R = 1 ,8491    ,662,662,662
BEGIN DESCRIPTION:
TOWHEAD CREEK 14.0
END DESCRIPTION:
XS GIS Cut Line= 4
      2898434.86     10077541.85      2898927.88     10077215.48
      2899282.05     10076597.43       2899629.3     10076014.05
#Sta/Elev= 30
  4101.5  1207.1  4238.9 1203.72  4305.1 1200.84  4482.6 1196.56  4527.1 1195.47
  4593.9 1192.46  4717.8  1189.3  4745.4 1187.05  4782.8 1185.93  4788.6 1184.55
  4804.4 1184.34    4826 1181.92    4885 1178.51  4928.1 1175.87  4959.8 1171.72
  4971.4  1169.1  4999.9 1168.35  5002.7 1167.85  5005.9 1168.35  5024.5  1172.5
  5046.1 1172.98  5075.1  1176.2  5120.9 1178.83  5238.1 1179.08  5378.7 1181.04
  5675.7 1186.64  5914.4 1191.19  6018.6  1193.9  6059.2 1194.91    6084 1195.63
#Mann= 11 ,-1 , 0
  4101.5      .1       0  4482.6     .05       0  4527.1      .1       0
  4999.9     .07       0  5005.9      .1       0  5238.1     .05       0
  5378.7      .1       0  5675.7     .05       0  5914.4      .1       0
  6018.6     .05       0  6059.2      .1       0
Bank Sta=4885,5120.9
XS Rating Curve= 0 ,0
Exp/Cntr=0.3,0.1

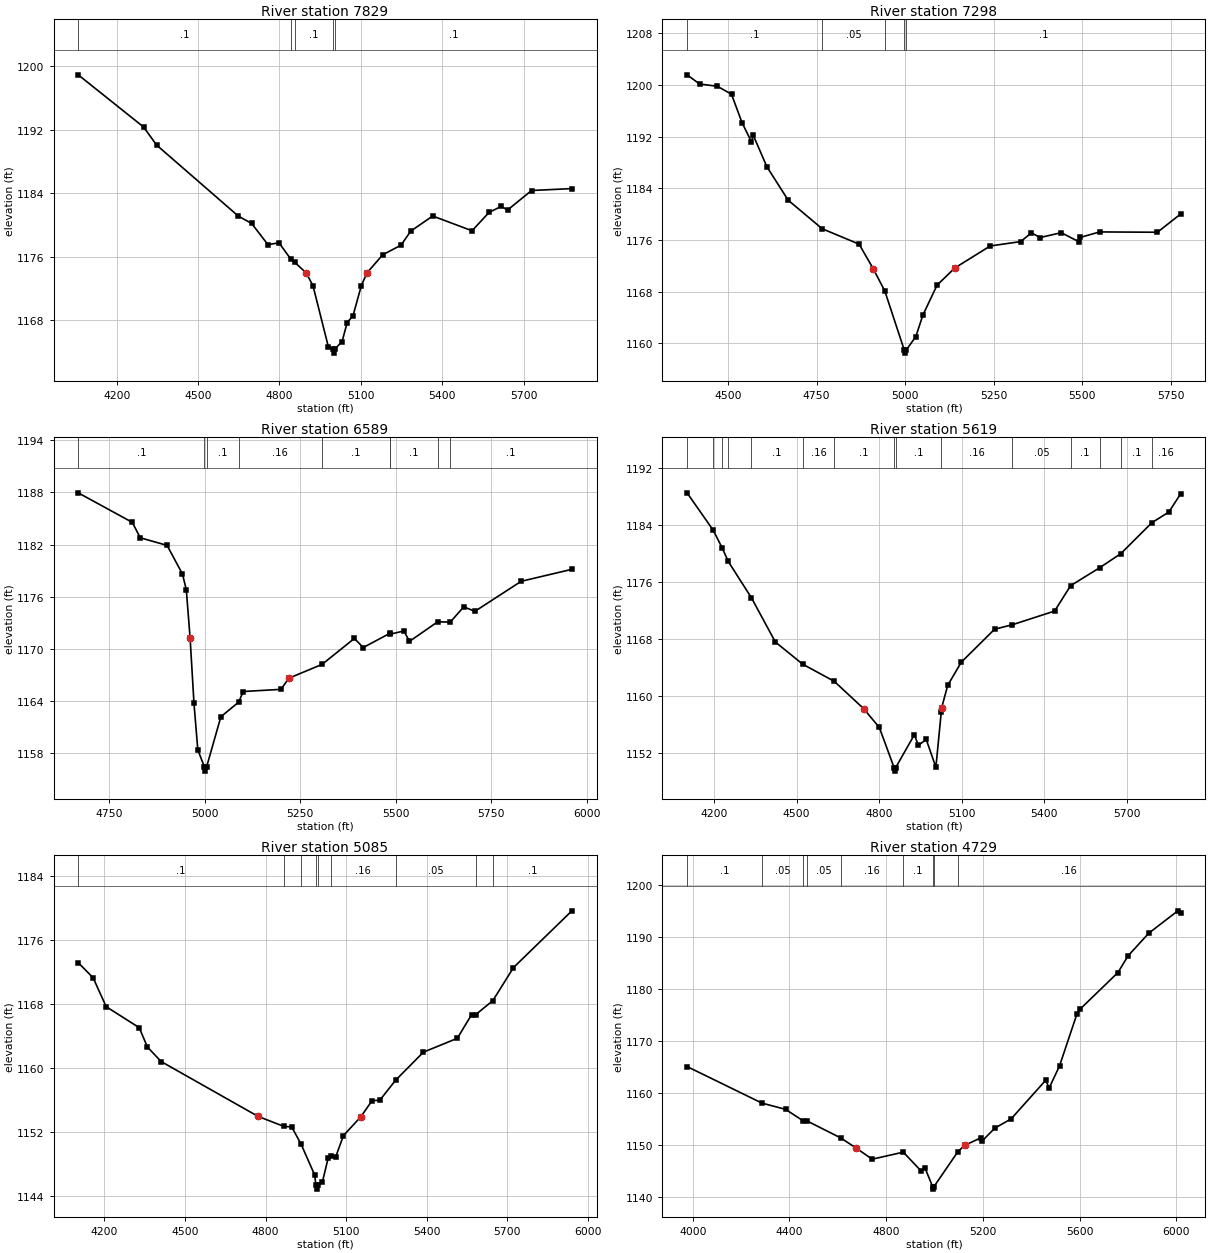
Type RM Length L Ch R = 1 ,7829    ,531,531,531
BEGIN DESCRIPTION:
TOWHEAD CREEK 13.0
END DESCRIPTION:
XS GIS Cut Line= 3
      2899316.78     10078000.19      2899650.11     10077444.65
      2899830.36     10076286.86
#Sta/Elev= 30
  4058.3 1198.92  4298.9 1192.36  4347.5 1190.07  4648.7 1181.13  4697.3 1180.22
  4757.7 1177.54  4798.2 1177.78  4841.7 1175.73    4856 1175.33  4899.4 1173.96
  4923.9 1172.34  4980.3 1164.68  4997.6 1164.39  5000.3 1163.89  5003.6 1164.39
  5030.9 1165.35  5049.6 1167.73  5071.4 1168.62  5101.8 1172.39  5122.6 1173.99
  5180.4 1176.26  5248.3 1177.49    5284 1179.25  5364.9 1181.15  5509.9 1179.29
  5572.7 1181.61  5617.9 1182.36  5640.7  1181.9  5729.3 1184.36  5877.9  1184.6
#Mann= 5 ,-1 , 0
  4058.3      .1       0  4841.7     .05       0    4856      .1       0
  4997.6     .07       0  5003.6      .1       0
Bank Sta=4899.4,5122.6
XS Rating Curve= 0 ,0
Exp/Cntr=0.3,0.1

Type RM Length L Ch R = 1 ,7298    ,709,709,709
BEGIN DESCRIPTION:
TOWHEAD CREEK 12.0
END DESCRIPTION:
XS GIS Cut Line= 3
      2900184.92     10077819.11      2900228.32     10076890.31
      2900059.51     10076457.47
#Sta/Elev= 30
  4383.9 1201.54  4419.3 1200.12  4469.4 1199.77  4509.4 1198.54  4539.4 1194.11
  4565.8 1191.19  4570.8  1192.2  4609.5 1187.31  4669.6 1182.15  4765.6 1177.74
  4869.8 1175.36  4909.8 1171.55  4942.4 1168.12  4997.2 1159.01    5000 1158.51
  5003.2 1159.01    5030 1161.06    5050 1164.39    5090 1169.02  5140.1 1171.67
  5240.2 1175.08  5326.6 1175.76  5356.5 1177.12    5381 1176.38  5440.7 1177.13
  5489.7 1175.76    5495 1176.41  5549.4 1177.25  5712.5  1177.2  5778.3 1180.03
#Mann= 5 ,-1 , 0
  4383.9      .1       0  4765.6     .05       0  4942.4      .1       0
  4997.2     .07       0  5003.2      .1       0
Bank Sta=4909.8,5140.1
XS Rating Curve= 0 ,0
Exp/Cntr=0.3,0.1

Type RM Length L Ch R = 1 ,6589    ,970,970,970
BEGIN DESCRIPTION:
TOWHEAD CREEK 11.0
END DESCRIPTION:
XS GIS Cut Line= 3
       2901139.8     10077063.92      2900640.64     10077011.84
      2900172.71     10076374.92
#Sta/Elev= 30
    4669 1187.96  4810.7 1184.55  4831.2 1182.78  4901.6  1181.9  4941.8  1178.6
  4951.9 1176.79  4961.9 1171.19    4972 1163.68    4982 1158.33  4999.1 1156.37
  5001.9 1155.87  5005.1 1156.37  5042.4 1162.14  5088.8 1163.82    5101 1165.05
  5199.7  1165.3  5220.6 1166.59  5307.3 1168.18  5391.9 1171.17    5415 1170.12
    5484 1171.74  5485.3 1171.66  5521.5 1172.03  5536.1 1170.83  5609.9 1173.09
  5642.8 1173.05  5678.1 1174.81  5707.4  1174.3  5828.6 1177.76  5961.2 1179.14
#Mann= 9 ,-1 , 0
    4669      .1       0  4999.1     .07       0  5005.1      .1       0
  5088.8     .16       0  5307.3      .1       0    5484     .16       0
  5485.3      .1       0  5609.9     .16       0  5642.8      .1       0
Bank Sta=4961.9,5220.6
XS Rating Curve= 0 ,0
Exp/Cntr=0.3,0.1

Type RM Length L Ch R = 1 ,5619    ,534,534,534
BEGIN DESCRIPTION:
TOWHEAD CREEK 10.0
END DESCRIPTION:
XS GIS Cut Line= 4
      2901296.04     10076816.56      2901148.46     10076386.84
      2900605.92     10075931.11      2900028.63     10075679.35
#Sta/Elev= 30
  4102.6 1188.56  4197.6  1183.3  4230.9 1180.76  4252.1 1178.92  4336.4 1173.81
  4423.2  1167.6  4522.3 1164.49  4637.3 1162.07  4743.4 1158.25  4800.7  1155.6
  4854.3 1149.96  4857.1 1149.46  4860.3 1149.96  4928.1 1154.58  4942.5 1153.08
  4971.1 1153.91  5006.2    1150  5025.7 1157.77  5027.1 1158.36  5049.1 1161.51
  5098.5 1164.77  5219.5  1169.4  5284.1 1170.03  5437.3 1171.95  5495.5 1175.52
  5601.1 1178.04  5677.5 1180.01  5790.7 1184.37  5852.1 1185.86  5895.3 1188.44
#Mann= 15 ,-1 , 0
  4102.6      .1       0  4197.6     .16       0  4230.9      .1       0
  4252.1     .16       0  4336.4      .1       0  4522.3     .16       0
  4637.3      .1       0  4854.3     .07       0  4860.3      .1       0
  5025.7     .16       0  5284.1     .05       0  5495.5      .1       0
  5601.1     .16       0  5677.5      .1       0  5790.7     .16       0
Bank Sta=4743.4,5027.1
XS Rating Curve= 0 ,0
Exp/Cntr=0.3,0.1

Type RM Length L Ch R = 1 ,5085    ,356,356,356
BEGIN DESCRIPTION:
TOWHEAD CREEK 9.0
END DESCRIPTION:
XS GIS Cut Line= 4
      2901465.29     10076495.31      2901317.73      10075844.3
      2900944.46     10075557.84      2900254.38     10075431.98
#Sta/Elev= 30
  4102.1 1173.22  4157.8 1171.31  4206.3 1167.71  4329.3 1165.09  4360.1 1162.66
  4411.3 1160.85  4772.3    1154  4869.1 1152.74  4897.4 1152.69  4932.4 1150.54
    4983 1146.69  4987.8 1145.41  4990.5 1144.91  4993.8 1145.41  5011.6 1145.76
  5033.4 1148.79  5044.3 1149.01  5061.5 1148.94  5090.5 1151.61  5154.9 1153.94
  5197.3 1155.98  5225.5    1156  5284.4 1158.51  5388.5 1162.03  5514.7 1163.76
    5568 1166.72    5583 1166.71  5647.1 1168.47    5724  1172.6  5941.6 1179.69
#Mann= 9 ,-1 , 0
  4102.1      .1       0  4869.1     .16       0  4932.4      .1       0
  4987.8     .07       0  4993.8      .1       0  5044.3     .16       0
  5284.4     .05       0    5583     .16       0  5647.1      .1       0
Bank Sta=4772.3,5154.9
XS Rating Curve= 0 ,0
Exp/Cntr=0.3,0.1

Type RM Length L Ch R = 1 ,4729    ,759,759,759
BEGIN DESCRIPTION:
TOWHEAD CREEK 8.0
END DESCRIPTION:
XS GIS Cut Line= 4
      2901560.78     10076260.94      2901534.74     10075518.78
      2900979.19     10075245.34      2900536.46     10074728.83
#Sta/Elev= 30
  3976.6 1165.12  4286.5  1158.1  4384.1  1156.9  4457.2 1154.68  4472.7 1154.68
  4612.4 1151.41  4674.2 1149.52  4742.4 1147.33  4871.1 1148.68  4944.7 1145.07
  4960.3  1145.7  4992.2 1142.08  4994.9 1141.58  4998.2 1142.08  5096.5 1148.75
  5124.4 1149.98  5191.8 1151.43  5197.4 1150.85    5250 1153.31  5316.9 1155.06
  5460.2 1162.49  5474.5 1161.02  5517.3 1165.24  5588.6 1175.12  5602.9 1176.17
  5758.7 1183.17  5801.5 1186.41  5886.1 1190.72  6006.8 1195.03  6018.7  1194.7
#Mann= 9 ,-1 , 0
  3976.6      .1       0  4286.5     .05       0  4457.2      .1       0
  4472.7     .05       0  4612.4     .16       0  4871.1      .1       0
  4992.2     .07       0  4998.2      .1       0  5096.5     .16       0
Bank Sta=4674.2,5124.4
XS Rating Curve= 0 ,0
Exp/Cntr=0.3,0.1