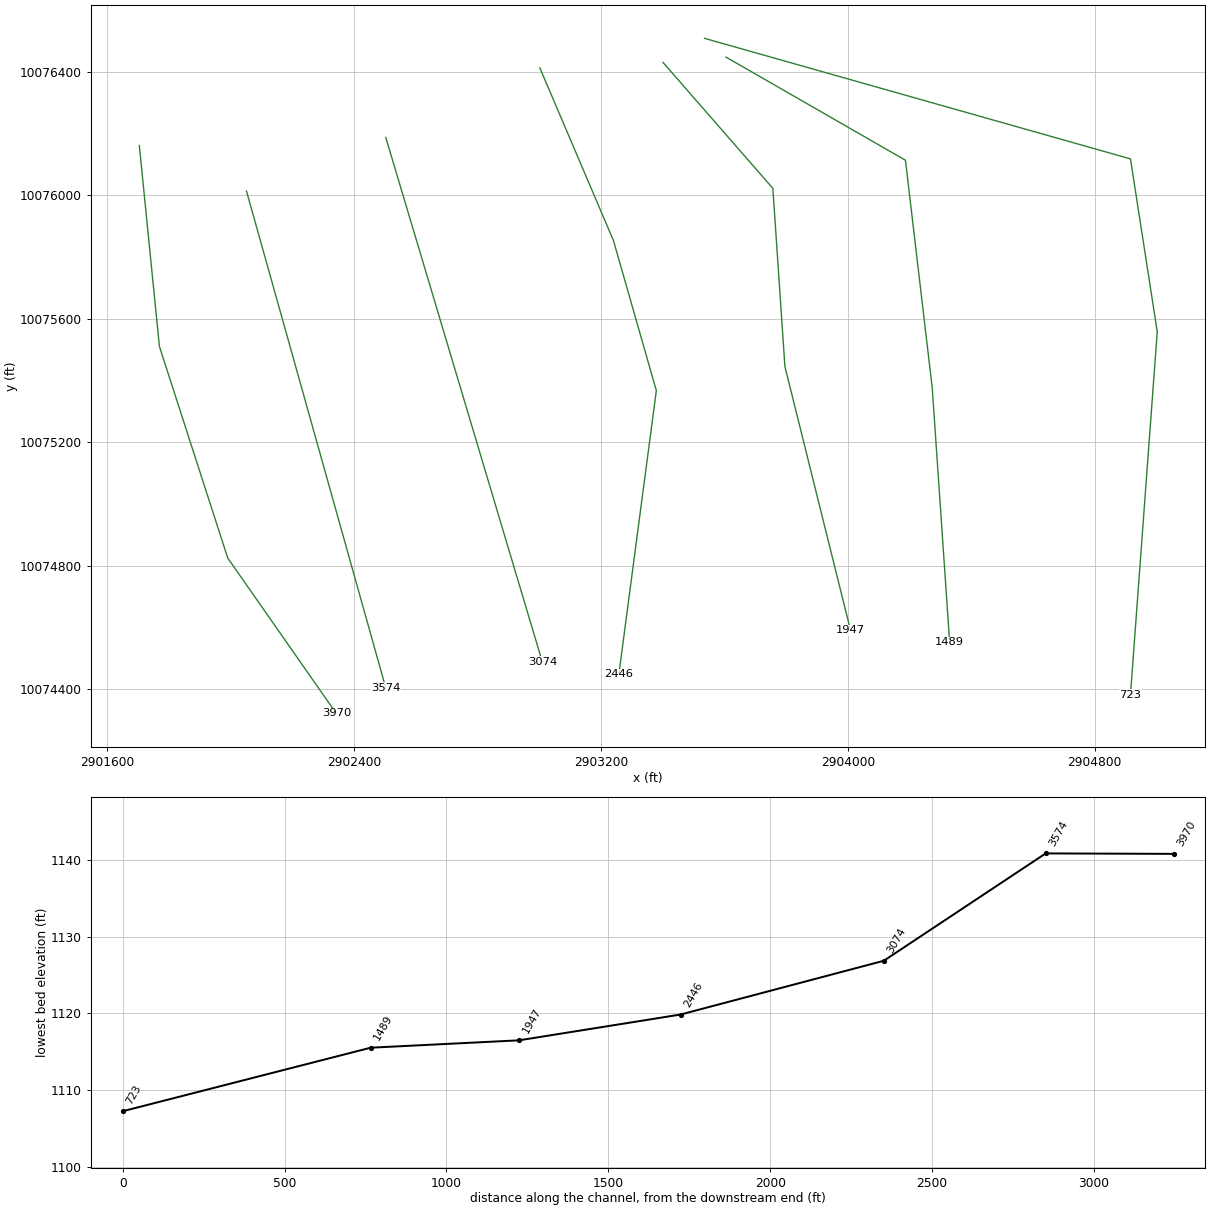
HEC-RAS study TOWHEAD CREEK.prj: TOWHEAD CREEK Base Level Engineering

--- TOWHEAD CREEK.g01 (geometry) --- (continued)

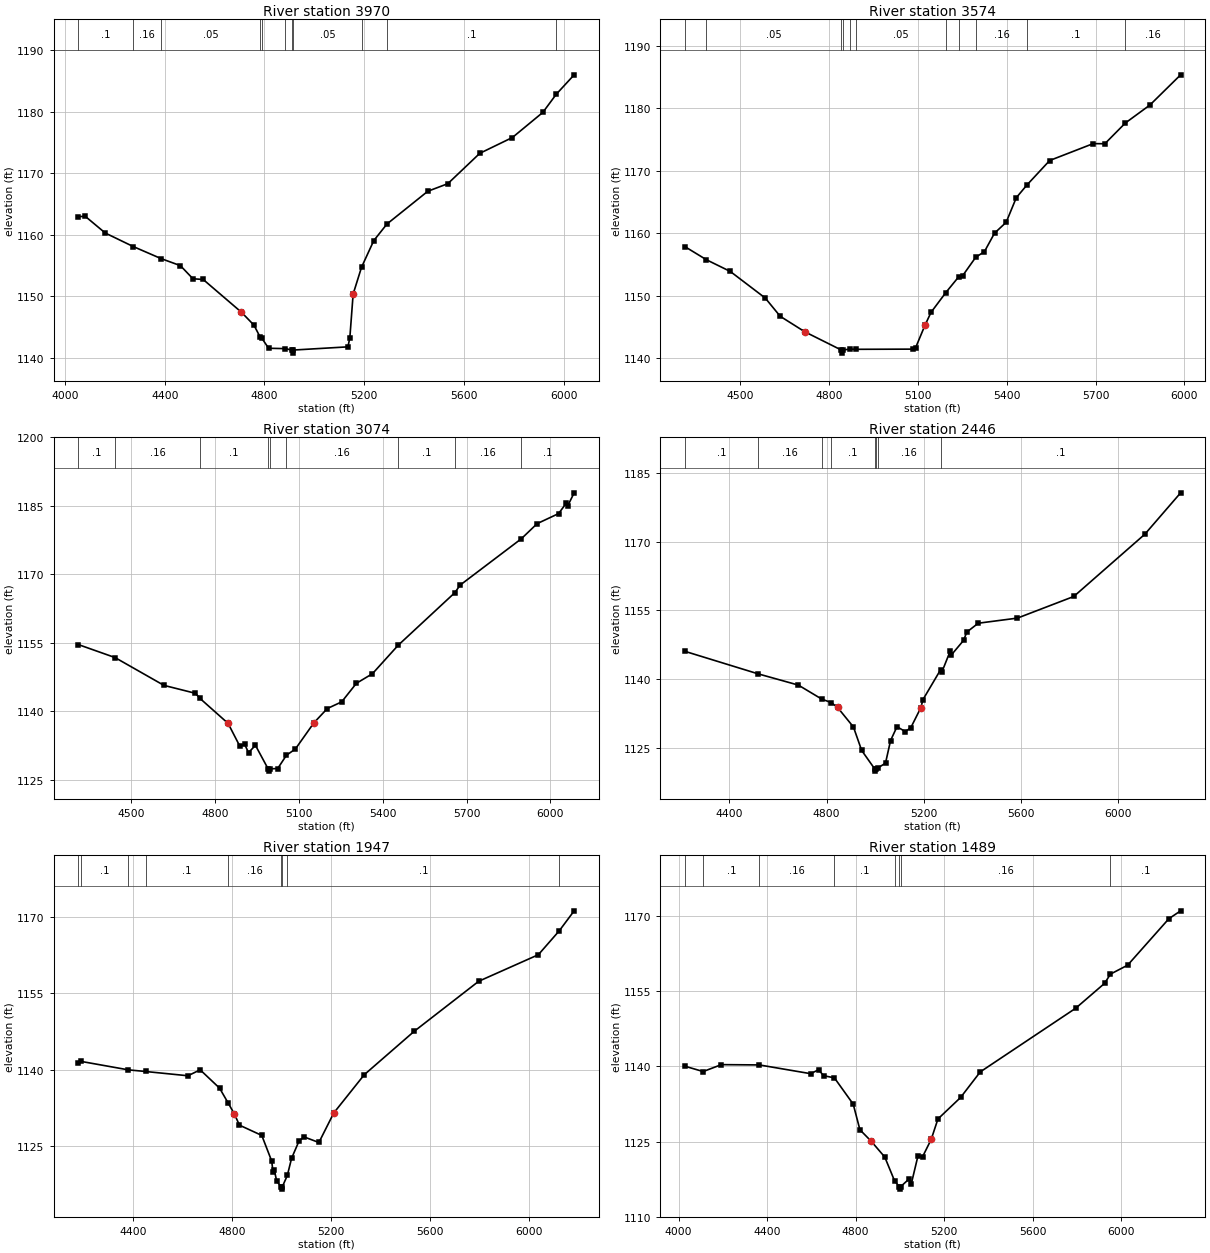
Type RM Length L Ch R = 1 ,3970    ,396,396,396
BEGIN DESCRIPTION:
TOWHEAD CREEK 7.0
END DESCRIPTION:
XS GIS Cut Line= 4
      2901704.01     10076161.12      2901769.12      10075510.1
      2901990.47     10074824.34      2902342.01      10074320.9
#Sta/Elev= 30
  4053.6 1162.94  4081.1 1163.01  4161.5 1160.29  4274.4 1158.08  4385.7 1156.13
    4463 1154.99  4513.3 1152.86  4554.5 1152.74  4707.9 1147.42  4758.2 1145.32
  4781.9 1143.46  4788.8 1143.25    4817 1141.57  4883.9 1141.51  4910.2 1141.28
  4912.9 1140.78  4916.2 1141.28  5134.9  1141.8  5142.7 1143.27  5155.9 1150.37
  5189.7 1154.74  5238.8 1159.06  5291.6 1161.75  5455.4 1167.07  5535.7  1168.3
  5663.9 1173.23  5794.8  1175.8  5916.9 1179.88    5971 1182.84  6042.5 1185.98
#Mann= 11 ,-1 , 0
  4053.6      .1       0  4274.4     .16       0  4385.7     .05       0
  4781.9     .16       0  4788.8      .1       0  4883.9     .05       0
  4910.2    .033       0  4916.2     .05       0  5189.7     .16       0
  5291.6      .1       0    5971     .16       0
Bank Sta=4707.9,5155.9
XS Rating Curve= 0 ,0
Exp/Cntr=0.3,0.1

Type RM Length L Ch R = 1 ,3574    ,500,500,500
BEGIN DESCRIPTION:
TOWHEAD CREEK 6.0
END DESCRIPTION:
XS GIS Cut Line= 2
      2902051.24     10076013.54      2902502.63     10074403.31
#Sta/Elev= 30
  4314.7 1157.88  4387.7 1155.77  4468.1  1153.9    4586 1149.65  4636.5 1146.73
  4719.5 1144.25  4842.5 1141.34  4845.2 1140.84  4848.5 1141.34  4870.2 1141.48
  4892.4 1141.45    5083 1141.48  5093.4 1141.73  5124.6 1145.28  5145.3 1147.37
  5195.2 1150.53  5238.4 1153.04  5251.8 1153.22  5296.1 1156.18  5325.2 1157.06
  5359.3 1160.02  5398.6 1161.76  5432.7 1165.69  5468.9 1167.74  5545.4 1171.64
  5692.1 1174.34  5731.4 1174.32  5800.7 1177.64  5883.4 1180.51    5987 1185.34
#Mann= 11 ,-1 , 0
  4314.7      .1       0  4387.7     .05       0  4842.5    .033       0
  4848.5     .05       0  4870.2      .1       0  4892.4     .05       0
  5195.2     .16       0  5238.4      .1       0  5296.1     .16       0
  5468.9      .1       0  5800.7     .16       0
Bank Sta=4719.5,5124.6
XS Rating Curve= 0 ,0
Exp/Cntr=0.3,0.1

Type RM Length L Ch R = 1 ,3074    ,628,628,628
BEGIN DESCRIPTION:
TOWHEAD CREEK 5.0
END DESCRIPTION:
XS GIS Cut Line= 2
      2902502.62      10076187.2      2903009.99      10074487.3
#Sta/Elev= 30
  4310.8 1154.58  4441.9 1151.74  4617.1 1145.64    4730  1143.9  4745.9 1142.79
  4846.6 1137.31  4888.4 1132.34  4906.1 1132.69  4919.7 1130.91  4944.5  1132.5
  4989.8 1127.35  4992.5 1126.85  4995.8 1127.35  5024.1 1127.42  5055.4 1130.33
  5087.4  1131.7  5153.7 1137.44  5201.5 1140.56  5253.1 1142.03  5305.8  1146.1
    5363 1148.19  5455.3 1154.44    5658 1165.96  5676.8 1167.61  5895.5 1177.75
  5952.4 1181.08  6029.1 1183.28    6057 1185.61  6062.2 1185.04  6084.8 1187.83
#Mann= 9 ,-1 , 0
  4310.8      .1       0  4441.9     .16       0  4745.9      .1       0
  4989.8     .07       0  4995.8      .1       0  5055.4     .16       0
  5455.3      .1       0    5658     .16       0  5895.5      .1       0
Bank Sta=4846.6,5153.7
XS Rating Curve= 0 ,0
Exp/Cntr=0.3,0.1

Type RM Length L Ch R = 1 ,2446    ,499,499,499
BEGIN DESCRIPTION:
TOWHEAD CREEK 4.0
END DESCRIPTION:
XS GIS Cut Line= 4
      2903001.77     10076412.85      2903240.47     10075852.98
      2903379.36     10075366.87      2903257.97     10074447.75
#Sta/Elev= 30
  4216.6 1146.04  4519.1  1141.1  4684.2 1138.65  4780.7 1135.58  4818.8 1134.84
  4845.3 1133.78  4910.9 1129.49  4944.7 1124.37  4998.3 1120.34    5001 1119.84
  5004.3 1120.34  5010.6  1120.5  5042.9 1121.59  5063.7 1126.53  5090.3 1129.56
  5124.1 1128.49  5146.9 1129.32  5188.5 1133.72  5196.9 1135.46  5269.4 1141.98
  5274.9 1141.49  5308.7 1146.01  5313.9 1145.24  5364.2 1148.42  5377.6 1150.24
  5424.7 1152.18  5586.1  1153.3  5818.1 1158.03  6110.6 1171.64  6257.9 1180.69
#Mann= 8 ,-1 , 0
  4216.6      .1       0  4519.1     .16       0  4780.7     .05       0
  4818.8      .1       0  4998.3     .07       0  5004.3      .1       0
  5010.6     .16       0  5269.4      .1       0
Bank Sta=4845.3,5188.5
XS Rating Curve= 0 ,0
Exp/Cntr=0.3,0.1

Type RM Length L Ch R = 1 ,1947    ,458,458,458
BEGIN DESCRIPTION:
TOWHEAD CREEK 3.0
END DESCRIPTION:
XS GIS Cut Line= 4
      2903401.07     10076430.23      2903756.96     10076022.25
      2903796.03       10075445.      2904008.71     10074589.92
#Sta/Elev= 30
  4180.1  1141.2  4192.5 1141.58  4382.3 1139.93  4451.2 1139.61  4622.5 1138.77
  4671.8 1139.94  4750.1 1136.34  4785.9 1133.32  4810.2 1131.22  4830.3 1129.06
  4920.5 1127.04  4960.6 1121.98  4965.7 1119.88  4970.8 1120.28  4980.6 1118.07
  4997.7 1116.98  5000.4 1116.48  5003.7 1116.98  5023.5 1119.16  5040.7 1122.53
  5070.8 1125.94  5090.9 1126.75    5151 1125.65  5211.1 1131.46  5334.2 1138.98
  5535.6 1147.51    5796 1157.35  6036.7 1162.57    6121 1167.27  6181.2  1171.2
#Mann= 9 ,-1 , 0
  4180.1     .16       0  4192.5      .1       0  4382.3     .16       0
  4451.2      .1       0  4785.9     .16       0  4997.7     .07       0
  5003.7     .16       0  5023.5      .1       0    6121     .05       0
Bank Sta=4810.2,5211.1
XS Rating Curve= 0 ,0
Exp/Cntr=0.3,0.1

Type RM Length L Ch R = 1 ,1489    ,766,766,766
BEGIN DESCRIPTION:
TOWHEAD CREEK 2.0
END DESCRIPTION:
XS GIS Cut Line= 4
      2903605.08     10076447.59      2904186.65      10076113.4
      2904273.46     10075375.55      2904329.88     10074550.87
#Sta/Elev= 30
  4028.1 1140.06  4111.1 1138.99  4193.5 1140.37  4364.9 1140.31  4597.1 1138.56
  4632.7 1139.37  4654.8 1138.16  4703.9 1137.74  4789.1 1132.48  4819.3 1127.37
  4869.7 1125.11  4931.7 1121.92  4976.1 1117.15  4997.6 1116.02  5000.3 1115.52
  5003.6 1116.02  5040.9 1117.53  5050.9 1116.47  5081.1 1122.06  5102.9 1122.02
  5141.6 1125.47  5171.8 1129.52  5274.1 1133.81  5363.1 1138.92  5794.4 1151.63
  5924.7 1156.59  5951.4 1158.44  6028.9 1160.22  6215.4  1169.5  6268.4 1171.07
#Mann= 8 ,-1 , 0
  4028.1     .16       0  4111.1      .1       0  4364.9     .16       0
  4703.9      .1       0  4976.1     .16       0  4997.6     .07       0
  5003.6     .16       0  5951.4      .1       0
Bank Sta=4869.7,5141.6
XS Rating Curve= 0 ,0
Exp/Cntr=0.3,0.1

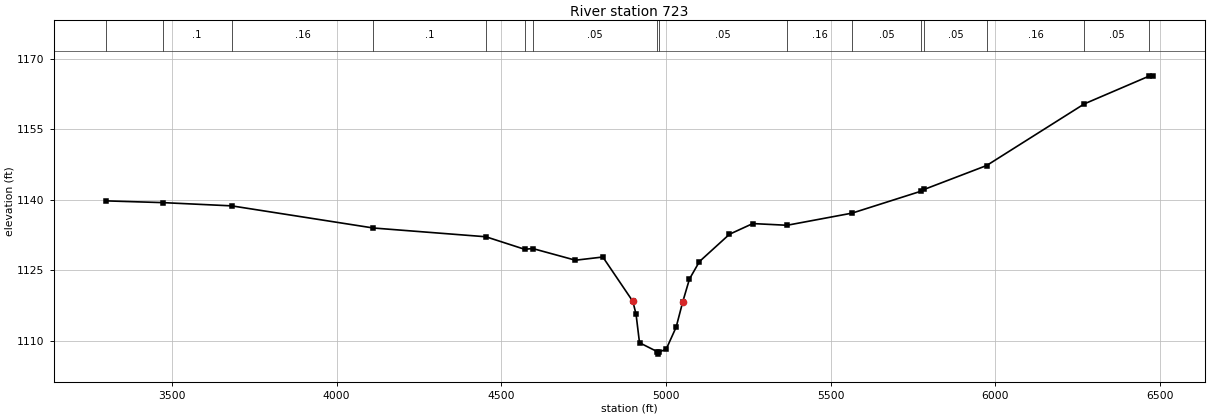
Type RM Length L Ch R = 1 ,723     ,0,0,0
BEGIN DESCRIPTION:
TOWHEAD CREEK 1.0
END DESCRIPTION:
XS GIS Cut Line= 4
      2903535.58     10076508.38      2904915.82     10076117.74
      2905002.62     10075557.84      2904915.81     10074381.58
#Sta/Elev= 30
  3299.1 1139.78  3471.9 1139.41  3681.2 1138.72  4111.3 1134.02  4453.2 1132.16
  4570.9  1129.5  4595.4 1129.66  4725.3 1127.18  4808.4 1127.86  4899.5 1118.45
  4909.3 1115.72  4919.8 1109.66  4974.4 1107.74  4977.1 1107.24  4980.4 1107.74
  5000.7 1108.26  5031.1 1112.97  5051.3 1118.39  5071.6  1123.2  5101.9  1126.9
    5193 1132.69  5263.8 1134.96  5367.9  1134.6  5565.5 1137.18  5776.1 1141.86
  5785.1 1142.23    5974 1147.28  6270.7 1160.37  6468.6  1166.3  6479.6 1166.33
#Mann= 16 ,-1 , 0
  3299.1     .16       0  3471.9      .1       0  3681.2     .16       0
  4111.3      .1       0  4453.2     .05       0  4570.9      .1       0
  4595.4     .05       0  4974.4     .04       0  4980.4     .05       0
  5367.9     .16       0  5565.5     .05       0  5776.1      .1       0
  5785.1     .05       0    5974     .16       0  6270.7     .05       0
  6468.6      .1       0
Bank Sta=4899.5,5051.3
XS Rating Curve= 0 ,0
Exp/Cntr=0.3,0.1

Chan Stop Cuts=-1
Use User Specified Reach Order=0
Composite Channel Slope=5