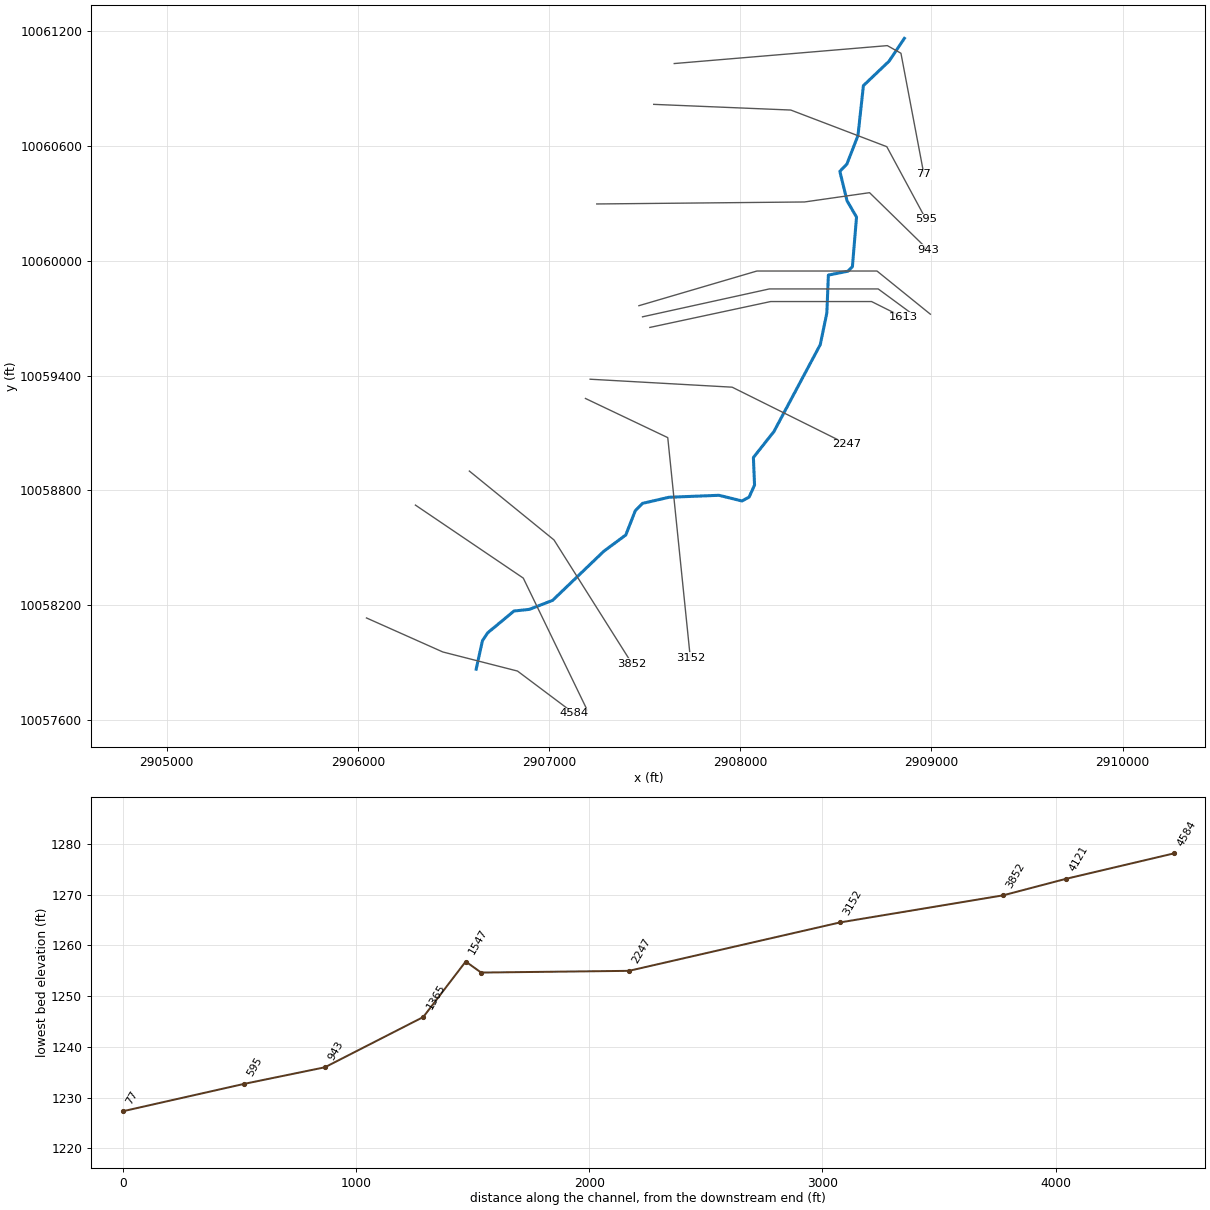
--- TRIBUTARY DC 1.prj (project) ---

Proj Title=TRIBUTARY DC 1 Base Level Engineering
Current Plan=p01
Default Exp/Contr=0.3,0.1
English Units
Geom File=g01
Flow File=f01
Plan File=p01
Y Axis Title=Elevation
X Axis Title(PF)=Main Channel Distance
X Axis Title(XS)=Station
BEGIN DESCRIPTION:
TRIBUTARY DC 1
END DESCRIPTION:
DSS Export Rating Curves= 0
DSS Export Rating Curve Sorted= 0
DSS Export Volume Flow Curves= 0
DXF OffsetX= 0
DXF OffsetY= 0
DXF ScaleX= 1
DXF ScaleY= 10

--- TRIBUTARY DC 1.p01 (plan) ---

Plan Title=Multiple Run
Short Identifier=Multiple
Geom File=g01
Flow File=f01
Subcritical Flow
K Sum by GR= 0
Std Step Tol= 0.01
Critical Tol= 0.01
Num of Std Step Trials= 20
Max Error Tol= 0.3
Flow Tol Ratio= 0.001
Split Flow NTrial= 30
Split Flow Tol= 0.02
Split Flow Ratio= 0.02
Log Output Level= 0
Friction Slope Method= 1
Unsteady Friction Slope Method= 2
Unsteady Bridges Friction Slope Method= 1
Parabolic Critical Depth
Global Vel Dist=  1 , 1 , 1
Global Log Level= 0
CheckData=True
Encroach Param= -1, 0, 0, 0
BEGIN DESCRIPTION:
Multiple Run
END DESCRIPTION:

--- TRIBUTARY DC 1.f01 (steady flow) ---

Flow Title=Multiple
Program Version=4.10
Number of Profiles= 7
Profile Names=10-year,25-year,50-year,1pct_min,100-year,1pct_plu,500-year
River Rch & RM=TRIBUTARY DC 1,Reach-1         ,4584
     883    1277    1619    1504    2034    2751    3221
River Rch & RM=TRIBUTARY DC 1,Reach-1         ,3152
    1095    1600    2042    1908    2580    3489    4131
Boundary for River Rch & Prof#=TRIBUTARY DC 1,Reach-1         , 1
Up Type= 0
Dn Type= 3
Dn Slope=0.01
Boundary for River Rch & Prof#=TRIBUTARY DC 1,Reach-1         , 2
Up Type= 0
Dn Type= 3
Dn Slope=0.01
Boundary for River Rch & Prof#=TRIBUTARY DC 1,Reach-1         , 3
Up Type= 0
Dn Type= 3
Dn Slope=0.01
Boundary for River Rch & Prof#=TRIBUTARY DC 1,Reach-1         , 4
Up Type= 0
Dn Type= 3
Dn Slope=0.01
Boundary for River Rch & Prof#=TRIBUTARY DC 1,Reach-1         , 5
Up Type= 0
Dn Type= 3
Dn Slope=0.01
Boundary for River Rch & Prof#=TRIBUTARY DC 1,Reach-1         , 6
Up Type= 0
Dn Type= 3
Dn Slope=0.01
Boundary for River Rch & Prof#=TRIBUTARY DC 1,Reach-1         , 7
Up Type= 0
Dn Type= 3
Dn Slope=0.01
DSS Import GetInterval= 0
DSS Import GetPeak= 0
DSS Import FillOption= 0

--- TRIBUTARY DC 1.g01 (geometry) ---

Geom Title=Existing Conditions
Program Version=4.10

River Reach=TRIBUTARY DC 1  ,Reach-1
Reach XY= 30
      2906618.47     10057863.73      2906651.23     10058012.65
      2906678.29      10058053.8      2906816.05     10058168.13
      2906897.11       10058177.       2907018.4      10058224.1
      2907285.24     10058480.05      2907401.13     10058566.08
      2907450.79     10058692.95      2907489.16     10058731.56
      2907627.75     10058763.32      2907888.29     10058773.56
      2908008.83     10058743.88      2908046.23     10058764.27
      2908074.58     10058826.96      2908068.56     10058971.32
      2908175.97     10059106.99      2908418.33     10059561.55
      2908452.75      10059727.6      2908460.75     10059925.37
      2908563.06     10059945.64      2908586.44     10059968.99
      2908607.93     10060229.08      2908558.47     10060313.73
      2908520.69     10060467.84      2908557.47      10060505.8
       2908615.5     10060654.96      2908643.97     10060916.25
      2908777.85     10061043.86      2908858.47     10061163.73

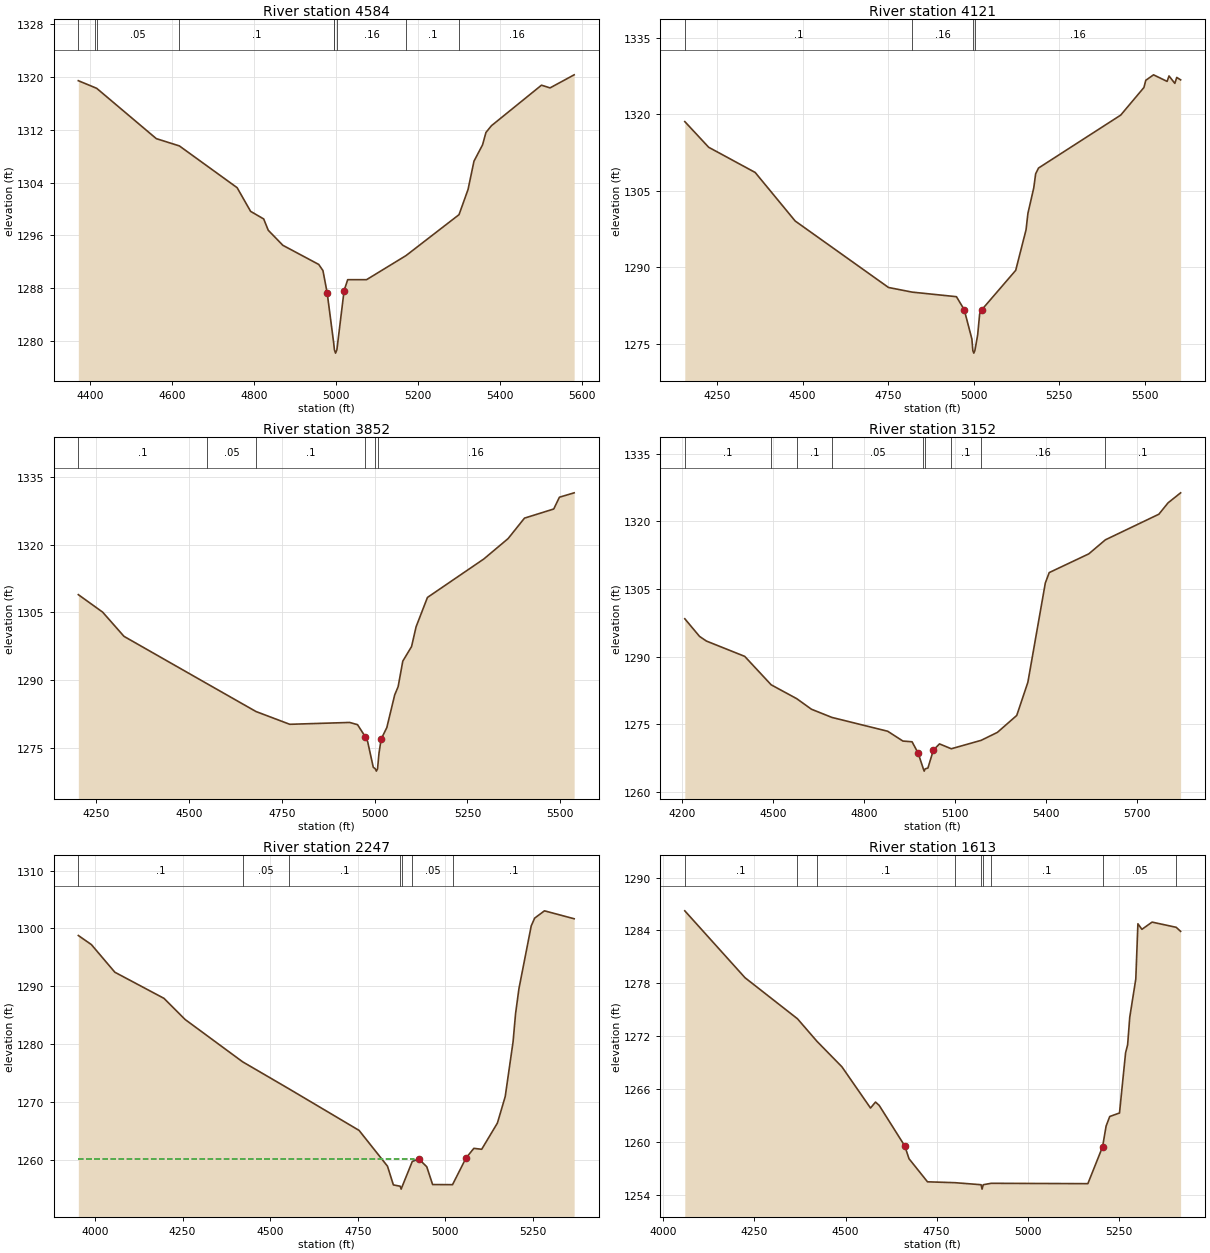
Type RM Length L Ch R = 1 ,4584    ,463,463,463
BEGIN DESCRIPTION:
TRIBUTARY DC 1 10.0
END DESCRIPTION:
XS GIS Cut Line= 4
       2906044.7     10058132.02      2906443.99     10057954.08
      2906834.62     10057854.25      2907129.79     10057632.87
#Sta/Elev= 30
  4370.7 1319.44  4410.3 1318.42  4415.6 1318.28  4560.9 1310.66  4617.1 1309.56
    4758 1303.23  4790.9 1299.64  4822.8 1298.49  4833.9 1296.78  4869.5  1294.5
    4957  1291.6  4967.3 1290.67  4977.6  1287.3  4993.5 1279.71  4995.3 1278.66
    4998 1278.16  5001.3 1278.66  5018.9 1287.64  5027.7 1289.29  5073.7 1289.29
  5169.9 1292.94  5299.2 1299.14  5321.2 1302.96  5335.7 1307.25  5356.6 1309.72
  5364.9  1311.6  5378.3 1312.62  5500.3 1318.76  5521.2 1318.35    5580 1320.33
#Mann= 9 ,-1 , 0
  4370.7     .05       0  4410.3      .1       0  4415.6     .05       0
  4617.1      .1       0  4993.5     .16       0  4995.3     .07       0
  5001.3     .16       0  5169.9      .1       0  5299.2     .16       0
Bank Sta=4977.6,5018.9
XS Rating Curve= 0 ,0
Exp/Cntr=0.3,0.1

Type RM Length L Ch R = 1 ,4121    ,269,269,269
BEGIN DESCRIPTION:
TRIBUTARY DC 1 9.0
END DESCRIPTION:
XS GIS Cut Line= 3
      2906300.74     10058722.32        2906865.     10058340.36
      2907199.22     10057650.22
#Sta/Elev= 30
    4156  1318.6  4225.7 1313.56  4361.6 1308.61  4478.4 1299.08    4751 1286.03
  4819.8 1285.12  4949.4 1284.22    4972  1281.7  4994.6  1275.9  4997.3 1273.64
  5000.1 1273.14  5003.3 1273.64  5011.4 1276.72  5017.2 1280.81  5022.7  1281.6
  5122.5 1289.39  5152.7 1297.35  5158.2 1300.58  5175.3  1305.6  5180.8 1308.35
  5189.2 1309.48  5429.2 1319.87    5497 1325.29  5502.5 1326.71  5525.1 1327.78
  5564.7 1326.49  5570.3 1327.56  5587.3  1326.1  5592.9 1327.27  5604.2 1326.79
#Mann= 4 ,-1 , 0
    4156      .1       0  4819.8     .16       0  4997.3     .07       0
  5003.3     .16       0
Bank Sta=4972,5022.7
XS Rating Curve= 0 ,0
Exp/Cntr=0.3,0.1

Type RM Length L Ch R = 1 ,3852    ,700,700,700
BEGIN DESCRIPTION:
TRIBUTARY DC 1 8.0
END DESCRIPTION:
XS GIS Cut Line= 3
      2906582.88     10058900.26      2907025.59     10058540.01
      2907433.52      10057893.4
#Sta/Elev= 30
  4202.1 1308.94  4267.6 1305.07  4325.1 1299.71  4548.7 1289.24  4680.5 1283.08
  4771.5 1280.25  4932.8 1280.66    4954 1280.17  4975.1 1277.48  4975.2 1277.46
  4981.3 1276.41  4996.4 1270.75  5001.9 1270.39  5004.7 1269.89  5007.9 1270.39
  5011.7 1273.78  5017.6 1276.98  5032.9 1279.53  5054.1 1286.75  5063.4 1288.59
  5075.9 1294.23  5099.5 1297.45  5111.7 1301.83  5142.3 1308.32  5294.1 1316.83
  5359.6 1321.35  5403.6 1325.87  5482.4 1327.89  5497.7  1330.5  5537.4 1331.47
#Mann= 6 ,-1 , 0
  4202.1      .1       0  4548.7     .05       0  4680.5      .1       0
  4975.1     .16       0  5001.9     .07       0  5007.9     .16       0
Bank Sta=4975.2,5017.6
XS Rating Curve= 0 ,0
Exp/Cntr=0.3,0.1

Type RM Length L Ch R = 1 ,3152    ,905,905,905
BEGIN DESCRIPTION:
TRIBUTARY DC 1 7.0
END DESCRIPTION:
XS GIS Cut Line= 3
      2907190.06     10059280.05      2907620.64     10059075.17
      2907738.69     10057922.44
#Sta/Elev= 30
  4209.2 1298.39    4258 1294.46  4280.8 1293.43  4406.8 1290.04  4494.1 1283.72
  4578.6 1280.63    4627 1278.29  4694.6 1276.47  4878.5  1273.4  4928.7 1271.22
  4958.9 1271.06    4979 1268.54  4996.1 1265.04  4998.9 1264.54  5002.1 1265.04
  5011.2 1265.23  5029.3 1269.23  5049.4 1270.59  5088.3 1269.51  5186.8 1271.38
  5240.4 1273.15  5304.2 1276.91  5340.9 1284.28  5398.5 1306.34  5411.3 1308.65
  5541.9 1312.81  5596.6 1315.93  5773.1 1321.62  5803.3 1324.14  5844.8 1326.37
#Mann= 9 ,-1 , 0
  4209.2      .1       0  4494.1     .05       0  4578.6      .1       0
  4694.6     .05       0  4996.1    .035       0  5002.1     .05       0
  5088.3      .1       0  5186.8     .16       0  5596.6      .1       0
Bank Sta=4979,5029.3
XS Rating Curve= 0 ,0
Exp/Cntr=0.3,0.1

Type RM Length L Ch R = 1 ,2247    ,634,634,634
BEGIN DESCRIPTION:
TRIBUTARY DC 1 6.0
END DESCRIPTION:
XS GIS Cut Line= 3
      2907214.44     10059380.72      2907957.45     10059339.06
      2908558.14     10059040.45
#Sta/Elev= 30
  3952.5 1298.78  3989.8 1297.21  4056.7 1292.44  4196.9 1287.93    4257 1284.29
  4421.4 1276.97  4554.4 1272.28  4753.7 1265.13  4834.8 1258.95  4851.6 1255.72
    4871 1255.49  4873.8 1254.99    4877 1255.49  4905.6 1259.77  4924.4 1260.18
  4946.8 1258.86  4963.6 1255.78  5020.4 1255.76  5058.8 1260.35  5081.2 1262.03
  5103.6 1261.87  5148.4 1266.39  5170.8 1270.98  5193.2 1280.44  5200.3 1285.29
    5210 1289.63    5245 1300.44  5254.8 1301.78  5282.8 1303.04  5367.5 1301.67
#Mann= 7 ,-1 , 0
  3952.5      .1       0  4421.4     .05       0  4554.4      .1       0
    4871    .033       0    4877      .1       0  4905.6     .05       0
  5020.4      .1       0
#XS Ineff= 2 , 0
            4910 1260.14
Permanent Ineff=
       T       T
Bank Sta=4924.4,5058.8
XS Rating Curve= 0 ,0
Exp/Cntr=0.3,0.1

Type RM Length L Ch R = 1 ,1613    ,66,66,66
BEGIN DESCRIPTION:
TRIBUTARY DC 1 5.0
END DESCRIPTION:
XS GIS Cut Line= 4
      2907526.92     10059651.57      2908158.84     10059786.98
      2908686.61     10059786.98       2908853.3     10059703.63
#Sta/Elev= 30
    4059 1286.23  4224.2 1278.64  4368.2 1273.98  4421.7 1271.42  4490.1 1268.53
  4568.6 1263.85  4582.2 1264.53  4592.4 1264.15  4662.4 1259.56  4674.2  1258.1
  4724.9 1255.48  4800.5 1255.38  4871.9 1255.15  4874.6 1254.65  4877.9 1255.15
  4899.5 1255.31  5164.9 1255.27  5205.3 1259.46  5214.9  1261.8  5224.9 1262.89
  5251.7 1263.29  5268.4 1270.12    5274 1271.03  5279.8 1274.15  5296.4 1278.49
  5302.2 1284.76  5313.2 1284.13  5341.1 1284.95  5407.2 1284.36  5419.4  1283.9
#Mann= 9 ,-1 , 0
    4059      .1       0  4368.2     .05       0  4421.7      .1       0
  4800.5     .05       0  4871.9     .07       0  4877.9     .05       0
  4899.5      .1       0  5205.3     .05       0  5407.2      .1       0
Bank Sta=4662.4,5205.3
XS Rating Curve= 0 ,0
Exp/Cntr=0.3,0.1

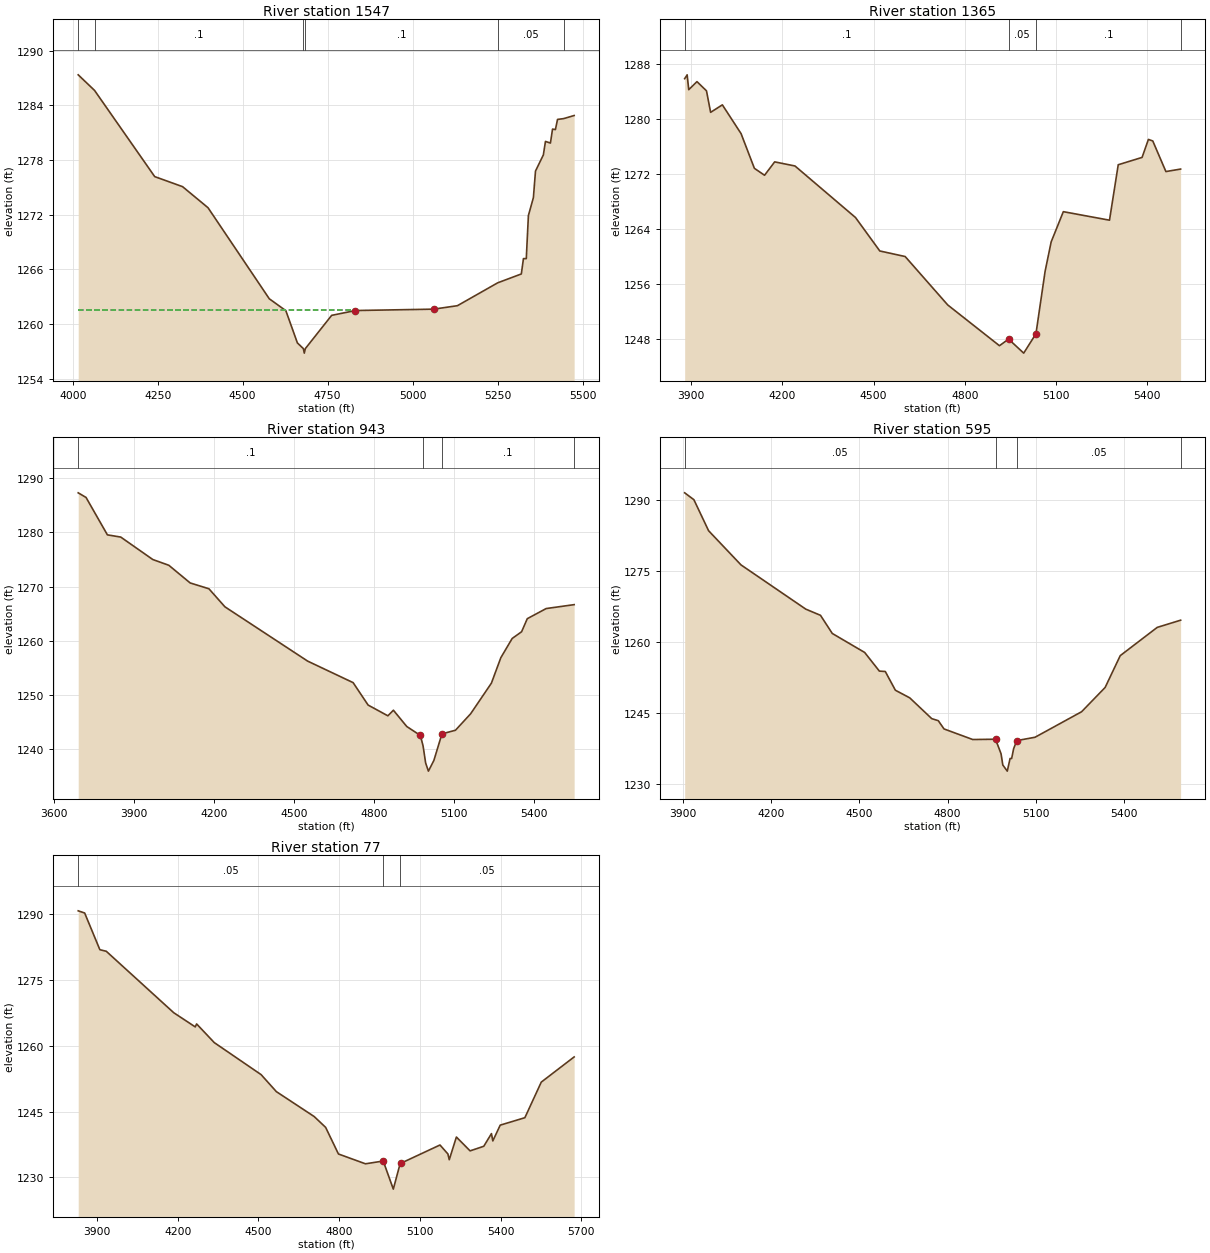
Type RM Length L Ch R = 1 ,1547    ,182,182,182
BEGIN DESCRIPTION:
TRIBUTARY DC 1 4.0
END DESCRIPTION:
XS GIS Cut Line= 4
      2907488.66     10059707.11      2908151.89     10059852.95
      2908721.34     10059852.95      2908890.96     10059728.33
#Sta/Elev= 30
  4016.2 1287.34  4064.3 1285.63  4241.3 1276.18  4323.2 1275.08  4398.1 1272.77
  4578.3 1262.79  4627.1 1261.48    4661 1257.95  4678.5 1257.33  4681.3 1256.83
  4684.5 1257.33  4761.8 1260.97  4831.8  1261.5  5061.8 1261.65  5131.8 1262.03
  5250.4 1264.54  5319.8 1265.51    5326 1267.19  5334.4 1267.19  5340.6 1271.91
  5355.3 1273.88  5361.5 1276.79  5384.6 1278.56  5390.8 1280.04  5405.4 1279.86
  5411.6 1281.39  5420.1 1281.34  5426.3 1282.45  5444.4 1282.54  5475.2 1282.88
#Mann= 6 ,-1 , 0
  4016.2     .16       0  4064.3      .1       0  4678.5     .07       0
  4684.5      .1       0  5250.4     .05       0  5444.4      .1       0
#XS Ineff= 2 , 0
         4820.91 1261.53
Permanent Ineff=
       T       T
Bank Sta=4831.8,5061.8
XS Rating Curve= 0 ,0
Exp/Cntr=0.3,0.1

Type RM Length L Ch R = 1 ,1365    ,422,422,422
BEGIN DESCRIPTION:
TRIBUTARY DC 1 3.0
END DESCRIPTION:
XS GIS Cut Line= 4
      2907469.68     10059765.25      2908086.85     10059946.63
      2908714.97     10059946.63       2908994.2     10059720.81
#Sta/Elev= 30
  3878.9 1285.83    3887 1286.39  3892.3 1284.23  3919.3  1285.4  3950.6 1284.06
  3964.2 1280.93  4002.8 1282.02  4064.3 1277.83  4108.1 1272.78  4141.5 1271.77
  4174.8 1273.72  4241.6 1273.12  4440.5 1265.62  4520.4 1260.75  4603.8 1259.94
  4743.8 1252.89  4913.8 1246.96  4943.8 1247.92  4993.5 1245.88  5033.8  1248.7
  5063.8 1257.77  5083.8 1262.07  5123.8 1266.47  5275.6 1265.23  5304.3  1273.3
  5382.7 1274.37  5403.5 1276.99  5417.9 1276.76    5461 1272.31  5509.4 1272.67
#Mann= 4 ,-1 , 0
  3878.9      .1       0  4943.8     .05       0  5033.8      .1       0
  5509.4      .1       0
Bank Sta=4943.8,5033.8
XS Rating Curve= 0 ,0
Exp/Cntr=0.3,0.1

Type RM Length L Ch R = 1 ,943     ,348,348,348
BEGIN DESCRIPTION:
TRIBUTARY DC 1 2.0
END DESCRIPTION:
XS GIS Cut Line= 4
      2907249.14     10060297.39      2908335.92     10060307.81
       2908676.2     10060356.42      2908981.25      10060058.3
#Sta/Elev= 30
  3691.7 1287.28    3721 1286.43    3801 1279.53    3851 1279.12    3971 1274.98
    4031 1273.92    4111 1270.66  4181.1 1269.59  4241.1 1266.26  4551.1 1256.24
  4721.1 1252.28  4777.3 1248.14  4851.3 1246.16    4872 1247.19    4922 1244.19
    4973 1242.54  4983.1  1240.6  4992.7 1237.46  5003.1 1235.96  5023.5 1237.93
  5053.8 1242.83  5104.4  1243.5  5161.1 1246.53  5238.9 1252.18  5274.3 1256.88
  5316.7 1260.42    5352 1261.66  5373.3 1264.07    5444 1265.94  5548.8 1266.66
#Mann= 4 ,-1 , 0
  3691.7      .1       0  4983.1     .05       0  5053.8      .1       0
  5548.8     .05       0
Bank Sta=4973,5053.8
XS Rating Curve= 0 ,0
Exp/Cntr=0.3,0.1

Type RM Length L Ch R = 1 ,595     ,518,518,518
BEGIN DESCRIPTION:
Mapping XS bb126f2e
END DESCRIPTION:
XS GIS Cut Line= 4
      2907547.19     10060818.38      2908264.13     10060788.65
      2908766.31     10060597.03      2908970.72     10060217.88
#Sta/Elev= 30
  3906.5 1291.49  3937.8 1290.04  3987.8 1283.48  4097.9 1276.26  4318.1 1266.91
  4368.2  1265.6  4408.2 1261.77  4518.3 1257.75  4568.3 1253.81  4588.4 1253.73
  4622.7 1249.77  4671.5 1248.16  4746.4 1243.76  4768.6 1243.33    4788 1241.59
  4885.6 1239.35  4963.1 1239.41  4981.9 1236.35  4987.9 1233.96  5003.1 1232.67
  5012.6 1235.34  5017.9 1235.33  5024.7 1237.41  5035.4 1239.12  5097.5 1239.83
  5255.7 1245.22  5335.7 1250.35  5387.1 1257.08  5512.8 1263.05  5592.3 1264.57
#Mann= 4 ,-1 , 0
  3906.5     .05       0  4963.1    .035       0  5035.4     .05       0
  5592.3     .05       0
Bank Sta=4963.1,5035.4
XS Rating Curve= 0 ,0
Exp/Cntr=0.3,0.1

Type RM Length L Ch R = 1 ,77      ,0,0,0
BEGIN DESCRIPTION:
TRIBUTARY DC 1 1.0
END DESCRIPTION:
XS GIS Cut Line= 4
      2907654.54     10061031.87      2908769.15     10061125.63
      2908840.33      10061085.7      2908960.13     10060453.71
#Sta/Elev= 30
  3830.2  1290.8  3854.2  1290.3  3910.7 1281.93  3934.5 1281.57  4185.4 1267.54
  4265.3 1264.31  4270.3 1264.99  4335.9 1260.73    4510 1253.42  4566.7 1249.54
  4707.2 1243.86  4749.8 1241.39  4797.5 1235.31  4897.9 1233.07    4964  1233.7
  5001.4 1227.29  5027.3 1233.22  5030.4 1233.22  5174.9 1237.36  5204.3 1235.32
  5209.4    1234  5235.9 1239.18  5286.8 1236.02  5337.7 1237.07  5366.2 1239.96
  5371.3 1238.29  5398.8 1241.89  5490.4 1243.59  5551.4 1251.71  5673.6 1257.46
#Mann= 3 ,-1 , 0
  3830.2     .05       0    4964    .035       0  5027.3     .05       0
Bank Sta=4964,5030.4
XS Rating Curve= 0 ,0
Exp/Cntr=0.3,0.1

Chan Stop Cuts=-1
Use User Specified Reach Order=0
Composite Channel Slope=5