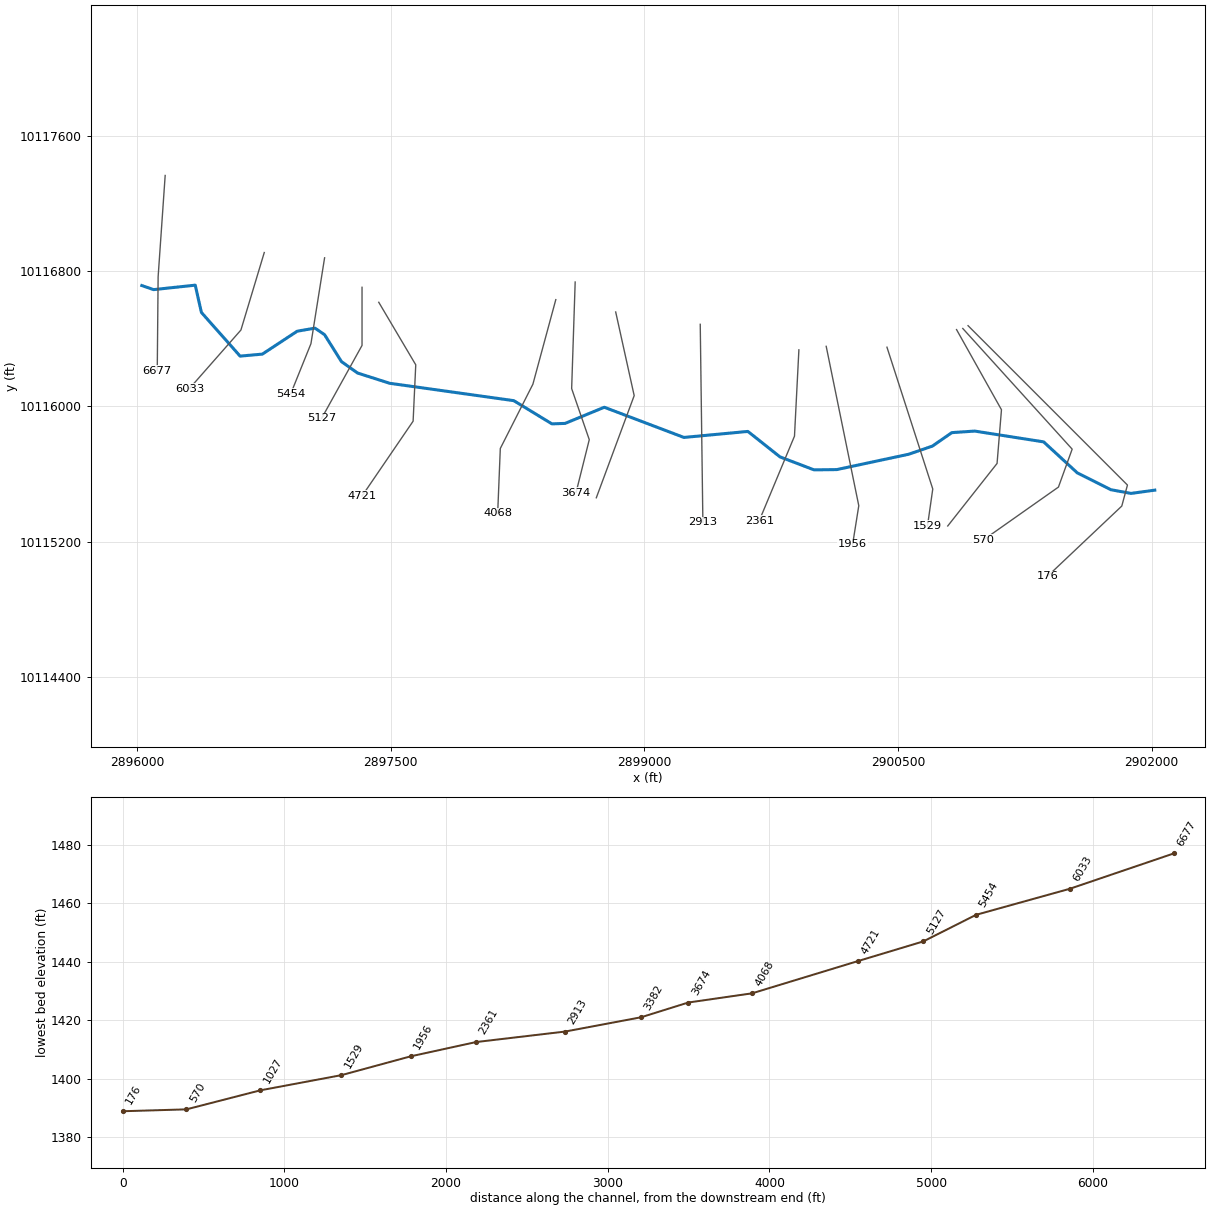
--- UNT 0002 IN LATR.prj (project) ---

Proj Title=UNT 1002 IN LATR Base Level Engineering
Current Plan=p01
Default Exp/Contr=0.3,0.1
English Units
Geom File=g01
Flow File=f01
Plan File=p01
Y Axis Title=Elevation
X Axis Title(PF)=Main Channel Distance
X Axis Title(XS)=Station
BEGIN DESCRIPTION:
UNT 1002 IN LATR
END DESCRIPTION:
DSS Export Rating Curves= 0
DSS Export Rating Curve Sorted= 0
DSS Export Volume Flow Curves= 0
DXF OffsetX= 0
DXF OffsetY= 0
DXF ScaleX= 1
DXF ScaleY= 10

--- UNT 0002 IN LATR.p01 (plan) ---

Plan Title=Multiple Run
Short Identifier=Multiple
Geom File=g01
Flow File=f01
Subcritical Flow
K Sum by GR= 0
Std Step Tol= 0.01
Critical Tol= 0.01
Num of Std Step Trials= 20
Max Error Tol= 0.3
Flow Tol Ratio= 0.001
Split Flow NTrial= 30
Split Flow Tol= 0.02
Split Flow Ratio= 0.02
Log Output Level= 0
Friction Slope Method= 1
Unsteady Friction Slope Method= 2
Unsteady Bridges Friction Slope Method= 1
Parabolic Critical Depth
Global Vel Dist=  1 , 1 , 1
Global Log Level= 0
CheckData=True
Encroach Param= -1, 0, 0, 0
BEGIN DESCRIPTION:
Multiple Run
END DESCRIPTION:

--- UNT 0002 IN LATR.f01 (steady flow) ---

Flow Title=Multiple
Program Version=4.10
Number of Profiles= 7
Profile Names=10-year,25-year,50-year,1pct_min,100-year,1pct_plu,500-year
River Rch & RM=UNT 1002 IN LATR,Reach-1         ,6677
    1371    2046    2648    2506    3389    4583    5575
Boundary for River Rch & Prof#=UNT 1002 IN LATR,Reach-1         , 1
Up Type= 0
Dn Type= 3
Dn Slope=0.005
Boundary for River Rch & Prof#=UNT 1002 IN LATR,Reach-1         , 2
Up Type= 0
Dn Type= 3
Dn Slope=0.005
Boundary for River Rch & Prof#=UNT 1002 IN LATR,Reach-1         , 3
Up Type= 0
Dn Type= 3
Dn Slope=0.005
Boundary for River Rch & Prof#=UNT 1002 IN LATR,Reach-1         , 4
Up Type= 0
Dn Type= 3
Dn Slope=0.005
Boundary for River Rch & Prof#=UNT 1002 IN LATR,Reach-1         , 5
Up Type= 0
Dn Type= 3
Dn Slope=0.005
Boundary for River Rch & Prof#=UNT 1002 IN LATR,Reach-1         , 6
Up Type= 0
Dn Type= 3
Dn Slope=0.005
Boundary for River Rch & Prof#=UNT 1002 IN LATR,Reach-1         , 7
Up Type= 0
Dn Type= 3
Dn Slope=0.005
DSS Import GetInterval= 0
DSS Import GetPeak= 0
DSS Import FillOption= 0

--- UNT 0002 IN LATR.g01 (geometry) ---

Geom Title=Existing Conditions
Program Version=4.10

River Reach=UNT 1002 IN LATR,Reach-1
Reach XY= 30
      2896028.47     10116713.73      2896098.38     10116689.67
      2896344.45     10116716.01      2896380.82     10116554.71
      2896609.67     10116296.39      2896741.31     10116308.23
      2896947.33     10116443.72      2897052.47     10116461.88
      2897109.14     10116423.16      2897209.05     10116263.95
      2897304.24     10116196.39      2897494.28      10116135.7
       2898228.1     10116032.99       2898453.5     10115895.78
      2898531.35     10115898.43      2898763.35     10115994.01
      2899234.19     10115815.48      2899612.36     10115851.01
      2899802.37     10115700.38      2900003.48     10115623.76
       2900137.9     10115625.26      2900562.57     10115715.88
      2900703.26     10115764.09      2900818.39     10115843.91
      2900953.71     10115853.04      2901361.31      10115789.2
      2901560.07     10115606.15      2901759.47     10115506.15
      2901878.46     10115484.48      2902018.47     10115503.73

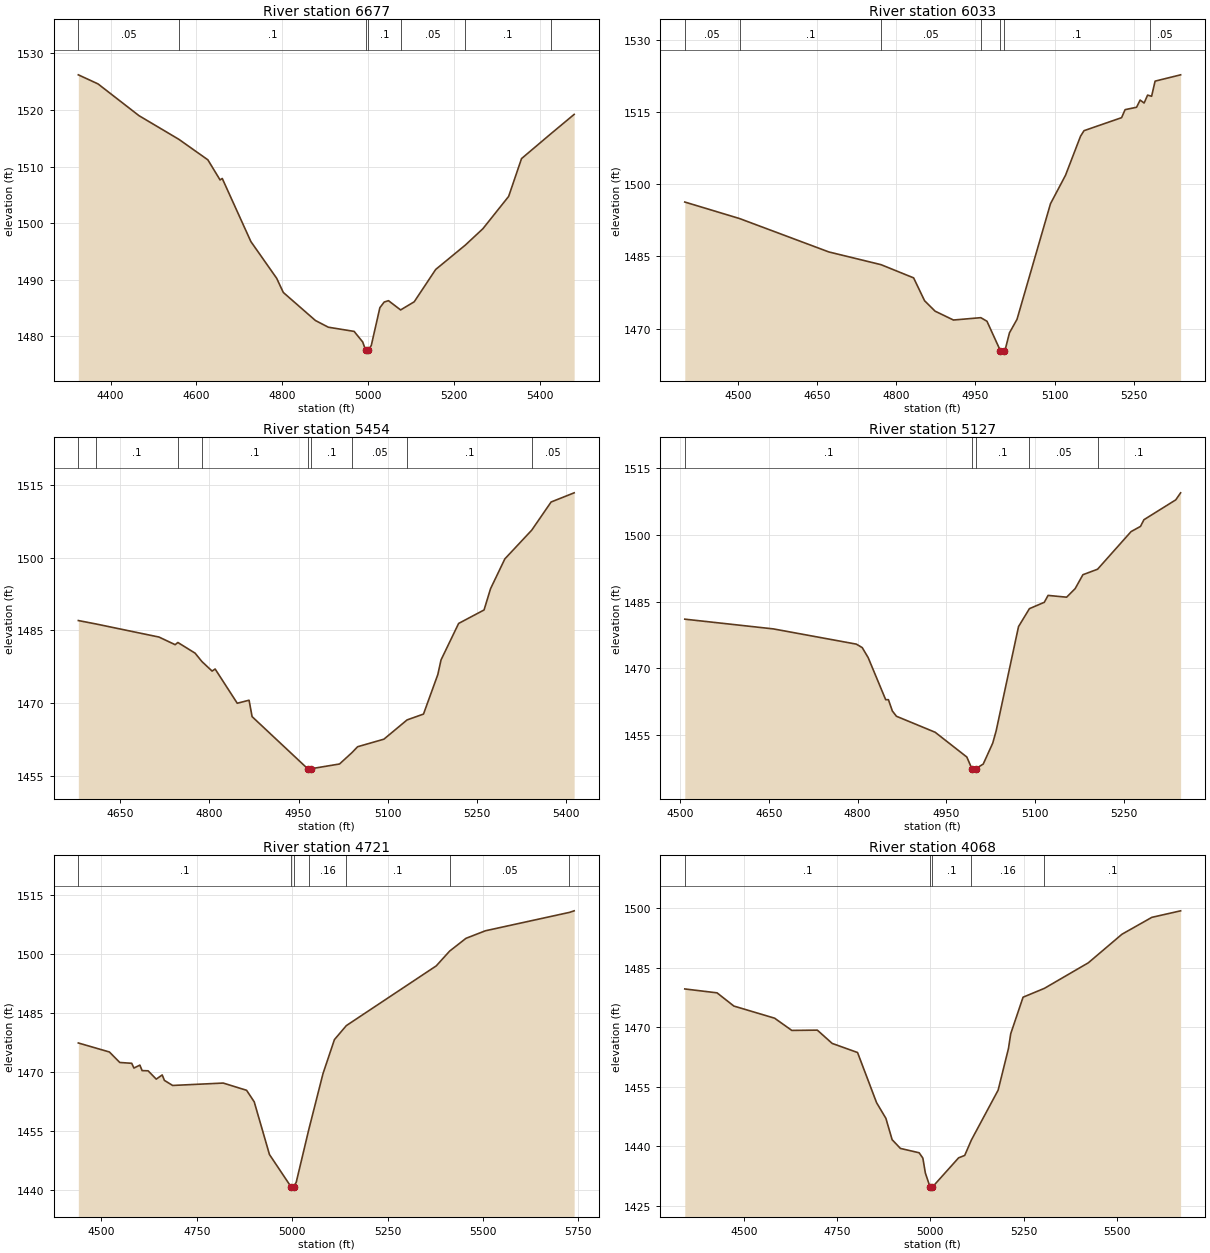
Type RM Length L Ch R = 1 ,6677    ,644,644,644
BEGIN DESCRIPTION:
UNT 1002 IN LATR 14.0
END DESCRIPTION:
XS GIS Cut Line= 3
      2896166.62     10117364.77      2896124.95     10116765.81
      2896119.75     10116211.14
#Sta/Elev= 30
    4325  1526.2  4370.8  1524.6  4466.4 1518.98  4559.1 1514.81  4626.8 1511.18
  4655.2 1507.63  4660.3 1507.89    4727 1496.74  4787.1 1490.25  4802.5 1487.75
  4877.4 1482.79  4907.4 1481.61  4967.5 1480.87  4987.5    1479  4994.5 1477.53
  4997.2 1477.03  5000.5 1477.53  5007.5 1478.39  5027.5 1485.06  5037.5 1486.05
  5047.5  1486.3  5075.8 1484.66  5107.5  1486.1  5157.5 1491.81  5226.6 1496.12
  5267.5 1499.01  5327.5 1504.72  5357.5  1511.4  5425.9 1515.79  5480.1 1519.21
#Mann= 7 ,-1 , 0
    4325     .05       0  4559.1      .1       0  4994.5     .07       0
  5000.5      .1       0  5075.8     .05       0  5226.6      .1       0
  5425.9     .05       0
Bank Sta=4994.5,5000.5
XS Rating Curve= 0 ,0
Exp/Cntr=0.3,0.1

Type RM Length L Ch R = 1 ,6033    ,579,579,579
BEGIN DESCRIPTION:
UNT 1002 IN LATR 13.0
END DESCRIPTION:
XS GIS Cut Line= 3
      2896752.57     10116909.06      2896614.54      10116450.7
      2896309.84     10116104.34
#Sta/Elev= 30
  4398.9 1496.28    4503 1492.84    4672 1485.92  4770.9 1483.28  4832.7 1480.54
  4853.5 1475.79  4873.4 1473.63  4908.2 1471.79  4960.1 1472.28  4971.8 1471.53
  4997.2 1465.42    5000 1464.92  5003.2 1465.42  5006.9 1465.89  5014.4 1469.13
  5028.7 1471.93  5092.2 1495.93  5120.7 1501.84  5149.2 1509.95  5155.8 1511.09
    5227 1513.79  5233.6 1515.45  5255.4 1515.95  5262.1 1517.44  5269.7 1516.83
  5276.3 1518.47  5280.1 1518.35  5283.9 1518.23  5290.5 1521.37  5338.9 1522.68
#Mann= 7 ,-1 , 0
  4398.9     .05       0    4503      .1       0  4770.9     .05       0
  4960.1      .1       0  4997.2     .07       0  5003.2      .1       0
  5280.1     .05       0
Bank Sta=4997.2,5003.2
XS Rating Curve= 0 ,0
Exp/Cntr=0.3,0.1

Type RM Length L Ch R = 1 ,5454    ,327,327,327
BEGIN DESCRIPTION:
UNT 1002 IN LATR 12.0
END DESCRIPTION:
XS GIS Cut Line= 3
      2897109.33     10116877.79       2897028.6     10116369.97
      2896908.82     10116073.12
#Sta/Elev= 30
  4579.4 1487.03  4609.7 1486.31  4715.1 1483.63  4742.3 1482.06  4746.9 1482.51
  4775.9 1480.31  4787.4 1478.58  4804.5 1476.62  4809.6 1477.05  4846.8    1470
  4866.7 1470.62  4871.8 1467.24  4965.3 1456.52    4968 1456.02  4971.3 1456.52
  5018.9 1457.49  5039.9 1459.84  5049.3 1461.04  5093.6  1462.6  5132.6 1466.57
  5160.2 1467.77  5184.3 1475.91  5189.7 1478.92  5219.3 1486.43  5262.1 1489.21
    5273 1493.58  5297.1 1499.73  5342.3 1505.64  5374.9 1511.44  5413.7 1513.33
#Mann= 9 ,-1 , 0
  4579.4     .05       0  4609.7      .1       0  4746.9     .05       0
  4787.4      .1       0  4965.3     .07       0  4971.3      .1       0
  5039.9     .05       0  5132.6      .1       0  5342.3     .05       0
Bank Sta=4965.3,4971.3
XS Rating Curve= 0 ,0
Exp/Cntr=0.3,0.1

Type RM Length L Ch R = 1 ,5127    ,406,406,406
BEGIN DESCRIPTION:
UNT 1002 IN LATR 11.0
END DESCRIPTION:
XS GIS Cut Line= 3
      2897330.68     10116703.35      2897330.68     10116359.56
      2897091.51       10115928.
#Sta/Elev= 30
  4508.2 1481.07  4657.8 1478.88  4797.8 1475.46  4807.8 1474.68  4817.8 1472.43
  4847.4 1462.97    4852 1462.97  4858.7 1460.42  4865.6 1459.24  4930.9 1455.65
  4984.4 1450.08  4993.1 1447.41  4995.9 1446.91  4999.1 1447.41  5012.1  1448.5
  5028.2 1453.22  5033.9 1455.95  5071.7  1479.4  5090.1 1483.43  5115.2 1484.86
  5121.6 1486.41  5152.9 1486.01  5167.3 1487.93  5180.4 1491.06  5205.2  1492.3
  5261.7 1500.75  5277.7 1501.93  5283.4 1503.42  5337.2 1507.89  5345.4 1509.47
#Mann= 5 ,-1 , 0
  4508.2      .1       0  4993.1     .07       0  4999.1      .1       0
  5090.1     .05       0  5205.2      .1       0
Bank Sta=4993.1,4999.1
XS Rating Curve= 0 ,0
Exp/Cntr=0.3,0.1

Type RM Length L Ch R = 1 ,4721    ,653,653,653
BEGIN DESCRIPTION:
UNT 1002 IN LATR 10.0
END DESCRIPTION:
XS GIS Cut Line= 4
      2897429.65     10116614.74      2897648.39     10116244.97
      2897632.77     10115911.64      2897330.67     10115468.91
#Sta/Elev= 30
  4439.7 1477.34  4521.1 1475.05  4548.3 1472.38  4579.6 1472.17  4585.4 1470.96
    4601 1471.71  4606.8 1470.31  4622.5 1470.26  4643.9 1468.14  4659.5 1469.21
  4665.3 1467.82  4686.8 1466.53  4819.4 1467.14  4880.6  1465.3  4900.6 1462.37
  4940.6 1448.95  4997.7 1440.65  5000.5 1440.15  5003.7 1440.65  5010.7  1441.9
  5043.4 1455.22  5080.8 1469.53  5110.8  1478.2    5142 1481.76  5377.6 1496.96
  5412.7 1500.72  5455.5 1503.97  5506.3 1505.89  5726.5 1510.57    5739 1510.97
#Mann= 7 ,-1 , 0
  4439.7      .1       0  4997.7     .07       0  5003.7      .1       0
  5043.4     .16       0    5142      .1       0  5412.7     .05       0
  5726.5      .1       0
Bank Sta=4997.7,5003.7
XS Rating Curve= 0 ,0
Exp/Cntr=0.3,0.1

Type RM Length L Ch R = 1 ,4068    ,394,394,394
BEGIN DESCRIPTION:
UNT 1002 IN LATR 9.0
END DESCRIPTION:
XS GIS Cut Line= 4
      2898476.52     10116630.39       2898341.1     10116130.39
      2898148.39     10115750.18      2898132.85     10115366.76
#Sta/Elev= 30
  4342.2  1479.6  4428.6 1478.62  4473.6 1475.29  4582.8 1472.23  4628.8 1469.15
  4697.2 1469.22    4737 1465.87  4804.9 1463.58  4855.9 1450.93  4880.8 1446.99
  4897.5 1441.61  4919.7 1439.41  4969.9 1438.31  4979.8 1436.97  4986.5 1433.21
  4999.2 1429.65    5002 1429.15  5005.2 1429.65  5075.6 1437.04  5091.9 1437.64
  5109.8 1441.53  5181.4 1454.09  5209.2 1464.63  5215.2 1468.33  5248.2 1477.52
  5305.3 1479.75    5423 1486.19  5513.1 1493.39  5593.2 1497.65  5670.2 1499.29
#Mann= 5 ,-1 , 0
  4342.2      .1       0  4999.2     .07       0  5005.2      .1       0
  5109.8     .16       0  5305.3      .1       0
Bank Sta=4999.2,5005.2
XS Rating Curve= 0 ,0
Exp/Cntr=0.3,0.1

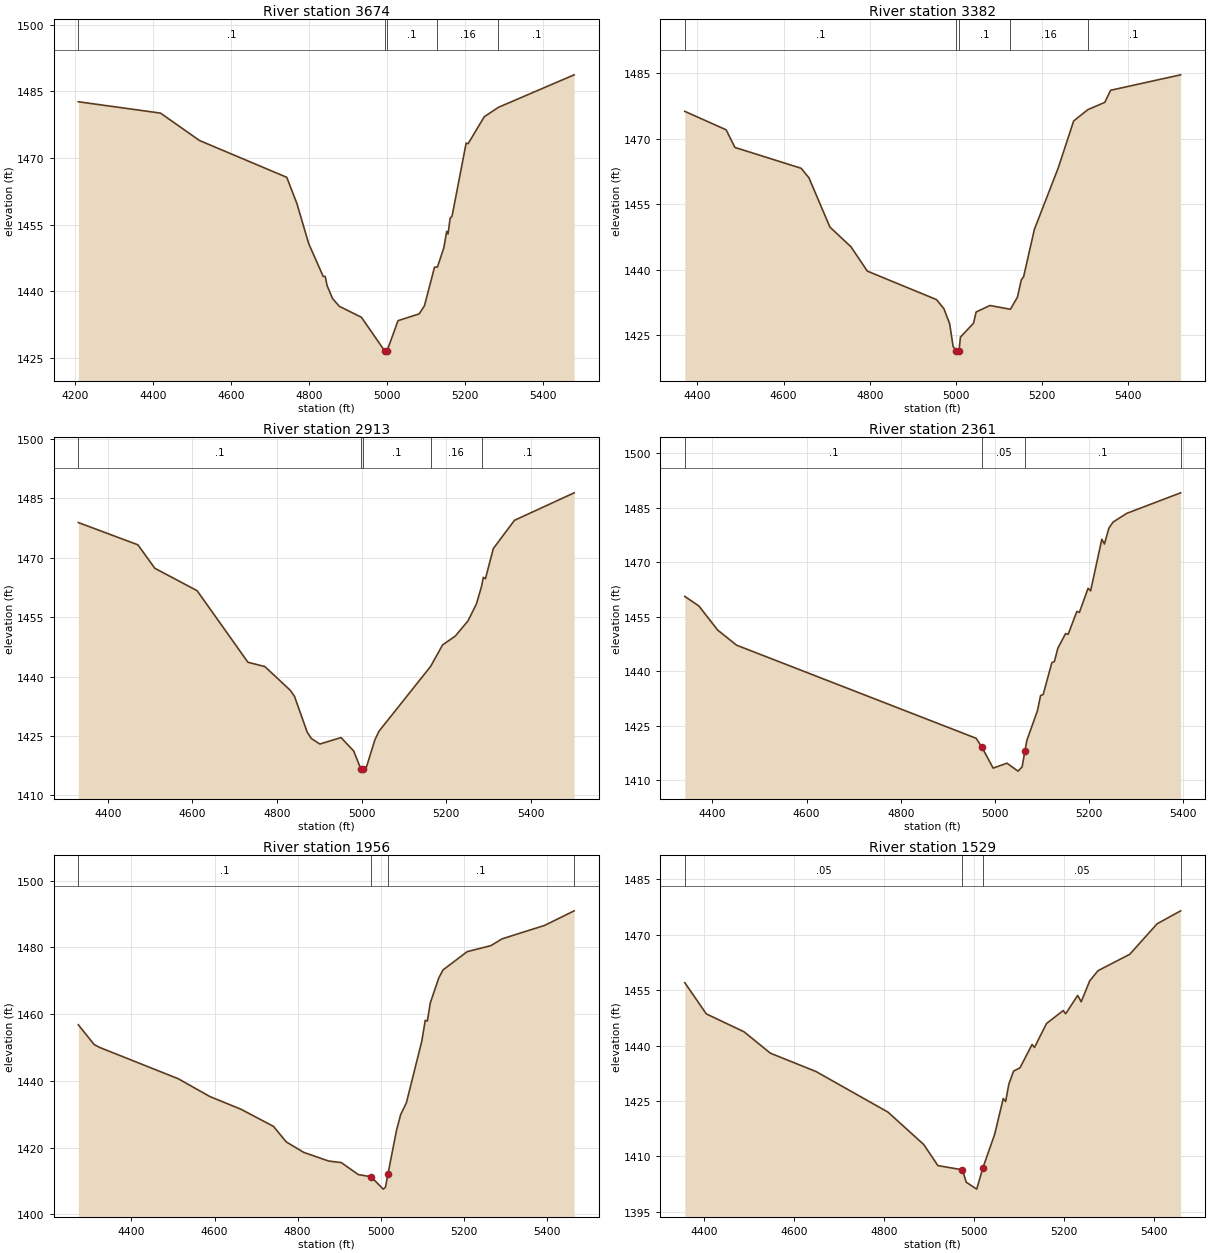
Type RM Length L Ch R = 1 ,3674    ,292,292,292
BEGIN DESCRIPTION:
UNT 1002 IN LATR 8.0
END DESCRIPTION:
XS GIS Cut Line= 4
       2898591.1     10116734.52      2898570.27     10116104.35
      2898674.43     10115802.26       2898596.3     10115489.73
#Sta/Elev= 30
  4208.8 1482.68  4419.7 1480.12  4519.8 1473.94  4743.7 1465.64  4769.9 1459.66
  4799.9  1450.7  4837.1  1443.3  4842.3  1443.3  4847.2 1441.21  4861.1 1438.32
  4878.4 1436.57  4935.2 1434.09  4994.9 1426.51  4997.7 1426.01  5000.9 1426.51
  5029.1 1433.33  5083.3 1434.86  5096.8 1436.67  5122.7 1445.38  5130.2 1445.42
  5146.7 1449.79  5153.9 1453.46  5157.4 1452.87  5162.7 1456.37  5167.8 1456.93
  5203.9 1473.36  5209.1 1473.25  5250.3  1479.3  5286.6 1481.42    5481 1488.75
#Mann= 5 ,-1 , 0
  4208.8      .1       0  4994.9     .07       0  5000.9      .1       0
  5130.2     .16       0  5286.6      .1       0
Bank Sta=4994.9,5000.9
XS Rating Curve= 0 ,0
Exp/Cntr=0.3,0.1

Type RM Length L Ch R = 1 ,3382    ,469,469,469
BEGIN DESCRIPTION:
UNT 1002 IN LATR 7.0
END DESCRIPTION:
XS GIS Cut Line= 3
      2898830.69     10116557.43      2898940.06     10116062.68
      2898716.15     10115458.64
#Sta/Elev= 30
  4370.6 1476.23  4466.6 1472.01    4487 1467.98  4640.7 1463.22  4658.7 1461.05
  4707.5 1449.77  4756.3 1445.27  4794.3 1439.71    4955 1433.19  4972.2 1431.08
  4985.4 1427.67  4993.5 1422.45  5001.1 1421.46  5003.9 1420.96  5007.1 1421.46
  5010.4 1424.62  5040.8  1427.8  5046.8 1430.36  5078.8 1431.85  5126.5 1430.99
  5142.8 1433.78  5151.7 1437.71    5157  1438.4    5182 1449.23  5237.5 1463.32
  5273.2 1474.03  5306.1 1476.62  5345.4 1478.28    5359 1481.05  5521.5 1484.58
#Mann= 5 ,-1 , 0
  4370.6      .1       0  5001.1     .07       0  5007.1      .1       0
  5126.5     .16       0  5306.1      .1       0
Bank Sta=5001.1,5007.1
XS Rating Curve= 0 ,0
Exp/Cntr=0.3,0.1

Type RM Length L Ch R = 1 ,2913    ,552,552,552
BEGIN DESCRIPTION:
UNT 1002 IN LATR 6.0
END DESCRIPTION:
XS GIS Cut Line= 2
      2899330.68     10116484.56      2899346.31     10115312.66
#Sta/Elev= 30
  4330.2 1478.92    4471 1473.29    4511 1467.36    4611 1461.69  4731.1  1443.6
  4771.1 1442.51  4831.1 1436.52  4841.1    1435  4871.1 1425.96  4881.1 1424.31
  4901.1 1422.93  4951.1 1424.56  4981.1 1421.17  4998.1 1416.58  5000.8 1416.08
  5004.1 1416.58  5011.1 1417.06  5031.1 1423.97  5041.1  1426.2  5162.9 1442.55
  5191.1 1447.97  5221.1 1450.21  5251.1 1454.04  5271.1 1458.32  5283.3 1462.78
  5287.5 1465.08  5292.5 1464.71  5311.1 1472.34  5361.1 1479.48  5502.2 1486.43
#Mann= 5 ,-1 , 0
  4330.2      .1       0  4998.1     .07       0  5004.1      .1       0
  5162.9     .16       0  5283.3      .1       0
Bank Sta=4998.1,5004.1
XS Rating Curve= 0 ,0
Exp/Cntr=0.3,0.1

Type RM Length L Ch R = 1 ,2361    ,405,405,405
BEGIN DESCRIPTION:
UNT 1002 IN LATR 5.0
END DESCRIPTION:
XS GIS Cut Line= 3
      2899914.01     10116333.48      2899887.98      10115823.1
      2899679.64     10115323.11
#Sta/Elev= 30
  4341.5 1460.56  4371.3 1457.94  4411.3  1451.3  4451.4 1447.14  4960.2 1421.51
  4972.4 1419.03  4996.2 1413.31  5025.4 1414.67    5049 1412.48  5057.7 1413.64
 5063.86 1418.15  5067.7 1420.92  5090.2  1429.1  5096.9 1433.29  5102.4 1433.56
  5120.8 1442.33  5126.2 1442.62  5133.5  1446.3    5150 1450.33  5155.4 1450.12
  5173.9 1456.43  5179.3 1456.16  5197.7  1462.8  5203.1 1462.09  5226.9 1476.29
  5232.4 1474.97  5241.9 1479.34  5250.8 1481.01    5280 1483.42  5394.2 1489.06
#Mann= 4 ,-1 , 0
  4341.5      .1       0  4972.4     .05       0 5063.86      .1       0
  5394.2      .1       0
Bank Sta=4972.4,5063.86
XS Rating Curve= 0 ,0
Exp/Cntr=0.3,0.1

Type RM Length L Ch R = 1 ,1956    ,427,427,427
BEGIN DESCRIPTION:
UNT 1002 IN LATR 4.0
END DESCRIPTION:
XS GIS Cut Line= 3
      2900075.48     10116354.35      2900268.18     10115411.64
      2900231.72     10115182.42
#Sta/Elev= 30
    4272 1456.81  4310.1  1450.9  4323.7 1450.01  4512.1 1440.68    4589 1435.31
  4663.5 1431.53  4742.1 1426.38  4772.8 1421.73  4814.9 1418.59  4874.8    1416
  4905.4 1415.53  4946.3 1411.94  4976.9  1411.3  5006.4 1407.58  5011.8 1408.14
  5017.7 1412.04  5038.1 1425.02  5048.3 1429.86  5062.3 1433.48  5099.4 1451.96
  5107.6 1458.15  5112.7 1457.93  5119.8 1463.37  5140.2 1470.85  5150.4 1473.24
  5208.6 1478.72  5265.9 1480.53  5292.8 1482.56  5395.3 1486.59  5466.3 1490.95
#Mann= 4 ,-1 , 0
    4272      .1       0  4976.9     .05       0  5017.7      .1       0
  5466.3      .1       0
Bank Sta=4976.9,5017.7
XS Rating Curve= 0 ,0
Exp/Cntr=0.3,0.1

Type RM Length L Ch R = 1 ,1529    ,502,502,502
BEGIN DESCRIPTION:
UNT 1002 IN LATR 3.0
END DESCRIPTION:
XS GIS Cut Line= 3
      2900434.84     10116349.17      2900705.68      10115510.6
      2900674.43     10115291.85
#Sta/Elev= 30
  4357.5 1457.01  4405.3 1448.57  4489.3 1443.72  4547.7 1437.94    4649 1432.99
  4809.2 1421.99  4888.7 1413.23  4920.2 1407.52  4974.6 1406.39  4983.2 1403.02
  5006.4 1401.16 5020.11 1406.91  5046.3 1415.98  5065.4 1425.68  5070.7 1424.87
  5077.8 1429.54  5088.3 1433.08  5102.7 1433.99  5129.5  1440.3  5134.8 1439.48
  5161.5 1445.95  5198.8 1449.48  5204.1  1448.6  5230.8 1453.56  5238.7 1451.84
  5257.6  1457.5    5276 1460.25  5346.7  1464.7  5407.3 1472.93  5459.7 1476.45
#Mann= 4 ,-1 , 0
  4357.5     .05       0  4974.6    .035       0 5020.11     .05       0
  5459.7      .1       0
Bank Sta=4974.6,5020.11
XS Rating Curve= 0 ,0
Exp/Cntr=0.3,0.1

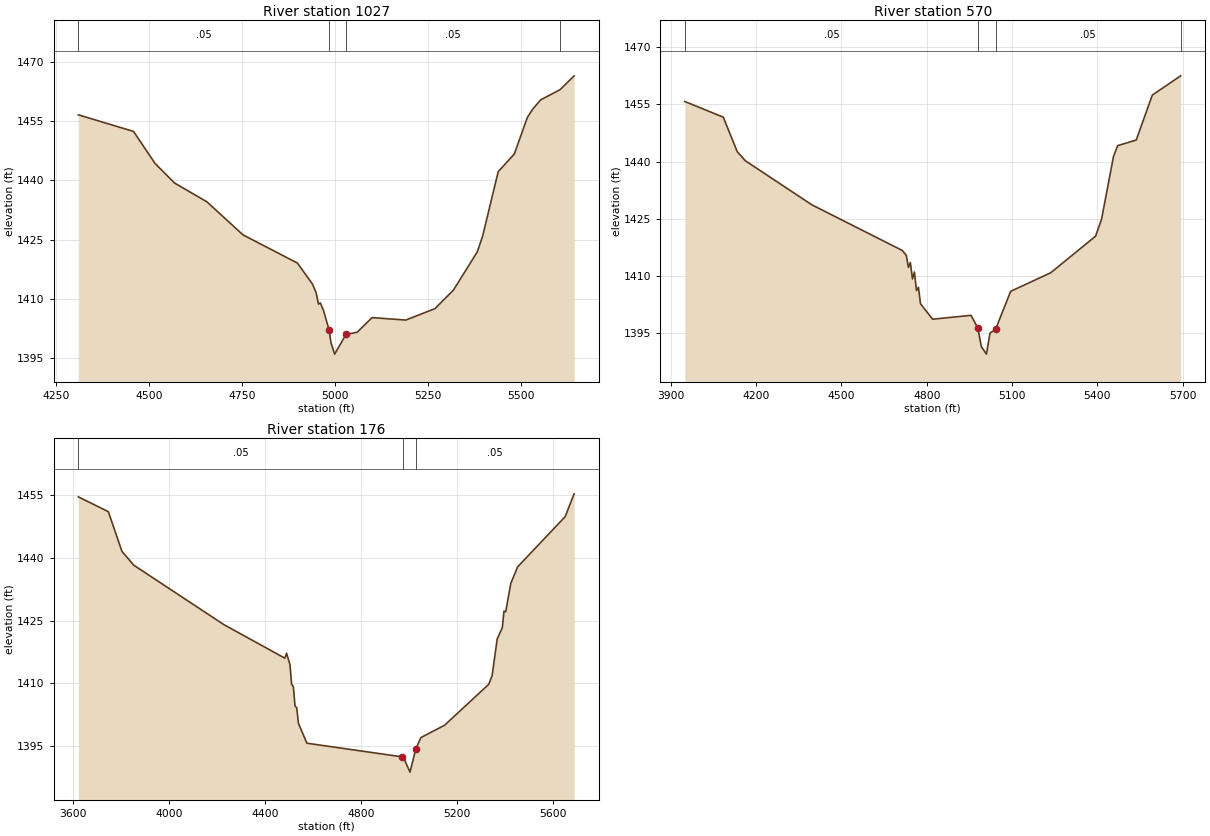
Type RM Length L Ch R = 1 ,1027    ,457,457,457
BEGIN DESCRIPTION:
UNT 1002 IN LATR 2.0
END DESCRIPTION:
XS GIS Cut Line= 4
      2900846.33     10116453.26      2901111.93     10115979.35
      2901085.89     10115661.64      2900794.23     10115291.86
#Sta/Elev= 30
  4310.5 1456.59    4459 1452.38  4516.3 1444.33  4569.2 1439.31    4656 1434.56
    4753 1426.19  4899.5 1419.03  4939.7 1413.76  4949.7 1411.57  4956.1 1408.63
  4961.1 1408.95  4969.8 1406.97 4984.55 1402.12  4989.8 1398.83  4999.6 1395.96
    5030 1400.95  5060.1 1401.51  5100.2 1405.21  5190.8 1404.59  5269.4  1407.5
  5319.1  1412.2  5383.2 1421.89  5397.6 1425.91  5439.3 1442.19  5482.6 1446.66
  5517.8 1455.95  5532.3 1458.05  5553.1 1460.36  5605.7 1462.97  5643.5 1466.47
#Mann= 4 ,-1 , 0
  4310.5     .05       0 4984.55    .035       0    5030     .05       0
  5605.7     .05       0
Bank Sta=4984.55,5030
XS Rating Curve= 0 ,0
Exp/Cntr=0.3,0.1

Type RM Length L Ch R = 1 ,570     ,394,394,394
BEGIN DESCRIPTION:
Mapping XS ba5a3e0a
END DESCRIPTION:
XS GIS Cut Line= 4
      2900883.26      10116459.8        2901530.     10115746.24
      2901448.86     10115521.92      2901004.98      10115209.3
#Sta/Elev= 30
  3948.9 1455.76  4084.3 1451.65  4133.6 1442.57    4162 1440.21  4395.8 1428.65
  4714.1 1416.66  4728.3 1415.36  4735.8  1412.2  4742.5  1413.5    4750 1409.17
  4756.7 1411.01  4764.2 1406.13  4770.9 1406.99  4778.3 1402.66  4820.8 1398.62
  4956.2 1399.63    4980 1396.26  4992.2 1391.45  5010.1 1389.45  5022.8 1394.97
  5042.2 1395.94  5095.4 1405.93  5236.6 1410.82  5394.3 1420.42  5415.2 1424.86
  5457.1 1441.29  5471.9 1444.18  5537.2 1445.65  5593.8 1457.44  5693.4  1462.5
#Mann= 4 ,-1 , 0
  3948.9     .05       0    4980    .035       0  5042.2     .05       0
  5693.4      .1       0
Bank Sta=4980,5042.2
XS Rating Curve= 0 ,0
Exp/Cntr=0.3,0.1

Type RM Length L Ch R = 1 ,176     ,0,0,0
BEGIN DESCRIPTION:
UNT 1002 IN LATR 1.0
END DESCRIPTION:
XS GIS Cut Line= 4
       2900914.3     10116476.49      2901856.94     10115533.85
      2901823.53     10115409.76      2901384.46     10114994.56
#Sta/Elev= 30
  3622.2 1454.52  3747.3 1450.98  3803.9 1441.51  3853.4  1438.2  4228.1 1424.04
  4482.7 1416.01  4489.8  1417.2  4503.9 1414.49    4511 1409.76  4518.1 1409.22
  4525.1 1404.59  4532.2 1404.18  4539.3 1400.46  4574.6 1395.71  4969.8 1392.47
  4976.1 1392.42  5004.3 1388.81  5027.9  1394.3  5049.7 1397.06  5148.1    1400
  5332.2 1409.77  5346.3 1411.86  5367.4 1420.58  5388.8 1423.31  5395.7 1427.24
    5403 1427.09    5424 1433.84  5452.3 1437.79  5650.5 1449.78  5688.1 1455.24
#Mann= 3 ,-1 , 0
  3622.2     .05       0  4976.1    .035       0  5027.9     .05       0
Bank Sta=4969.8,5027.9
XS Rating Curve= 0 ,0
Exp/Cntr=0.3,0.1

Chan Stop Cuts=-1
Use User Specified Reach Order=0
Composite Channel Slope=5