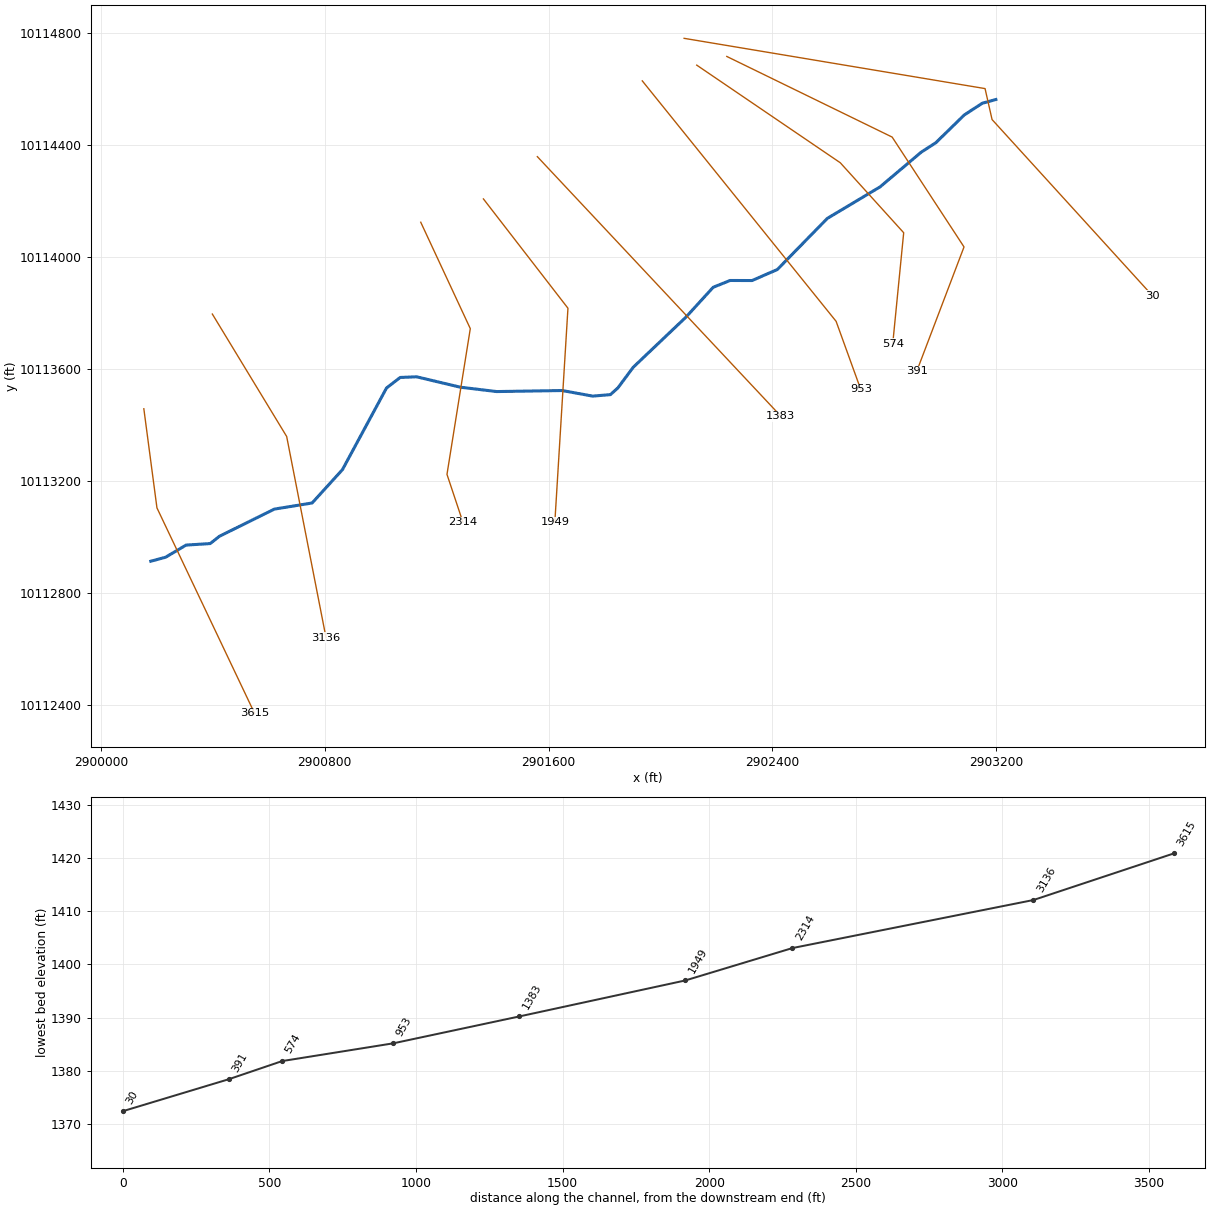
--- UNT 0003 IN LATR.prj (project) ---

Proj Title=UNT 1003 IN LATR Base Level Engineering
Current Plan=p01
Default Exp/Contr=0.3,0.1
English Units
Geom File=g01
Flow File=f01
Plan File=p01
BEGIN DESCRIPTION:
UNT 1003 IN LATR
END DESCRIPTION:

--- UNT 0003 IN LATR.p01 (plan) ---

Plan Title=Multiple Run
Short Identifier=Multiple
Geom File=g01
Flow File=f01
Subcritical Flow
K Sum by GR= 0
Std Step Tol= 0.01
Critical Tol= 0.01
Num of Std Step Trials= 20
Max Error Tol= 0.3
Flow Tol Ratio= 0.001
Split Flow NTrial= 30
Split Flow Tol= 0.02
Split Flow Ratio= 0.02
Log Output Level= 0
Friction Slope Method= 1
Unsteady Friction Slope Method= 2
Unsteady Bridges Friction Slope Method= 1
Parabolic Critical Depth
Global Vel Dist=  1 , 1 , 1
Global Log Level= 0
CheckData=True
Encroach Param= -1, 0, 0, 0
BEGIN DESCRIPTION:
Multiple Run
END DESCRIPTION:

--- UNT 0003 IN LATR.f01 (steady flow) ---

Flow Title=Multiple
Number of Profiles=7
Profile Names=10-year,25-year,50-year,1pct_min,100-year,1pct_plu,500-year
River Rch & RM= UNT 1003 IN LATR,Reach-1,3615
    1109    1638    2105    1980    2677    3621    4349
Boundary for River Rch & Prof#=UNT 1003 IN LATR,Reach-1,1
Up Type=0
Dn Type=3
Dn Slope=0.005
Boundary for River Rch & Prof#=UNT 1003 IN LATR,Reach-1,2
Up Type=0
Dn Type=3
Dn Slope=0.005
Boundary for River Rch & Prof#=UNT 1003 IN LATR,Reach-1,3
Up Type=0
Dn Type=3
Dn Slope=0.005
Boundary for River Rch & Prof#=UNT 1003 IN LATR,Reach-1,4
Up Type=0
Dn Type=3
Dn Slope=0.005
Boundary for River Rch & Prof#=UNT 1003 IN LATR,Reach-1,5
Up Type=0
Dn Type=3
Dn Slope=0.005
Boundary for River Rch & Prof#=UNT 1003 IN LATR,Reach-1,6
Up Type=0
Dn Type=3
Dn Slope=0.005
Boundary for River Rch & Prof#=UNT 1003 IN LATR,Reach-1,7
Up Type=0
Dn Type=3
Dn Slope=0.005

--- UNT 0003 IN LATR.g01 (geometry) ---

Geom Title=Existing Conditions

River Reach=UNT 1003 IN LATR,Reach-1
Reach XY= 30
      2900178.47     10112913.73      2900231.39     10112928.05
      2900304.47     10112971.38      2900390.80     10112976.82
      2900423.82     10113002.91      2900620.03     10113099.96
      2900755.02     10113121.89      2900863.43     10113241.10
      2901020.90     10113532.88      2901069.79     10113570.48
      2901128.48     10113572.79      2901284.30     10113535.72
      2901414.63     10113520.03      2901648.47     10113523.74
      2901757.62     10113503.81      2901821.01     10113509.07
      2901848.00     10113533.51      2901902.28     10113606.65
      2902090.74     10113785.86      2902188.23     10113892.69
      2902248.72     10113917.00      2902327.12     10113916.79
      2902417.47     10113956.14      2902595.98     10114138.75
      2902784.72     10114251.58      2902931.80     10114375.71
      2902983.56     10114408.99      2903085.64     10114508.58
      2903149.95     10114550.40      2903198.47     10114563.73

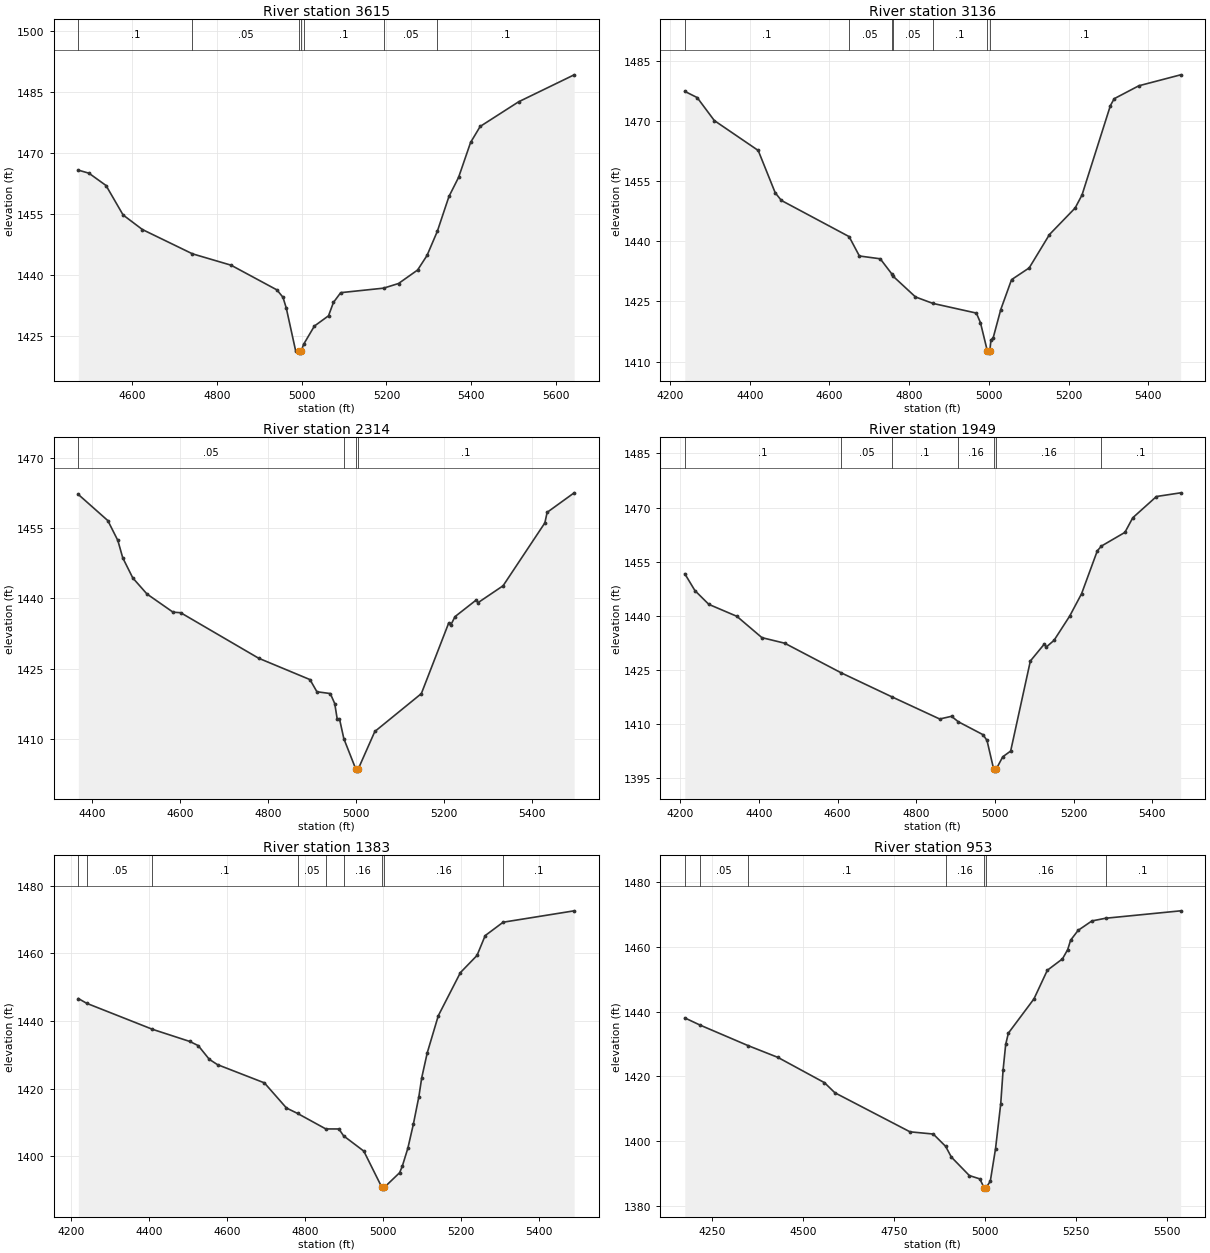
Type RM Length L Ch R = 1,3615,479,479,479
BEGIN DESCRIPTION:
UNT 1003 IN LATR 8.0
END DESCRIPTION:
XS GIS Cut Line= 3
      2900153.60     10113458.53      2900200.48     10113104.35
      2900549.42     10112370.01
#Sta/Elev= 30
  4472.7 1465.90  4497.7 1465.15  4538.1 1462.12  4578.4 1454.87  4624.0 1451.29
  4742.1 1445.32  4833.1 1442.53  4941.4 1436.45  4955.7 1434.64  4963.5 1431.99
  4985.7 1421.44  4992.6 1421.40  4995.4 1420.90  4998.6 1421.40  5004.5 1423.08
  5029.9 1427.56  5063.2 1430.08  5074.9 1433.38  5092.0 1435.77  5193.3 1436.88
  5228.4 1438.02  5273.5 1441.34  5295.7 1444.91  5320.0 1450.85  5347.5 1459.43
  5370.2 1464.12  5398.5 1472.70  5421.2 1476.65  5512.1 1482.72  5643.0 1489.34
#Mann=7,-1,0
  4472.7     0.1       0  4742.1    0.05       0  4992.6   0.035       0
  4998.6    0.05       0  5004.5     0.1       0  5193.3    0.05       0
  5320.0     0.1       0
Bank Sta=4992.6,4998.6
Exp/Cntr=0.3,0.1

Type RM Length L Ch R = 1,3136,822,822,822
BEGIN DESCRIPTION:
UNT 1003 IN LATR 7.0
END DESCRIPTION:
XS GIS Cut Line= 3
      2900398.39     10113797.05      2900664.02     10113359.56
      2900804.64     10112640.80
#Sta/Elev= 30
  4237.0 1477.37  4268.1 1475.82  4311.1 1470.09  4421.2 1462.64  4463.9 1452.09
  4479.4 1450.18  4649.3 1441.17  4675.1 1436.34  4727.4 1435.64  4755.7 1431.97
  4760.0 1431.27  4815.9 1426.13  4859.3 1424.53  4968.7 1422.11  4978.9 1419.72
  4996.3 1412.63  4999.1 1412.13  5002.3 1412.63  5005.4 1415.45  5010.5 1415.82
  5029.9 1423.00  5056.9 1430.44  5101.2 1433.37  5152.1 1441.69  5216.5 1448.30
  5233.7 1451.53  5305.0 1473.83  5314.5 1475.54  5376.3 1478.76  5481.2 1481.49
#Mann=7,-1,0
  4237.0     0.1       0  4649.3    0.05       0  4755.7     0.1       0
  4760.0    0.05       0  4859.3     0.1       0  4996.3    0.07       0
  5002.3     0.1       0
Bank Sta=4996.3,5002.3
Exp/Cntr=0.3,0.1

Type RM Length L Ch R = 1,2314,365,365,365
BEGIN DESCRIPTION:
UNT 1003 IN LATR 6.0
END DESCRIPTION:
XS GIS Cut Line= 4
      2901143.20     10114125.15      2901320.27     10113744.97
      2901236.93     10113224.14      2901293.84     10113053.42
#Sta/Elev= 30
  4368.4 1462.21  4435.4 1456.63  4458.2 1452.38  4469.3 1448.68  4492.1 1444.38
  4524.4 1440.94  4583.6 1437.06  4601.0 1436.94  4778.1 1427.22  4894.8 1422.65
  4910.6 1420.05  4941.0 1419.67  4951.1 1417.52  4956.8 1414.18  4961.9 1414.26
  4971.8 1410.02  4998.7 1403.59  5001.5 1403.09  5004.7 1403.59  5042.2 1411.56
  5147.9 1419.65  5210.0 1434.72  5215.0 1434.35  5224.5 1436.11  5272.0 1439.61
  5277.1 1439.11  5333.7 1442.70  5428.6 1456.13  5433.8 1458.39  5495.2 1462.56
#Mann=4,-1,0
  4368.4    0.05       0  4971.8     0.1       0  4998.7    0.07       0
  5004.7     0.1       0
Bank Sta=4998.7,5004.7
Exp/Cntr=0.3,0.1

Type RM Length L Ch R = 1,1949,566,566,566
BEGIN DESCRIPTION:
UNT 1003 IN LATR 4.0
END DESCRIPTION:
XS GIS Cut Line= 3
      2901367.15     10114208.50      2901669.23     10113817.89
      2901622.35     10113052.31
#Sta/Elev= 30
  4211.3 1451.68  4237.1 1447.01  4272.4 1443.20  4343.7 1439.89  4407.4 1433.98
  4465.3 1432.44  4609.2 1424.22  4738.5 1417.55  4859.5 1411.44  4889.6 1412.19
  4906.6 1410.69  4969.7 1407.09  4979.8 1405.49  4996.8 1397.50  4999.5 1397.00
  5002.8 1397.50  5019.8 1400.97  5039.9 1402.56  5090.0 1427.51  5125.8 1432.25
  5130.8 1431.41  5150.1 1433.22  5190.1 1439.97  5220.2 1446.14  5260.3 1458.04
  5270.7 1459.35  5330.4 1463.14  5350.4 1467.19  5410.6 1473.08  5472.1 1474.10
#Mann=7,-1,0
  4211.3     0.1       0  4609.2    0.05       0  4738.5     0.1       0
  4906.6    0.16       0  4996.8    0.07       0  5002.8    0.16       0
  5270.7     0.1       0
Bank Sta=4996.8,5002.8
Exp/Cntr=0.3,0.1

Type RM Length L Ch R = 1,1383,430,430,430
BEGIN DESCRIPTION:
UNT 1003 IN LATR 3.0
END DESCRIPTION:
XS GIS Cut Line= 2
      2901559.88     10114359.53      2902429.65     10113432.46
#Sta/Elev= 30
  4218.7 1446.62  4240.3 1445.20  4408.7 1437.52  4504.7 1433.91  4526.2 1432.68
  4554.5 1428.63  4575.5 1427.06  4695.7 1421.67  4752.3 1414.23  4780.7 1412.63
  4853.2 1408.04  4886.7 1408.03  4898.8 1405.99  4950.6 1401.48  4997.0 1390.73
  4999.7 1390.23  5003.0 1390.73  5042.5 1395.10  5049.4 1397.06  5063.5 1402.32
  5077.6 1409.41  5091.8 1417.61  5099.1 1423.18  5113.3 1430.58  5141.6 1441.54
  5198.3 1454.30  5240.8 1459.36  5261.8 1465.24  5307.8 1469.20  5489.9 1472.57
#Mann=9,-1,0
  4218.7     0.1       0  4240.3    0.05       0  4408.7     0.1       0
  4780.7    0.05       0  4853.2     0.1       0  4898.8    0.16       0
  4997.0    0.07       0  5003.0    0.16       0  5307.8     0.1       0
Bank Sta=4997,5003
Exp/Cntr=0.3,0.1

Type RM Length L Ch R = 1,953,379,379,379
BEGIN DESCRIPTION:
UNT 1003 IN LATR 2.0
END DESCRIPTION:
XS GIS Cut Line= 3
      2901934.85     10114630.39      2902627.56     10113771.01
      2902715.65     10113527.46
#Sta/Elev= 30
  4174.7 1438.04  4217.0 1435.81  4349.0 1429.47  4430.6 1425.85  4558.5 1418.05
  4587.3 1414.92  4793.6 1402.87  4857.6 1402.18  4891.7 1398.37  4907.2 1395.09
  4956.8 1389.36  4985.6 1388.33  4997.0 1385.67  4999.7 1385.17  5003.0 1385.67
  5014.4 1387.63  5028.8 1397.68  5043.1 1411.58  5049.6 1422.01  5056.7 1429.86
  5064.0 1433.33  5134.4 1443.92  5171.1 1452.75  5212.7 1456.27  5227.1 1459.13
  5235.1 1462.04  5255.9 1465.09  5293.7 1467.99  5331.3 1468.82  5537.5 1471.11
#Mann=7,-1,0
  4174.7     0.1       0  4217.0    0.05       0  4349.0     0.1       0
  4891.7    0.16       0  4997.0    0.07       0  5003.0    0.16       0
  5331.3     0.1       0
Bank Sta=4997,5003
Exp/Cntr=0.3,0.1

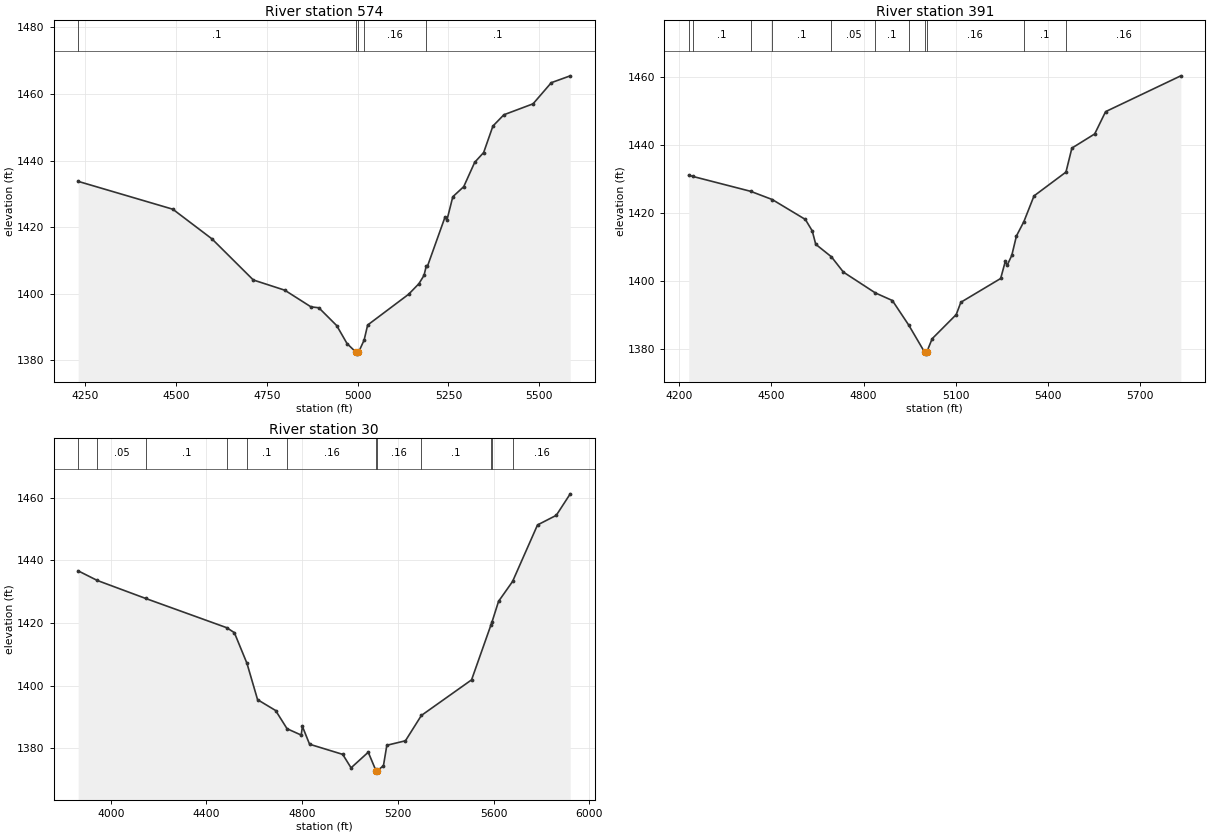
Type RM Length L Ch R = 1,574,183,183,183
BEGIN DESCRIPTION:
Mapping XS 2fc04c19
END DESCRIPTION:
XS GIS Cut Line= 4
      2902129.50     10114686.60      2902642.50     10114337.66
      2902869.06     10114087.66      2902830.00     10113691.80
#Sta/Elev= 30
  4229.8 1433.74  4490.6 1425.37  4598.4 1416.46  4712.3 1404.11  4799.0 1401.04
  4871.2 1396.03  4892.8 1395.76  4942.1 1390.40  4970.5 1385.01  4995.9 1382.33
  4998.7 1381.83  5001.9 1382.33  5017.6 1386.05  5027.3 1390.57  5140.1 1399.81
  5168.5 1402.99  5182.7 1405.51  5188.6 1408.25  5192.1 1408.25  5240.7 1423.09
  5245.7 1422.10  5261.9 1429.12  5292.0 1432.15  5322.2 1439.46  5346.9 1442.41
  5372.4 1450.36  5402.6 1453.75  5483.0 1457.04  5533.2 1463.39  5585.4 1465.45
#Mann=5,-1,0
  4229.8     0.1       0  4995.9    0.07       0  5001.9     0.1       0
  5017.6    0.16       0  5188.6     0.1       0
Bank Sta=4995.9,5001.9
Exp/Cntr=0.3,0.1

Type RM Length L Ch R = 1,391,361,361,361
BEGIN DESCRIPTION:
Mapping XS 85c7dca6
END DESCRIPTION:
XS GIS Cut Line= 4
      2902236.87     10114717.63      2902827.81     10114429.47
      2903084.65     10114036.91      2902915.52     10113592.16
#Sta/Elev= 30
  4230.5 1431.10  4244.1 1430.69  4432.3 1426.31  4502.4 1423.90  4610.4 1418.03
  4632.8 1414.66  4644.1 1410.73  4695.2 1407.04  4734.2 1402.54  4838.5 1396.40
  4893.6 1394.18  4946.9 1386.95  4999.1 1378.90  5001.9 1378.40  5005.1 1378.90
  5023.2 1382.93  5101.6 1390.04  5116.7 1393.66  5246.3 1400.66  5261.4 1405.69
  5267.4 1404.54  5282.5 1407.45  5297.6 1413.16  5322.0 1417.42  5354.9 1424.96
  5458.9 1431.97  5478.2 1439.03  5552.5 1443.20  5588.0 1449.76  5832.9 1460.30
#Mann=11,-1,0
  4230.5    0.05       0  4244.1     0.1       0  4432.3    0.05       0
  4502.4     0.1       0  4695.2    0.05       0  4838.5     0.1       0
  4946.9    0.16       0  4999.1    0.07       0  5005.1    0.16       0
  5322.0     0.1       0  5458.9    0.16       0
Bank Sta=4999.1,5005.1
Exp/Cntr=0.3,0.1

Type RM Length L Ch R = 1,30,0,0,0
BEGIN DESCRIPTION:
UNT 1003 IN LATR 1.0
END DESCRIPTION:
XS GIS Cut Line= 4
      2902084.45     10114782.36      2903159.82     10114602.78
      2903184.88     10114492.11      2903759.10     10113861.51
#Sta/Elev= 30
  3863.8 1436.68  3944.1 1433.60  4146.5 1427.85  4485.1 1418.51  4516.7 1416.93
  4569.4 1407.12  4613.7 1395.53  4689.1 1392.07  4736.9 1386.25  4796.0 1384.23
  4801.1 1386.98  4831.0 1381.30  4969.5 1378.06  5004.4 1373.76  5076.2 1378.75
  5108.3 1372.89  5111.1 1372.39  5114.3 1372.89  5139.7 1374.42  5153.9 1380.97
  5231.6 1382.40  5298.2 1390.49  5508.0 1401.86  5588.7 1419.33  5593.4 1420.34
  5620.8 1426.94  5679.3 1433.28  5783.6 1451.34  5862.0 1454.41  5920.4 1461.28
#Mann=12,-1,0
  3863.8     0.1       0  3944.1    0.05       0  4146.5     0.1       0
  4485.1    0.05       0  4569.4     0.1       0  4736.9    0.16       0
  5108.3    0.07       0  5114.3    0.16       0  5298.2     0.1       0
  5588.7    0.16       0  5593.4     0.1       0  5679.3    0.16       0
Bank Sta=5108.3,5114.3
Exp/Cntr=0.3,0.1

Chan Stop Cuts=-1