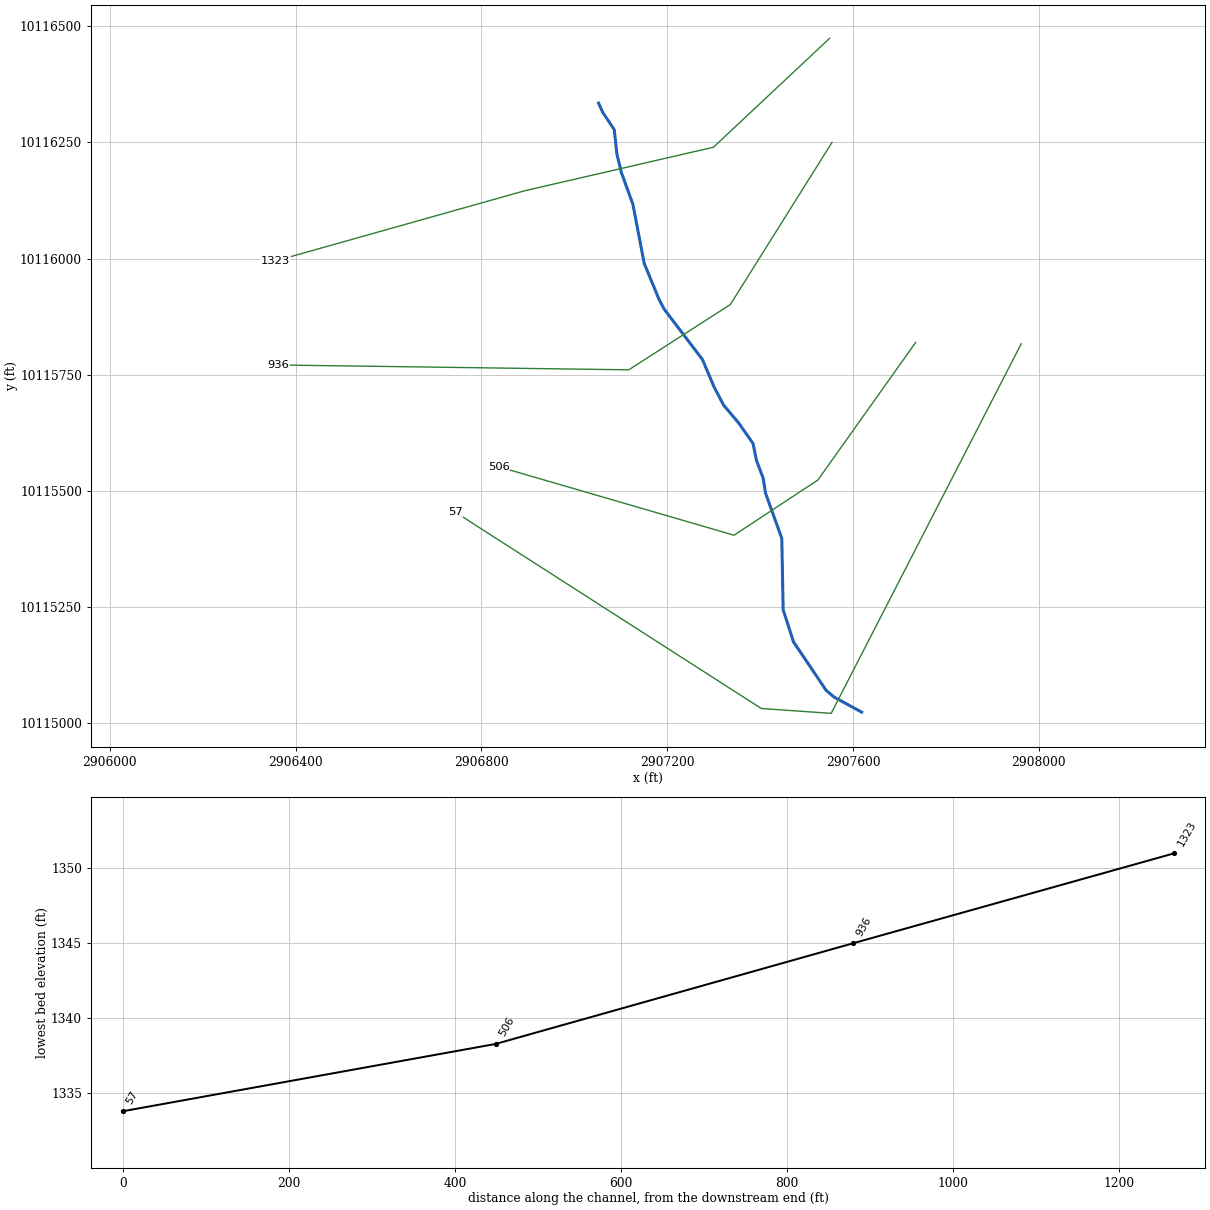
--- UNT 0004 IN LATR.prj (project) ---

Proj Title=UNT 1004 IN LATR Base Level Engineering
Current Plan=p01
Default Exp/Contr=0.3,0.1
English Units
Geom File=g01
Flow File=f01
Plan File=p01
BEGIN DESCRIPTION:
UNT 1004 IN LATR
END DESCRIPTION:

--- UNT 0004 IN LATR.p01 (plan) ---

Plan Title=Multiple Run
Short Identifier=Multiple
Geom File=g01
Flow File=f01
Subcritical Flow
K Sum by GR= 0
Std Step Tol= 0.01
Critical Tol= 0.01
Num of Std Step Trials= 20
Max Error Tol= 0.3
Flow Tol Ratio= 0.001
Split Flow NTrial= 30
Split Flow Tol= 0.02
Split Flow Ratio= 0.02
Log Output Level= 0
Friction Slope Method= 1
Unsteady Friction Slope Method= 2
Unsteady Bridges Friction Slope Method= 1
Parabolic Critical Depth
Global Vel Dist=  1 , 1 , 1
Global Log Level= 0
CheckData=True
Encroach Param= -1, 0, 0, 0
BEGIN DESCRIPTION:
Multiple Run
END DESCRIPTION:

--- UNT 0004 IN LATR.f01 (steady flow) ---

Flow Title=Multiple
Number of Profiles=7
Profile Names=10-year,25-year,50-year,1pct_min,100-year,1pct_plu,500-year
River Rch & RM= UNT 1004 IN LATR,Reach-1,1323
     958    1408    1805    1695    2292    3100    3710
Boundary for River Rch & Prof#=UNT 1004 IN LATR,Reach-1,1
Up Type=0
Dn Type=3
Dn Slope=0.005
Boundary for River Rch & Prof#=UNT 1004 IN LATR,Reach-1,2
Up Type=0
Dn Type=3
Dn Slope=0.005
Boundary for River Rch & Prof#=UNT 1004 IN LATR,Reach-1,3
Up Type=0
Dn Type=3
Dn Slope=0.005
Boundary for River Rch & Prof#=UNT 1004 IN LATR,Reach-1,4
Up Type=0
Dn Type=3
Dn Slope=0.005
Boundary for River Rch & Prof#=UNT 1004 IN LATR,Reach-1,5
Up Type=0
Dn Type=3
Dn Slope=0.005
Boundary for River Rch & Prof#=UNT 1004 IN LATR,Reach-1,6
Up Type=0
Dn Type=3
Dn Slope=0.005
Boundary for River Rch & Prof#=UNT 1004 IN LATR,Reach-1,7
Up Type=0
Dn Type=3
Dn Slope=0.005

--- UNT 0004 IN LATR.g01 (geometry) ---

Geom Title=Existing Conditions

River Reach=UNT 1004 IN LATR,Reach-1
Reach XY= 23
      2907051.98     10116334.82      2907061.02     10116314.89
      2907085.85     10116277.69      2907091.59     10116225.01
      2907101.37     10116184.87      2907126.04     10116116.83
      2907150.45     10115989.56      2907182.91     10115910.86
      2907193.47     10115891.09      2907275.81     10115782.63
      2907300.40     10115724.53      2907321.08     10115684.82
      2907353.53     10115646.40      2907384.59     10115602.13
      2907392.10     10115565.24      2907406.31     10115527.84
      2907411.59     10115495.03      2907446.51     10115397.92
      2907449.49     10115244.16      2907471.69     10115175.07
      2907542.07     10115070.56      2907559.24     10115056.05
      2907618.47     10115023.73

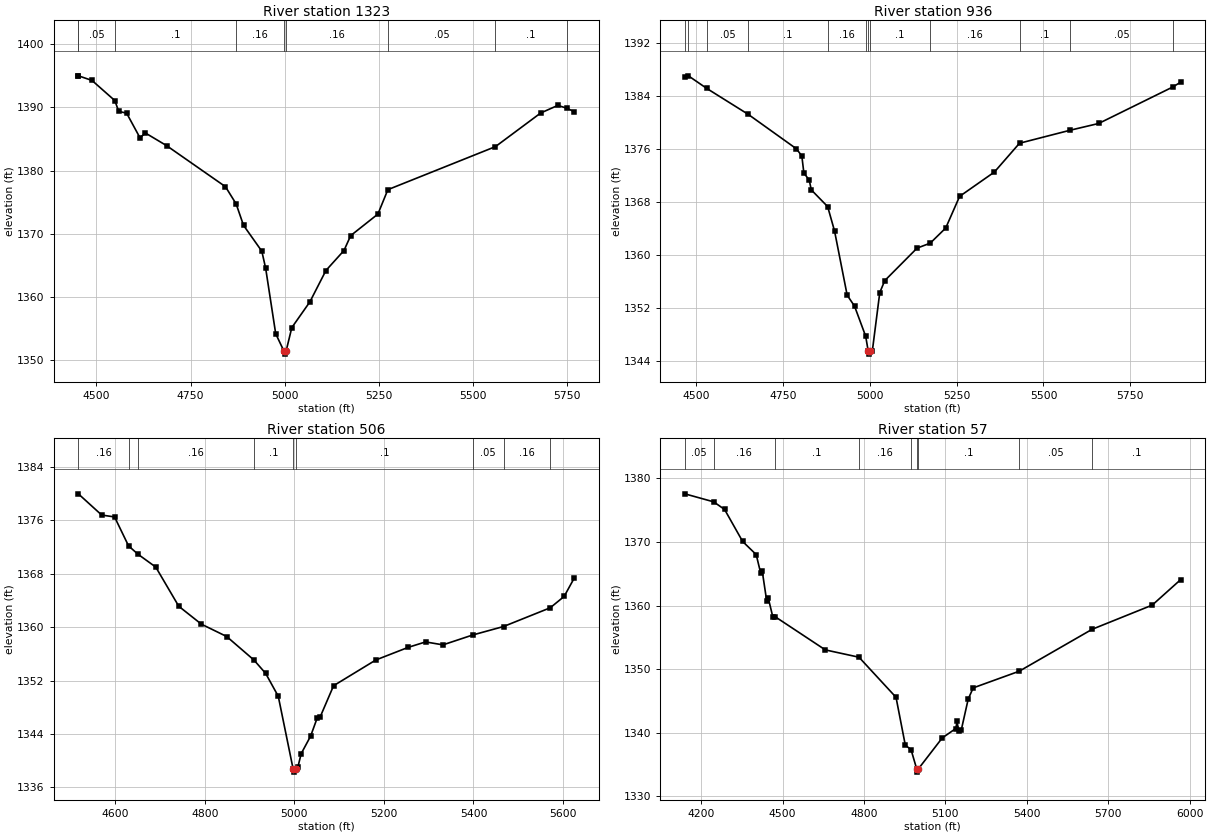
Type RM Length L Ch R = 1,1323,387,387,387
BEGIN DESCRIPTION:
UNT 1004 IN LATR 3.0
END DESCRIPTION:
XS GIS Cut Line= 4
      2907549.42     10116474.12      2907299.43     10116239.76
      2906893.18     10116146.01      2906356.73     10115994.97
#Sta/Elev= 30
  4451.9 1394.98  4452.2 1394.98  4488.2 1394.25  4548.9 1391.06  4559.1 1389.35
  4580.1 1389.08  4615.7 1385.17  4629.9 1385.94  4686.2 1383.94  4842.7 1377.44
  4871.0 1374.72  4890.6 1371.33  4939.2 1367.24  4949.5 1364.51  4976.1 1354.18
  4997.8 1351.45  5000.6 1350.95  5003.8 1351.45  5018.9 1355.15  5066.8 1359.21
  5109.5 1364.18  5157.4 1367.34  5175.3 1369.70  5247.6 1373.11  5274.0 1376.97
  5559.8 1383.78  5679.9 1389.10  5725.4 1390.30  5749.7 1389.85  5768.8 1389.30
#Mann=9,-1,0
  4451.9     0.1       0  4452.2    0.05       0  4548.9     0.1       0
  4871.0    0.16       0  4997.8    0.07       0  5003.8    0.16       0
  5274.0    0.05       0  5559.8     0.1       0  5749.7    0.05       0
Bank Sta=4997.8,5003.8
Exp/Cntr=0.3,0.1

Type RM Length L Ch R = 1,936,430,430,430
BEGIN DESCRIPTION:
UNT 1004 IN LATR 2.0
END DESCRIPTION:
XS GIS Cut Line= 4
      2907554.65     10116250.20      2907335.89     10115901.22
      2907117.14     10115760.60      2906362.74     10115771.00
#Sta/Elev= 30
  4468.2 1386.83  4478.5 1387.08  4531.2 1385.18  4650.4 1381.26  4789.5 1376.03
  4804.9 1374.95  4810.8 1372.35  4826.1 1371.33  4832.0 1369.83  4879.2 1367.29
  4899.0 1363.60  4935.3 1353.89  4956.5 1352.23  4988.6 1347.67  4995.7 1345.47
  4998.5 1344.97  5001.7 1345.47  5007.8 1345.49  5029.1 1354.28  5043.4 1356.09
  5136.4 1361.01  5174.2 1361.76  5218.8 1364.05  5258.8 1368.84  5358.8 1372.52
  5431.1 1376.88  5576.9 1378.85  5658.8 1379.87  5872.4 1385.40  5894.6 1386.12
#Mann=12,-1,0
  4468.2    0.05       0  4478.5     0.1       0  4531.2    0.05       0
  4650.4     0.1       0  4879.2    0.16       0  4988.6     0.1       0
  4995.7    0.07       0  5001.7     0.1       0  5174.2    0.16       0
  5431.1     0.1       0  5576.9    0.05       0  5872.4     0.1       0
Bank Sta=4995.7,5001.7
Exp/Cntr=0.3,0.1

Type RM Length L Ch R = 1,506,449,449,449
BEGIN DESCRIPTION:
Mapping XS 0cf44248
END DESCRIPTION:
XS GIS Cut Line= 4
      2907734.79     10115819.69      2907524.25     10115523.43
      2907343.78     10115404.61      2906836.99     10115551.99
#Sta/Elev= 30
  4517.6 1379.97  4569.8 1376.79  4598.5 1376.51  4629.8 1372.17  4650.9 1370.92
  4690.5 1369.00  4741.9 1363.13  4792.4 1360.45  4848.9 1358.60  4909.6 1355.09
  4935.9 1353.08  4964.1 1349.65  4997.2 1338.79  5000.0 1338.29  5003.2 1338.79
  5007.7 1338.99  5015.3 1341.06  5036.4 1343.69  5051.4 1346.47  5057.4 1346.51
  5087.6 1351.23  5182.1 1355.09  5254.4 1356.98  5293.1 1357.79  5331.9 1357.35
  5398.4 1358.83  5467.3 1360.10  5571.4 1362.90  5602.5 1364.60  5624.9 1367.33
#Mann=9,-1,0
  4517.6    0.16       0  4629.8     0.1       0  4650.9    0.16       0
  4909.6     0.1       0  4997.2    0.07       0  5003.2     0.1       0
  5398.4    0.05       0  5467.3    0.16       0  5571.4    0.05       0
Bank Sta=4997.2,5003.2
Exp/Cntr=0.3,0.1

Type RM Length L Ch R = 1,57,0,0,0
BEGIN DESCRIPTION:
UNT 1004 IN LATR 1.0
END DESCRIPTION:
XS GIS Cut Line= 4
      2907961.88     10115816.66      2907552.82     10115021.11
      2907402.43     10115031.64      2906743.74     10115454.22
#Sta/Elev= 30
  4139.2 1377.56  4245.7 1376.30  4285.9 1375.10  4352.5 1370.07  4402.4 1368.01
  4419.0 1365.09  4424.6 1365.44  4441.2 1360.71  4446.8 1361.20  4463.4 1358.26
  4471.8 1358.26  4657.3 1353.03  4781.4 1351.88  4917.9 1345.58  4952.1 1338.06
  4973.2 1337.36  4994.1 1334.32  4996.8 1333.82  5000.1 1334.32  5088.2 1339.19
  5138.1 1340.67  5143.1 1341.81  5148.4 1340.21  5158.4 1340.43  5184.0 1345.30
  5202.3 1347.06  5372.1 1349.68  5640.9 1356.27  5862.4 1360.07  5967.1 1364.07
#Mann=9,-1,0
  4139.2    0.05       0  4245.7    0.16       0  4471.8     0.1       0
  4781.4    0.16       0  4973.2     0.1       0  4994.1    0.07       0
  5000.1     0.1       0  5372.1    0.05       0  5640.9     0.1       0
Bank Sta=4994.1,5000.1
Exp/Cntr=0.3,0.1

Chan Stop Cuts=-1