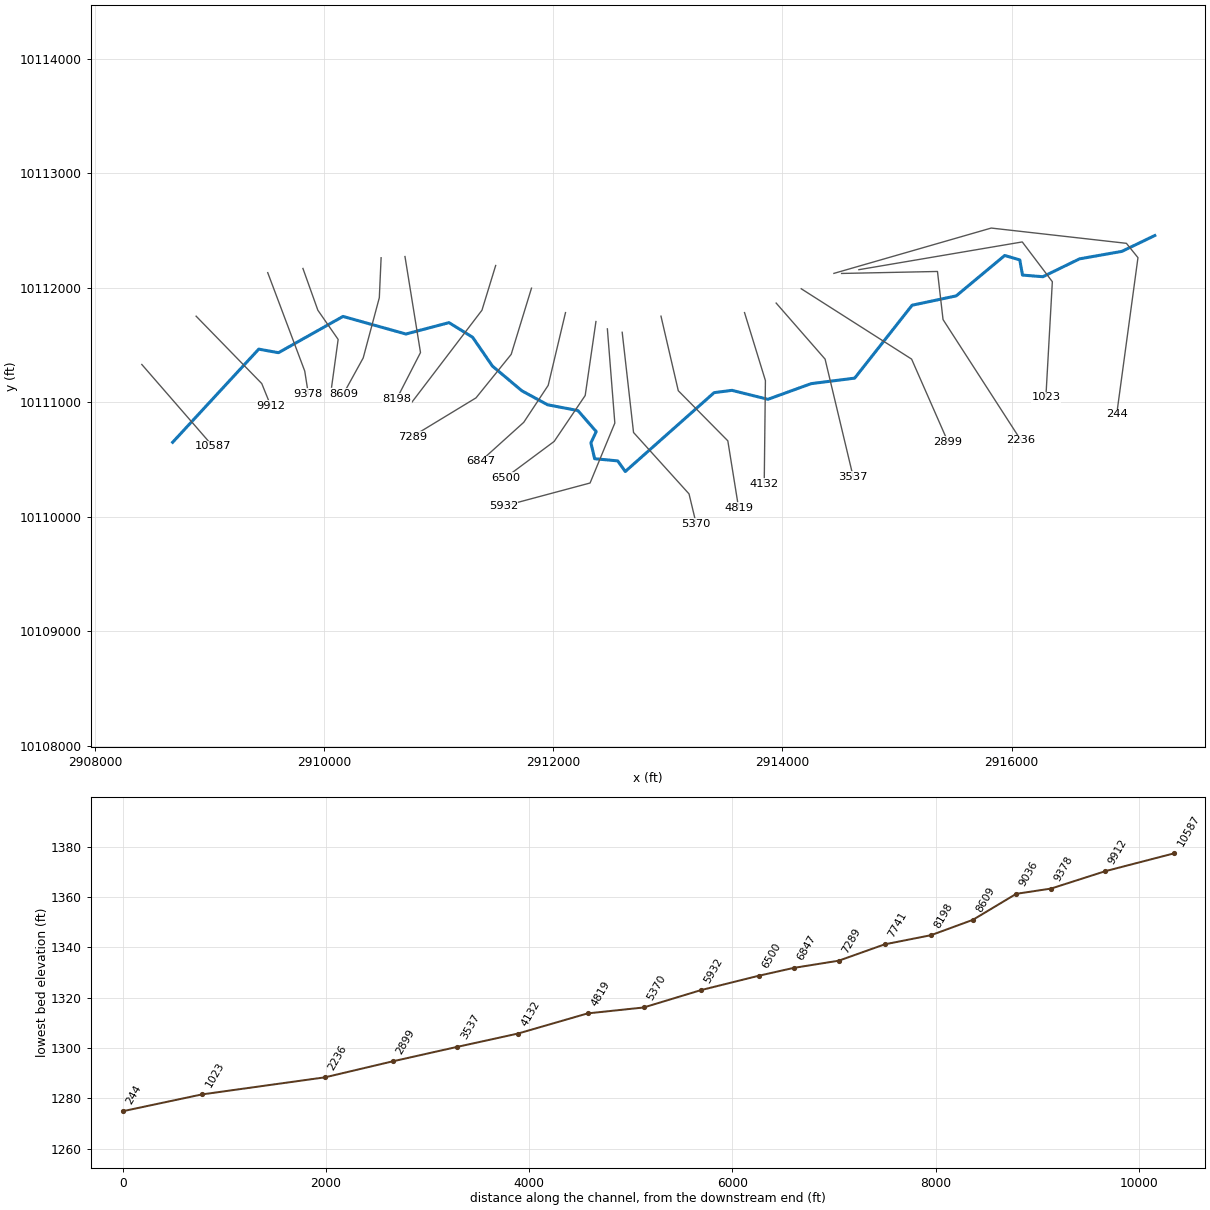
--- UNT 0005 IN LATR.prj (project) ---

Proj Title=UNT 1005 IN LATR Base Level Engineering
Current Plan=p01
Default Exp/Contr=0.3,0.1
English Units
Geom File=g01
Flow File=f01
Plan File=p01
Y Axis Title=Elevation
X Axis Title(PF)=Main Channel Distance
X Axis Title(XS)=Station
BEGIN DESCRIPTION:
UNT 1005 IN LATR
END DESCRIPTION:
DSS File=dss
DSS Export Rating Curves= 0
DSS Export Rating Curve Sorted= 0
DSS Export Volume Flow Curves= 0
DXF OffsetX= 0
DXF OffsetY= 0
DXF ScaleX= 1
DXF ScaleY= 10

--- UNT 0005 IN LATR.p01 (plan) ---

Plan Title=Multiple Run
Program Version=4.10
Short Identifier=Multiple Run
Geom File=g01
Flow File=f01
Subcritical Flow
K Sum by GR= 0
Std Step Tol= 0.01
Critical Tol= 0.01
Num of Std Step Trials= 20
Max Error Tol= 0.3
Flow Tol Ratio= 0.001
Split Flow NTrial= 30
Split Flow Tol= 0.02
Split Flow Ratio= 0.02
Log Output Level= 0
Friction Slope Method= 1
Unsteady Friction Slope Method= 2
Unsteady Bridges Friction Slope Method= 1
Parabolic Critical Depth
Global Vel Dist= 1 , 1 , 1
Global Log Level= 0
CheckData=True
Encroach Param=-1 ,0,0, 0
BEGIN DESCRIPTION:
Multiple Run
END DESCRIPTION:
Computation Interval=1HOUR
Output Interval=1HOUR
Run HTab= 0
Run UNet= 0
Run PostProcess= 0
Run WQNet= 0
UNET Theta= 1
UNET Theta Warmup= 1
UNET ZTol= 0.02
UNET ZSATol= 0.05
UNET MxIter= 20
UNET MaxInSteps= 0
UNET DtIC= 0
UNET DtMin= 0
UNET MaxCRTS= 20
UNET WFStab= 2
UNET SFStab= 1
UNET WFX= 1
UNET SFX= 1
UNET DSS MLevel= 4
UNET DZMax Abort= 100
UNET Convert EG Bridges= 0
UNET Use Existing IB Tables=-1
UNET Froude Reduction=False
UNET Froude Limit= 1
UNET Froude Power= 10
UNET Time Slicing=0,0, 5
UNET Junction Losses=0
Instantaneous Interval=1HOUR
DSS File=dss
Write IC File= 0
Write IC File at Sim End=0
Echo Input=False
Echo Parameters=False
Echo Output=False
Write Detailed= 0
WQ AD Non Conservative
WQ ULTIMATE=-1
WQ Max Comp Step=1HOUR
WQ Output Interval=15MIN
WQ Output Selected Increments= 0
WQ Output face flow=0
WQ Output face velocity=0
WQ Output face area=0
WQ Output face dispersion=0
WQ Output cell volume=0
WQ Output cell surface area=0
WQ Output cell continuity=0
WQ Output cumulative cell continuity=0
WQ Output face conc=0
WQ Output face dconc_dx=0
WQ Output face courant=0
WQ Output face peclet=0
WQ Output face adv mass=0
WQ Output face disp mass=0
WQ Output cell mass=0
WQ Output cell source sink temp=0
WQ Output cell source sink nsm=0
WQ Output MaxMinRange=-1
WQ Daily Max Min Mean=-1
WQ Daily Range=0
WQ Daily Time=0
WQ Create Restart=0
WQ Fixed Restart=0
WQ System Summary=0
WQ Use Fixed Temperature=0
Sorting and Armoring Iterations= 10
XS Update Threshold= 0.02
Hydraulics Update Threshold= 0.02
Energy Slope Method= 1
Volume Change Method= 0
XS Weighting Method= 0
Number of US Weighted Cross Sections= 1
Number of DS Weighted Cross Sections= 1
Upstream XS Weight=0.25
Main XS Weight=0.5
Downstream XS Weight=0.25
Number of DS XS's Weighted with US Boundary= 1
Upstream Boundary Weight= 1
Weight of XSs Associated with US Boundary= 0
Number of US XS's Weighted with DS Boundary= 1
Downstream Boundary Weight= 0.5
Weight of XSs Associated with DS Boundary= 0.5
Sediment Output Level= 4
Mass or Volume Output= 0
Output Increment Type= 1
Profile and TS Output Increment= 10
XS Output Flag= 0
XS Output Increment= 10
Disregard all LS=0
Disregard all Conn=0
Disregard all Breaches=0
Disregard all Pumps=0

--- UNT 0005 IN LATR.f01 (steady flow) ---

Flow Title=Multiple
Number of Profiles=7
Profile Names=10-year,25-year,50-year,1pct_min,100-year,1pct_plu,500-year
River Rch & RM= UNT 1005 IN LATR,Reach-1,10587
     946    1394    1789    1683    2276    3078    3697
River Rch & RM= UNT 1005 IN LATR,Reach-1,9378
    1567    2367    3088    2946    3984    5388    6665
River Rch & RM= UNT 1005 IN LATR,Reach-1,5370
    1649    2485    3238    3082    4168    5636    6940
Boundary for River Rch & Prof#=UNT 1005 IN LATR,Reach-1,1
Up Type=0
Dn Type=3
Dn Slope=0.005
Boundary for River Rch & Prof#=UNT 1005 IN LATR,Reach-1,2
Up Type=0
Dn Type=3
Dn Slope=0.005
Boundary for River Rch & Prof#=UNT 1005 IN LATR,Reach-1,3
Up Type=0
Dn Type=3
Dn Slope=0.005
Boundary for River Rch & Prof#=UNT 1005 IN LATR,Reach-1,4
Up Type=0
Dn Type=3
Dn Slope=0.005
Boundary for River Rch & Prof#=UNT 1005 IN LATR,Reach-1,5
Up Type=0
Dn Type=3
Dn Slope=0.005
Boundary for River Rch & Prof#=UNT 1005 IN LATR,Reach-1,6
Up Type=0
Dn Type=3
Dn Slope=0.005
Boundary for River Rch & Prof#=UNT 1005 IN LATR,Reach-1,7
Up Type=0
Dn Type=3
Dn Slope=0.005

--- UNT 0005 IN LATR.g01 (geometry) ---

Geom Title=Existing Conditions
Program Version=4.10

River Reach=UNT 1005 IN LATR,Reach-1
Reach XY= 30
      2908677.91     10110648.76      2909429.21     10111462.33
       2909601.6     10111431.32      2910164.62     10111748.01
      2910713.78     10111594.35       2911089.8     10111693.75
      2911295.85     10111566.26      2911469.15      10111314.1
       2911725.8     10111098.67      2911949.64     10110976.58
      2912215.25     10110925.86      2912374.75     10110742.29
      2912328.41     10110643.68      2912361.09     10110505.28
      2912562.01     10110486.43      2912628.47     10110393.73
      2913403.92     10111082.44      2913559.08     10111102.52
      2913873.85     10111024.35      2914249.68      10111160.8
       2914630.7     10111209.19      2915131.74     10111845.78
      2915516.82     10111927.43      2915940.03     10112280.21
      2916071.43     10112241.75      2916095.36     10112109.02
      2916273.37     10112094.81      2916592.84     10112250.79
      2916962.65     10112316.12      2917249.75     10112454.43

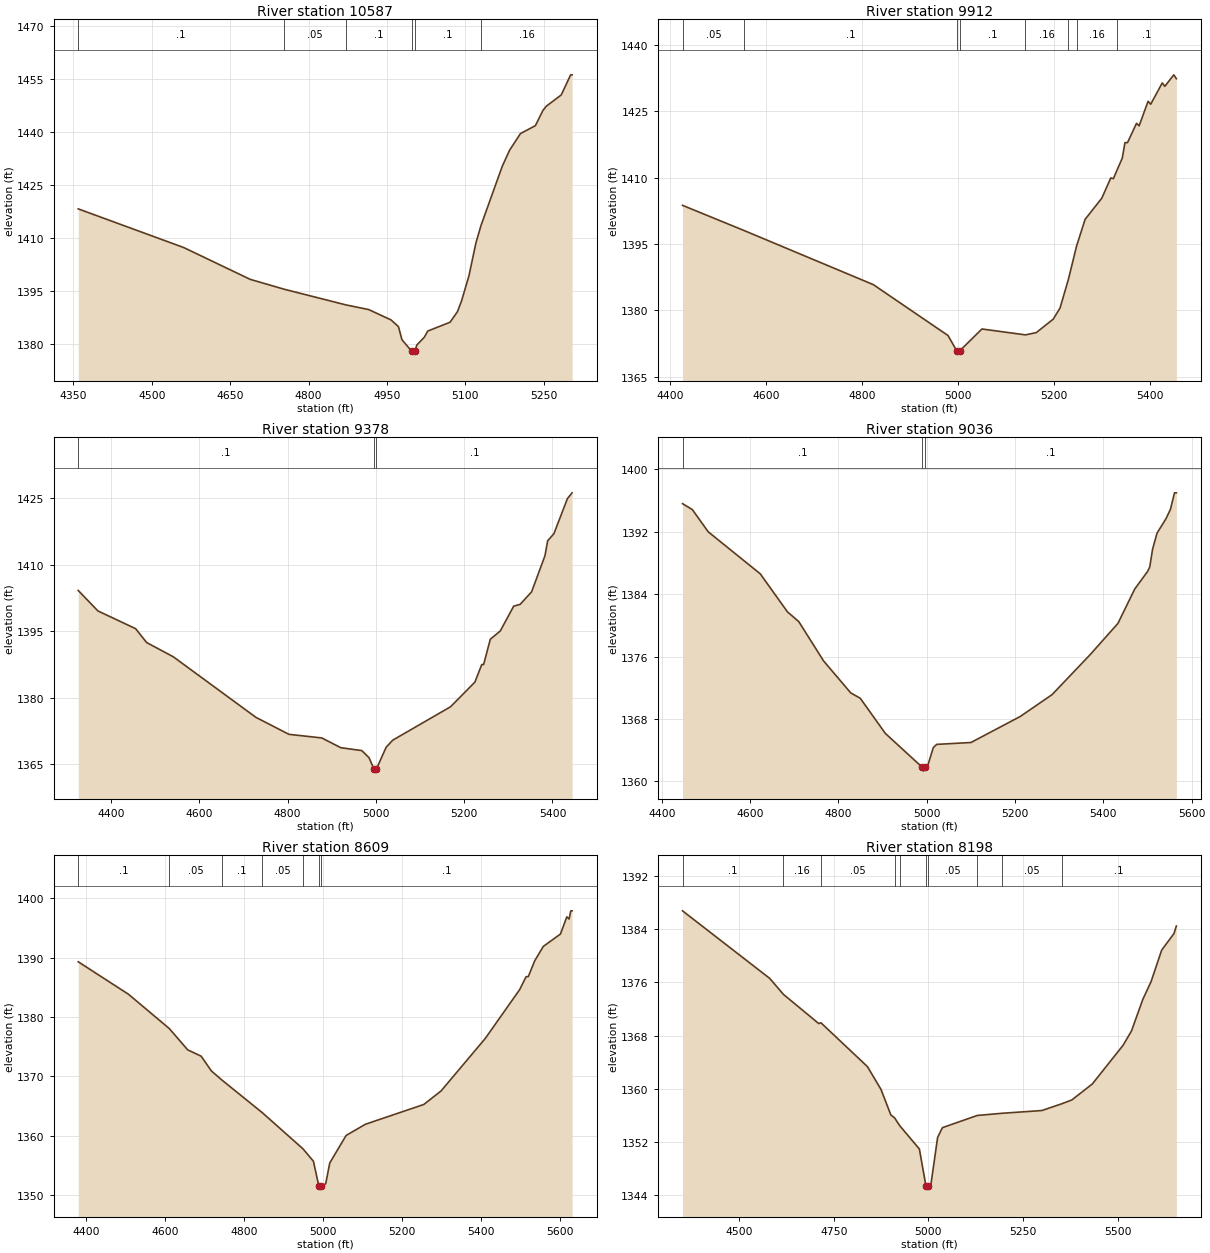
Type RM Length L Ch R = 1 ,10587   ,675,675,675
BEGIN DESCRIPTION:
UNT 1005 IN LATR 18.0
END DESCRIPTION:
XS GIS Cut Line= 2
      2908408.79     10111328.33      2909028.62     10110614.74
#Sta/Elev= 30
  4359.1 1418.21  4560.9 1407.27  4688.1 1398.27  4753.4 1395.46  4871.5 1391.03
    4915 1389.71  4957.8 1386.78    4972 1384.88  4978.7 1381.18  4997.5 1377.88
  5000.3 1377.38  5003.5 1377.88  5007.2 1379.69  5021.4 1381.86    5028 1383.62
  5070.8 1386.13    5085 1389.14  5092.6 1392.09  5106.9 1399.25  5120.2 1408.54
    5130 1413.52  5170.5  1430.2  5184.7 1434.82  5205.6 1439.53  5234.1 1441.77
  5248.4 1446.04    5255 1447.27  5283.5 1450.45  5301.6 1456.15  5304.3 1456.15
#Mann= 6 ,-1 , 0
  4359.1      .1       0  4753.4     .05       0  4871.5      .1       0
  4997.5     .07       0  5003.5      .1       0    5130     .16       0
Bank Sta=4997.5,5003.5
XS Rating Curve= 0 ,0
Exp/Cntr=0.3,0.1

Type RM Length L Ch R = 1 ,9912    ,534,534,534
BEGIN DESCRIPTION:
UNT 1005 IN LATR 17.0
END DESCRIPTION:
XS GIS Cut Line= 3
      2908882.74     10111750.21      2909455.68     10111161.64
      2909533.65     10110969.33
#Sta/Elev= 30
  4425.5 1403.74    4554 1398.03  4823.1  1385.8  4978.7 1374.29  4996.9 1370.81
  4999.6 1370.31  5002.9 1370.81  5049.3 1375.77  5139.9 1374.44  5162.4 1374.94
  5197.9    1378  5212.1 1380.53  5229.5 1387.01  5246.4 1394.49  5264.2 1400.56
  5299.1 1405.37  5317.8 1409.94  5323.2 1409.78  5329.9 1411.49  5341.7 1414.42
  5347.3 1417.92  5352.7 1417.94  5371.4  1422.3  5376.8 1421.72  5395.5 1427.28
  5400.9  1426.6    5425 1431.43  5430.4 1430.66  5449.1 1433.26  5454.4 1432.37
#Mann= 8 ,-1 , 0
  4425.5     .05       0    4554      .1       0  4996.9     .07       0
  5002.9      .1       0  5139.9     .16       0  5229.5      .1       0
  5246.4     .16       0  5329.9      .1       0
Bank Sta=4996.9,5002.9
XS Rating Curve= 0 ,0
Exp/Cntr=0.3,0.1

Type RM Length L Ch R = 1 ,9378    ,342,342,342
BEGIN DESCRIPTION:
UNT 1005 IN LATR 16.0
END DESCRIPTION:
XS GIS Cut Line= 3
      2909507.76      10112130.4      2909830.68     10111271.01
      2909861.93     10111073.12
#Sta/Elev= 30
    4326 1404.21  4370.6 1399.59    4456 1395.58  4480.9 1392.45  4541.3 1389.23
  4728.4 1375.55  4803.2 1371.71  4877.5  1370.9  4920.7 1368.69  4968.2 1368.04
  4984.8 1366.41  4995.4  1363.9  4998.2  1363.4  5001.4  1363.9  5023.3 1368.79
  5038.2 1370.39  5169.2 1377.94  5224.3 1383.51  5239.9 1387.48  5244.1 1387.48
  5259.2 1393.19  5281.8 1395.06  5312.2 1400.67  5326.7 1401.07  5352.7 1403.89
    5383 1412.06  5389.1 1415.44  5403.3 1417.04  5433.7 1424.94  5444.4 1426.27
#Mann= 3 ,-1 , 0
    4326      .1       0  4995.4     .07       0  5001.4      .1       0
Bank Sta=4995.4,5001.4
XS Rating Curve= 0 ,0
Exp/Cntr=0.3,0.1

Type RM Length L Ch R = 1 ,9036    ,427,427,427
BEGIN DESCRIPTION:
UNT 1005 IN LATR 15.0
END DESCRIPTION:
XS GIS Cut Line= 4
      2909815.05     10112166.86      2909945.27     10111802.26
      2910122.35     10111547.06      2910065.05     10111130.36
#Sta/Elev= 30
    4447 1395.61  4469.1 1394.86  4505.2    1392  4623.1 1386.61  4684.7 1381.73
  4710.2 1380.49  4766.5 1375.44    4828 1371.34  4849.6 1370.65  4906.3 1366.15
  4989.8 1361.81  4992.5 1361.31  4995.8 1361.81  5001.5 1361.87  5014.9 1364.32
  5022.5 1364.74  5100.2 1364.98  5211.9 1368.32  5283.9 1371.12  5370.2 1376.25
    5433 1380.25  5471.1 1384.66    5500  1386.9  5505.1 1387.48  5511.5 1389.77
  5521.6 1391.83  5541.8 1393.67  5551.9 1394.87  5561.2    1397  5565.4    1397
#Mann= 3 ,-1 , 0
    4447      .1       0  4989.8     .07       0  4995.8      .1       0
Bank Sta=4989.8,4995.8
XS Rating Curve= 0 ,0
Exp/Cntr=0.3,0.1

Type RM Length L Ch R = 1 ,8609    ,411,411,411
BEGIN DESCRIPTION:
UNT 1005 IN LATR 14.0
END DESCRIPTION:
XS GIS Cut Line= 4
      2910497.35     10112260.56      2910481.73     10111911.64
       2910341.1      10111385.6      2910169.24     10111073.13
#Sta/Elev= 30
  4379.9 1389.29  4506.9 1383.83  4610.6 1378.03    4657 1374.45  4691.1 1373.38
  4717.1 1370.89  4743.1 1369.39  4846.1 1363.85    4949 1357.76  4975.4 1355.67
  4989.2 1351.47    4992 1350.97  4995.2 1351.47  5006.5 1351.88  5016.8 1355.38
  5058.2 1360.02  5107.2 1361.91  5254.9 1365.24  5298.6 1367.52  5410.5 1376.37
  5497.7 1384.61  5513.8 1386.77  5519.5  1386.8  5535.6 1389.44  5557.4 1391.88
  5600.9 1393.97    5617 1396.87  5622.7  1396.5  5627.1 1397.88  5630.3 1397.88
#Mann= 7 ,-1 , 0
  4379.9      .1       0  4610.6     .05       0  4743.1      .1       0
  4846.1     .05       0    4949      .1       0  4989.2     .07       0
  4995.2      .1       0
Bank Sta=4989.2,4995.2
XS Rating Curve= 0 ,0
Exp/Cntr=0.3,0.1

Type RM Length L Ch R = 1 ,8198    ,457,457,457
BEGIN DESCRIPTION:
UNT 1005 IN LATR 13.0
END DESCRIPTION:
XS GIS Cut Line= 3
      2910705.68     10112271.04       2910841.1     10111432.47
      2910633.76     10111028.16
#Sta/Elev= 30
  4350.9 1386.77  4581.1  1376.6  4617.4 1374.19  4710.6  1369.8  4716.3 1369.92
  4839.1 1363.32  4874.9 1359.89  4900.9 1356.05  4910.6 1355.62  4924.2 1354.44
  4976.2 1350.92  4993.5 1345.38  4996.2 1344.88  4999.5 1345.38  5006.6 1345.55
  5024.4 1352.67    5037 1354.13  5129.2 1355.97  5195.3  1356.3  5299.6 1356.71
  5352.8 1357.74  5378.7  1358.3  5432.8 1360.71  5513.6  1366.5  5536.1 1368.67
  5565.9 1373.41  5588.1 1376.14  5615.9 1380.86  5648.4 1383.35  5654.7 1384.48
#Mann= 10 ,-1 , 0
  4350.9      .1       0  4617.4     .16       0  4716.3     .05       0
  4910.6      .1       0  4924.2     .05       0  4993.5    .035       0
  4999.5     .05       0  5129.2      .1       0  5195.3     .05       0
  5352.8      .1       0
Bank Sta=4993.5,4999.5
XS Rating Curve= 0 ,0
Exp/Cntr=0.3,0.1

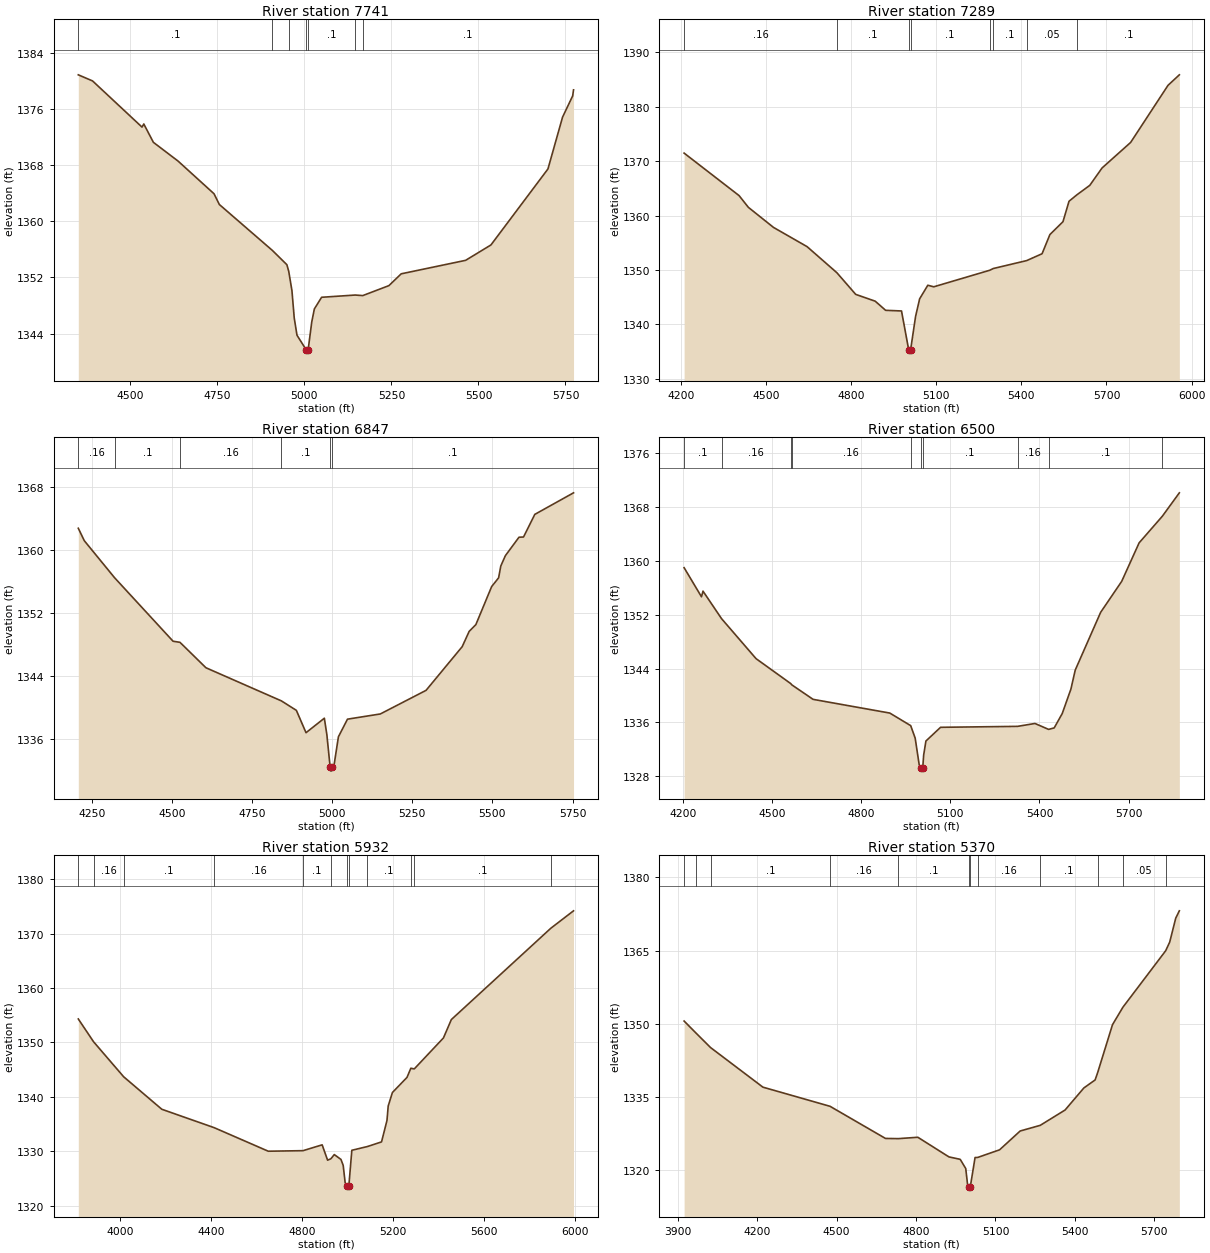
Type RM Length L Ch R = 1 ,7741    ,452,452,452
BEGIN DESCRIPTION:
UNT 1005 IN LATR 12.0
END DESCRIPTION:
XS GIS Cut Line= 3
      2911497.35     10112192.89      2911377.56     10111802.26
      2910763.21     10110995.28
#Sta/Elev= 30
  4350.4 1380.85  4391.4 1379.98  4533.4 1373.41  4538.6 1373.85  4566.1 1371.24
  4636.8 1368.58  4740.3 1363.92  4755.6 1362.39    4908 1355.85  4949.6 1353.82
    4955 1352.87  4964.2 1350.13  4970.8 1346.23  4978.7 1343.78  5004.8 1341.73
  5007.5 1341.23  5010.8 1341.73  5021.1 1345.66  5028.6 1347.52  5049.4 1349.18
    5146  1349.5  5167.6 1349.42  5242.8 1350.84  5278.1 1352.52  5463.2 1354.44
  5535.9 1356.63  5699.7 1367.45  5741.7 1374.83  5770.8 1377.86  5773.2 1378.71
#Mann= 7 ,-1 , 0
  4350.4      .1       0    4908     .05       0    4955      .1       0
  5004.8     .07       0  5010.8      .1       0    5146     .05       0
  5167.6      .1       0
Bank Sta=5004.8,5010.8
XS Rating Curve= 0 ,0
Exp/Cntr=0.3,0.1

Type RM Length L Ch R = 1 ,7289    ,442,442,442
BEGIN DESCRIPTION:
UNT 1005 IN LATR 11.0
END DESCRIPTION:
XS GIS Cut Line= 4
      2911809.85     10111994.96      2911632.77     10111416.85
      2911325.48     10111036.64      2910768.74     10110698.44
#Sta/Elev= 30
  4211.8  1371.5  4405.4 1363.69  4438.2 1361.53  4526.8 1357.84  4645.2  1354.3
  4749.9 1349.52  4816.4 1345.53  4885.1 1344.28  4921.8  1342.6  4977.8 1342.48
  5003.5 1335.23  5006.3 1334.73  5009.5 1335.23  5027.4 1341.49  5041.7 1344.72
  5070.5 1347.21  5091.3 1346.92  5288.4 1349.96    5301 1350.28  5418.8 1351.74
    5473    1353  5500.7 1356.53  5546.7 1358.89    5568 1362.65  5596.7 1363.87
  5641.1 1365.57  5684.3 1368.76  5785.1 1373.46  5916.8 1383.96  5956.7 1385.89
#Mann= 8 ,-1 , 0
  4211.8     .16       0  4749.9      .1       0  5003.5     .07       0
  5009.5      .1       0  5288.4     .05       0    5301      .1       0
  5418.8     .05       0  5596.7      .1       0
Bank Sta=5003.5,5009.5
XS Rating Curve= 0 ,0
Exp/Cntr=0.3,0.1

Type RM Length L Ch R = 1 ,6847    ,347,347,347
BEGIN DESCRIPTION:
UNT 1005 IN LATR 10.0
END DESCRIPTION:
XS GIS Cut Line= 4
      2912106.72      10111781.4      2911955.68     10111146.01
      2911742.14      10110823.1      2911367.17     10110484.58
#Sta/Elev= 30
  4207.7 1362.73  4226.4 1361.15  4320.8 1356.45  4503.4 1348.38    4525 1348.24
    4606 1345.01  4841.5  1340.8  4888.2  1339.6  4918.3 1336.76  4975.5  1338.6
  4983.4  1336.5  4993.6 1332.38  4996.3 1331.88  4999.6 1332.38  5005.6 1332.59
  5019.4 1336.24  5047.7 1338.48  5150.1 1339.14  5292.9 1342.14  5405.7 1347.69
  5427.4 1349.63  5448.3 1350.49  5497.7 1355.33  5519.3 1356.43  5526.1 1357.93
  5540.3 1359.24  5582.9 1361.59  5597.1 1361.62  5632.2 1364.49  5753.1 1367.23
#Mann= 6 ,-1 , 0
  4207.7     .16       0  4320.8      .1       0    4525     .16       0
  4841.5      .1       0  4993.6     .07       0  4999.6      .1       0
Bank Sta=4993.6,4999.6
XS Rating Curve= 0 ,0
Exp/Cntr=0.3,0.1

Type RM Length L Ch R = 1 ,6500    ,568,568,568
BEGIN DESCRIPTION:
UNT 1005 IN LATR 9.0
END DESCRIPTION:
XS GIS Cut Line= 4
      2912372.36     10111703.34       2912278.6     10111057.47
      2912007.77     10110656.43       2911582.1     10110339.77
#Sta/Elev= 30
  4203.7    1359  4262.2 1354.67  4267.3 1355.51  4329.7 1351.42  4445.8 1345.47
  4562.5 1341.76  4566.5 1341.56  4637.8 1339.41  4896.1 1337.37  4966.4  1335.5
  4981.5 1333.65  4995.1 1329.67    5001 1329.23  5003.8 1328.73    5007 1329.23
  5010.1 1331.12  5017.7 1333.21    5067 1335.25  5326.2 1335.39  5384.8 1335.82
  5430.6 1334.94  5449.5 1335.16  5476.6  1337.3  5505.8 1340.94  5520.4 1343.77
  5605.9 1352.36  5676.8 1356.97  5735.3 1362.69  5813.6 1366.66  5870.8 1370.14
#Mann= 10 ,-1 , 0
  4203.7      .1       0  4329.7     .16       0  4562.5      .1       0
  4566.5     .16       0  4966.4      .1       0    5001     .07       0
    5007      .1       0  5326.2     .16       0  5430.6      .1       0
  5813.6     .05       0
Bank Sta=5001,5007
XS Rating Curve= 0 ,0
Exp/Cntr=0.3,0.1

Type RM Length L Ch R = 1 ,5932    ,562,562,562
BEGIN DESCRIPTION:
Mapping XS 11c2d100
END DESCRIPTION:
XS GIS Cut Line= 4
      2912472.15     10111639.54      2912537.25     10110816.65
      2912321.11     10110293.22      2911563.43     10110090.13
#Sta/Elev= 30
  3816.8  1354.3  3883.9 1350.11    4016 1343.68  4183.8  1337.7  4413.7 1334.32
  4651.5 1329.99  4804.3 1330.09  4888.4 1331.16  4912.3 1328.34  4926.7  1328.6
  4941.7 1329.37    4971 1328.48  4980.8 1327.39  4989.5 1324.19  4999.5 1323.52
  5002.2 1323.02  5005.5 1323.52  5018.8 1330.16  5087.3 1330.85  5149.3  1331.7
  5173.2 1335.64  5178.6  1338.3  5197.1 1340.78  5261.2 1343.56  5278.1 1345.24
  5293.2 1345.12  5421.3 1350.81  5456.1 1354.19    5893 1370.97    5993 1374.18
#Mann= 12 ,-1 , 0
  3816.8      .1       0  3883.9     .16       0    4016      .1       0
  4413.7     .16       0  4804.3      .1       0  4926.7     .05       0
  4999.5    .035       0  5005.5     .05       0  5087.3      .1       0
  5278.1     .05       0  5293.2      .1       0    5893     .05       0
Bank Sta=4999.5,5005.5
XS Rating Curve= 0 ,0
Exp/Cntr=0.3,0.1

Type RM Length L Ch R = 1 ,5370    ,551,551,551
BEGIN DESCRIPTION:
UNT 1005 IN LATR 8.0
END DESCRIPTION:
XS GIS Cut Line= 4
      2912601.52     10111609.54      2912700.48     10110734.56
      2913184.85      10110198.1      2913247.22     10109938.22
#Sta/Elev= 30
  3923.9 1350.56  3967.3 1348.18  4023.8 1345.13  4221.6 1337.02  4475.1  1333.1
  4684.5 1326.52  4732.8 1326.48  4806.7 1326.76  4924.2 1322.74  4966.8 1322.24
  4987.7 1320.35  4994.5 1317.12  4998.9 1316.64  5001.7 1316.14  5004.9 1316.64
  5022.9 1322.61    5033 1322.63  5115.5 1324.19  5193.2 1328.04    5269  1329.2
  5362.9 1332.34  5433.9 1336.86  5476.4  1338.5  5486.2 1340.04    5542 1349.81
  5581.2 1353.38  5742.8 1364.95    5758 1366.71    5781 1371.65  5794.5 1373.13
#Mann= 12 ,-1 , 0
  3923.9      .1       0  3967.3     .16       0  4023.8      .1       0
  4475.1     .16       0  4732.8      .1       0  4998.9     .07       0
  5004.9      .1       0    5033     .16       0    5269      .1       0
  5486.2     .16       0  5581.2     .05       0  5742.8      .1       0
Bank Sta=4998.9,5004.9
XS Rating Curve= 0 ,0
Exp/Cntr=0.3,0.1

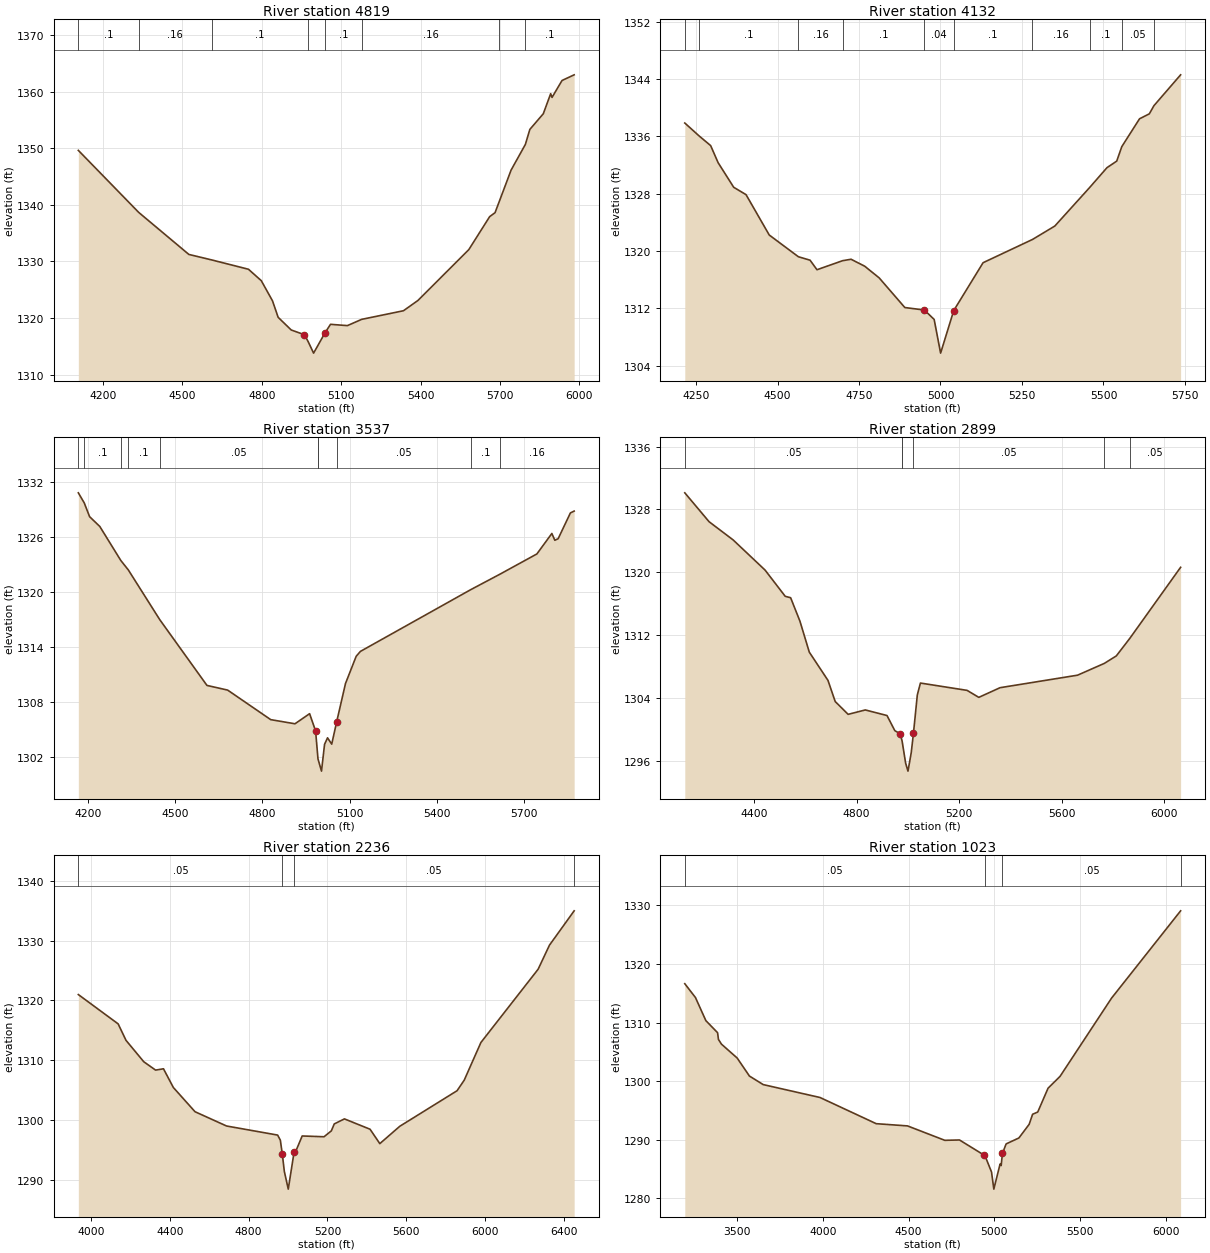
Type RM Length L Ch R = 1 ,4819    ,687,687,687
BEGIN DESCRIPTION:
UNT 1005 IN LATR 7.0
END DESCRIPTION:
XS GIS Cut Line= 4
      2912940.06     10111750.18       2913091.1     10111099.14
      2913523.39     10110661.64      2913617.11      10110078.5
#Sta/Elev= 30
  4106.7 1349.62  4335.1 1338.65  4524.5 1331.23  4611.7 1330.25  4749.8 1328.61
  4798.2 1326.59  4840.6 1323.03  4861.9 1320.12  4911.3 1317.88  4960.9 1317.05
    4975 1315.86  4995.9 1313.79  5038.6 1317.34  5059.9 1318.88  5123.5 1318.65
  5177.9 1319.76  5335.6 1321.28  5390.1 1323.09  5582.5 1332.08  5661.4 1337.91
  5681.7 1338.61  5697.3 1340.54  5742.4 1346.14  5796.3 1350.67  5813.3 1353.33
    5864 1356.09    5892 1359.64  5897.1 1358.98  5934.9 1361.97  5980.7 1362.97
#Mann= 8 ,-1 , 0
  4106.7      .1       0  4335.1     .16       0  4611.7      .1       0
    4975     .04       0  5038.6      .1       0  5177.9     .16       0
  5697.3     .05       0  5796.3      .1       0
Bank Sta=4960.9,5038.6
XS Rating Curve= 0 ,0
Exp/Cntr=0.3,0.1

Type RM Length L Ch R = 1 ,4132    ,595,595,595
BEGIN DESCRIPTION:
UNT 1005 IN LATR 5.0
END DESCRIPTION:
XS GIS Cut Line= 3
      2913669.23     10111781.41      2913851.52     10111187.68
      2913841.11     10110287.73
#Sta/Elev= 30
  4215.6 1337.85  4259.5 1336.05  4294.9  1334.7  4317.8 1332.32  4365.6 1328.89
  4403.5 1327.86  4474.7 1322.23  4564.1  1319.2  4599.9 1318.72  4621.1 1317.39
  4699.6 1318.65  4725.7 1318.85  4767.6 1317.88    4812 1316.25  4890.6 1312.12
  4950.6 1311.77  4980.6 1310.46  5000.4 1305.76  5040.6 1311.69  5130.7 1318.37
  5282.2 1321.61  5350.7 1323.48  5457.9 1328.87  5510.7 1331.62  5540.7 1332.54
  5556.3 1334.56  5610.7 1338.44  5640.7 1339.13  5654.7 1340.26  5736.7 1344.57
#Mann= 10 ,-1 , 0
  4215.6     .16       0  4259.5      .1       0  4564.1     .16       0
  4699.6      .1       0  4950.6     .04       0  5040.6      .1       0
  5282.2     .16       0  5457.9      .1       0  5556.3     .05       0
  5654.7     .16       0
Bank Sta=4950.6,5040.6
XS Rating Curve= 0 ,0
Exp/Cntr=0.3,0.1

Type RM Length L Ch R = 1 ,3537    ,638,638,638
BEGIN DESCRIPTION:
UNT 1005 IN LATR 3.0
END DESCRIPTION:
XS GIS Cut Line= 3
      2913945.24     10111864.79      2914372.35     10111375.18
      2914617.15      10110349.1
#Sta/Elev= 30
    4167 1330.82  4187.2 1329.73  4205.8 1328.22  4240.9 1327.15    4313 1323.45
  4338.8 1322.42  4446.9    1317  4609.2 1309.83  4680.4 1309.32  4828.5  1306.1
  4911.8 1305.65  4962.1 1306.75  4982.7 1304.87  4990.9 1301.83    5003 1300.49
  5013.5 1303.41  5023.8 1304.12  5038.1 1303.43  5054.7  1305.8  5085.5 1310.04
  5122.3 1313.01  5136.9 1313.54  5516.8 1320.28  5616.9 1321.96  5743.5 1324.16
  5794.9 1326.39  5805.2 1325.65  5816.6 1325.82  5858.7 1328.63  5871.6 1328.83
#Mann= 10 ,-1 , 0
    4167     .16       0  4187.2      .1       0    4313     .16       0
  4338.8      .1       0  4446.9     .05       0  4990.9      .1       0
  4990.9    .035       0  5054.7     .05       0  5516.8      .1       0
  5616.9     .16       0
Bank Sta=4982.7,5054.7
XS Rating Curve= 0 ,0
Exp/Cntr=0.3,0.1

Type RM Length L Ch R = 1 ,2899    ,663,663,663
BEGIN DESCRIPTION:
UNT 1005 IN LATR 2.0
END DESCRIPTION:
XS GIS Cut Line= 3
      2914164.03     10111989.76      2915127.56     10111375.18
      2915445.25     10110651.27
#Sta/Elev= 30
  4130.1 1330.11  4224.7 1326.44  4318.6 1324.12    4443 1320.29  4521.7 1316.95
  4542.8 1316.77  4579.2 1313.78  4615.6 1309.85  4688.4 1306.26  4716.6 1303.57
  4767.1 1301.94  4833.9  1302.5  4918.6 1301.79    4949 1299.87  4970.2 1299.46
  4977.5 1298.54  4991.3 1295.72  5000.4 1294.72  5013.1 1297.07  5021.8 1299.56
  5036.8 1304.41  5048.9 1305.92  5230.8 1304.99  5276.5  1304.1  5359.4 1305.33
  5661.6 1306.92    5766 1308.42  5812.7 1309.37  5865.3  1311.6  6063.5 1320.64
#Mann= 6 ,-1 , 0
  4130.1     .05       0  4977.5      .1       0  4977.5    .035       0
  5021.8     .05       0    5766      .1       0  5865.3     .05       0
Bank Sta=4970.2,5021.8
XS Rating Curve= 0 ,0
Exp/Cntr=0.3,0.1

Type RM Length L Ch R = 1 ,2236    ,1213,1213,1213
BEGIN DESCRIPTION:
UNT 1005 IN LATR 1.0
END DESCRIPTION:
XS GIS Cut Line= 4
       2914516.5     10112123.32      2915353.27     10112140.68
      2915401.88     10111720.54      2916082.43       10110665.
#Sta/Elev= 30
  3936.3 1320.97  4138.3 1316.06  4178.3  1313.3  4268.3 1309.72  4328.3 1308.32
  4368.4 1308.54  4418.4 1305.41  4528.4 1301.35  4688.4 1298.96  4947.6 1297.44
  4961.4 1296.58  4971.5 1294.19  4981.6 1291.35  5001.5 1288.39  5031.4 1294.67
  5036.4 1294.48  5072.2 1297.29  5182.9 1297.16  5219.9 1298.14    5235 1299.31
  5286.5 1300.15  5416.5 1298.42  5466.1 1296.01  5567.7 1298.92  5858.1 1304.87
  5894.4 1306.64  5978.9 1312.94  6269.3 1325.21  6326.8 1329.24  6452.1 1334.99
#Mann= 4 ,-1 , 0
  3936.3     .05       0  4971.5    .035       0  5031.4     .05       0
  6452.1     .05       0
Bank Sta=4971.5,5031.4
XS Rating Curve= 0 ,0
Exp/Cntr=0.3,0.1

Type RM Length L Ch R = 1 ,1023    ,779,779,779
BEGIN DESCRIPTION:
Mapping XS c506b207
END DESCRIPTION:
XS GIS Cut Line= 4
      2914667.28     10112156.26      2916093.22     10112398.62
      2916355.79     10112051.23      2916299.24     10111041.36
#Sta/Elev= 30
  3194.4 1316.64  3256.5 1314.29  3317.3 1310.34  3385.7 1308.28  3390.8 1307.13
  3408.6 1306.32  3499.9 1303.96  3571.6 1300.88  3652.1 1299.42  3983.3 1297.22
  4311.4 1292.75    4494 1292.37  4711.7 1289.91  4797.3 1289.97  4940.6 1287.39
  4947.8 1287.16  4984.3  1284.5  4997.7 1281.58  5034.2 1285.86  5040.5  1285.6
    5048 1287.67  5069.6  1289.3  5143.9 1290.31  5203.9 1292.64    5224 1294.36
    5254 1294.74  5314.1  1298.8  5384.2 1300.83  5684.7 1314.18  6087.7 1329.08
#Mann= 4 ,-1 , 0
  3194.4     .05       0  4947.8    .035       0    5048     .05       0
  6087.7      .1       0
Bank Sta=4940.6,5048
XS Rating Curve= 0 ,0
Exp/Cntr=0.3,0.1

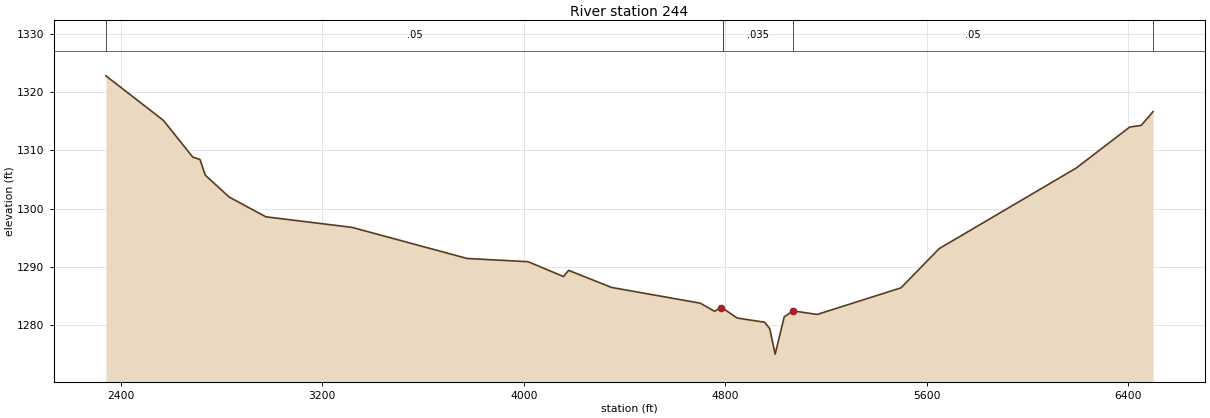
Type RM Length L Ch R = 1 ,244     ,0,0,0
BEGIN DESCRIPTION:
Mapping XS 98f47fe1
END DESCRIPTION:
XS GIS Cut Line= 5
      2914449.16     10112123.94      2915822.58     10112519.81
      2917002.11     10112386.51       2917103.1     10112261.28
      2916917.28     10110891.87
#Sta/Elev= 30
  2340.3 1322.87  2568.5  1315.2  2685.4 1308.86  2713.8 1308.46    2735 1305.75
  2830.4 1301.96  2975.5 1298.57  3317.8 1296.75  3774.9 1291.39  4017.1 1290.83
    4158 1288.27  4178.1 1289.34  4349.2 1286.39  4701.4 1283.68  4757.8 1282.28
  4781.9 1282.93    4792 1282.77  4847.6 1281.12  4956.7  1280.4  4977.1 1279.27
  4998.5  1274.9  5034.7 1281.34  5069.9 1282.35  5165.5 1281.74  5498.6 1286.33
  5649.9 1293.08  6194.9 1306.99  6406.8 1314.04  6452.8 1314.33  6499.5  1316.7
#Mann= 5 ,-1 , 0
  2340.3     .05       0    4792     .16       0    4792    .035       0
  5069.9     .05       0  6499.5     .05       0
Bank Sta=4781.9,5069.9
XS Rating Curve= 0 ,0
Exp/Cntr=0.3,0.1

Chan Stop Cuts=-1
Use User Specified Reach Order=0
Composite Channel Slope=5