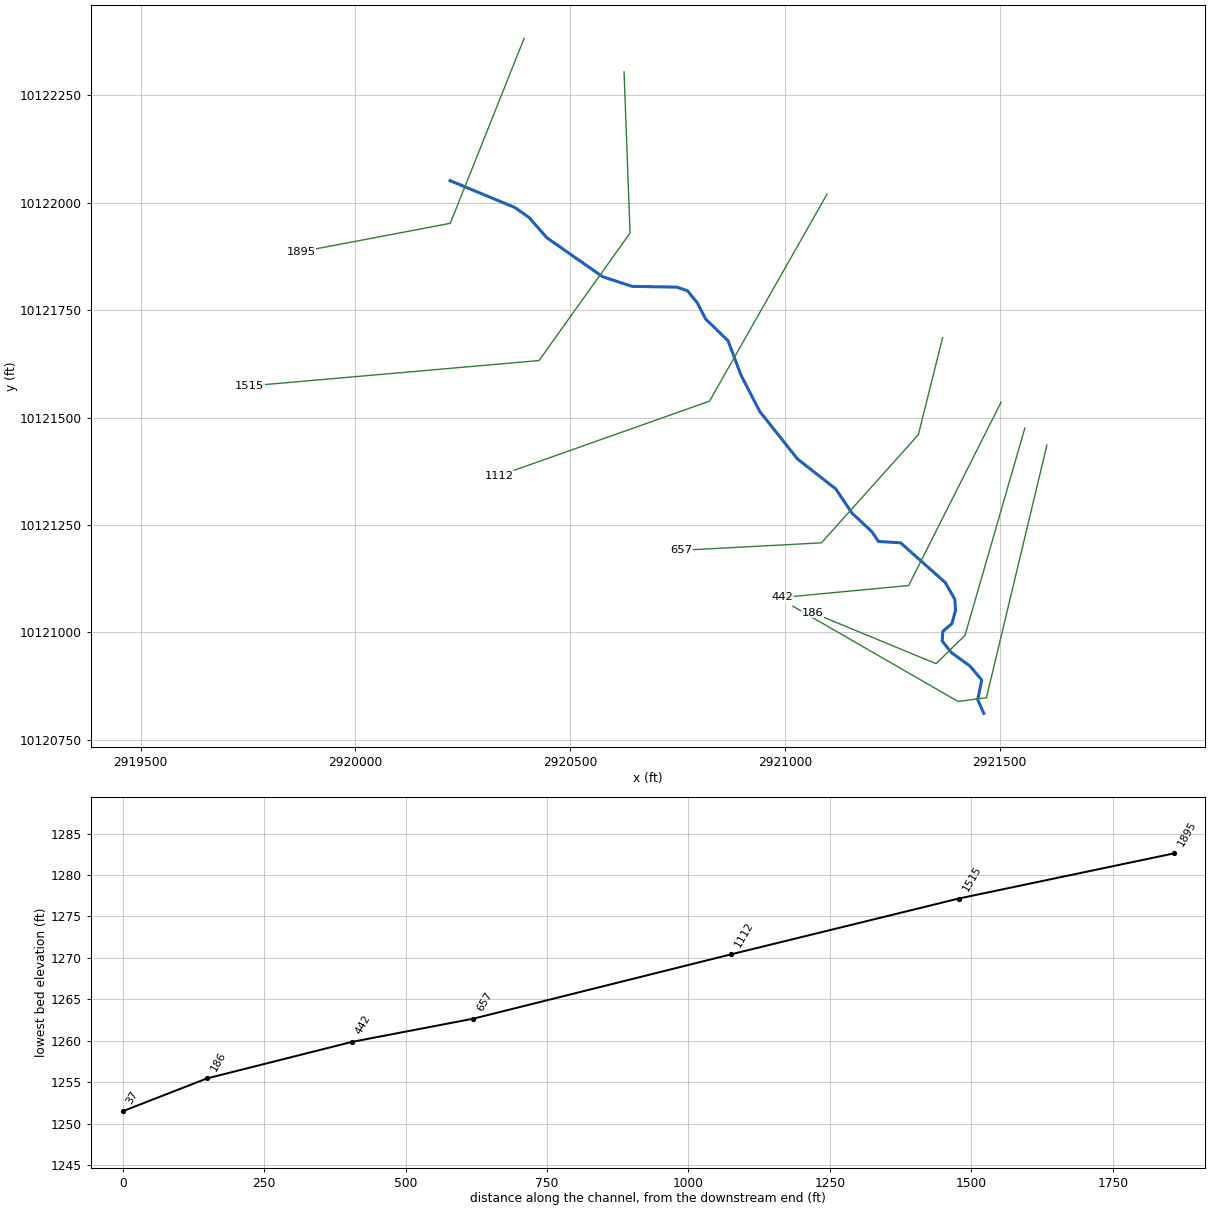
--- UNT 0008 IN LATR.prj (project) ---

Proj Title=UNT 1008 IN LATR Base Level Engineering
Current Plan=p01
Default Exp/Contr=0.3,0.1
English Units
Geom File=g01
Flow File=f01
Plan File=p01
Y Axis Title=Elevation
X Axis Title(PF)=Main Channel Distance
X Axis Title(XS)=Station
BEGIN DESCRIPTION:
UNT 1008 IN LATR
END DESCRIPTION:
DSS Export Rating Curves= 0
DSS Export Rating Curve Sorted= 0
DSS Export Volume Flow Curves= 0
DXF OffsetX= 0
DXF OffsetY= 0
DXF ScaleX= 1
DXF ScaleY= 10

--- UNT 0008 IN LATR.p01 (plan) ---

Plan Title=Multiple Run
Short Identifier=Multiple
Geom File=g01
Flow File=f01
Subcritical Flow
K Sum by GR= 0
Std Step Tol= 0.01
Critical Tol= 0.01
Num of Std Step Trials= 20
Max Error Tol= 0.3
Flow Tol Ratio= 0.001
Split Flow NTrial= 30
Split Flow Tol= 0.02
Split Flow Ratio= 0.02
Log Output Level= 0
Friction Slope Method= 1
Unsteady Friction Slope Method= 2
Unsteady Bridges Friction Slope Method= 1
Parabolic Critical Depth
Global Vel Dist=  1 , 1 , 1
Global Log Level= 0
CheckData=True
Encroach Param= -1, 0, 0, 0
BEGIN DESCRIPTION:
Multiple Run
END DESCRIPTION:

--- UNT 0008 IN LATR.f01 (steady flow) ---

Flow Title=Multiple
Number of Profiles=7
Profile Names=10-year,25-year,50-year,1pct_min,100-year,1pct_plu,500-year
River Rch & RM= UNT 1008 IN LATR,Reach-1,1895
     440     614     759     690     933    1262    1411
Boundary for River Rch & Prof#=UNT 1008 IN LATR,Reach-1,1
Up Type=0
Dn Type=3
Dn Slope=0.005
Boundary for River Rch & Prof#=UNT 1008 IN LATR,Reach-1,2
Up Type=0
Dn Type=3
Dn Slope=0.005
Boundary for River Rch & Prof#=UNT 1008 IN LATR,Reach-1,3
Up Type=0
Dn Type=3
Dn Slope=0.005
Boundary for River Rch & Prof#=UNT 1008 IN LATR,Reach-1,4
Up Type=0
Dn Type=3
Dn Slope=0.005
Boundary for River Rch & Prof#=UNT 1008 IN LATR,Reach-1,5
Up Type=0
Dn Type=3
Dn Slope=0.005
Boundary for River Rch & Prof#=UNT 1008 IN LATR,Reach-1,6
Up Type=0
Dn Type=3
Dn Slope=0.005
Boundary for River Rch & Prof#=UNT 1008 IN LATR,Reach-1,7
Up Type=0
Dn Type=3
Dn Slope=0.005

--- UNT 0008 IN LATR.g01 (geometry) ---

Geom Title=Existing Conditions
Program Version=4.10

River Reach=UNT 1008 IN LATR,Reach-1
Reach XY= 30
      2920220.53     10122051.67      2920371.33     10121989.09
      2920404.28      10121965.9      2920445.78     10121918.72
      2920575.55     10121828.08      2920644.22     10121805.53
      2920748.51     10121803.76      2920773.04     10121795.24
      2920795.83     10121767.46      2920815.35     10121729.62
      2920867.44     10121679.06       2920897.9     10121598.58
      2920941.06     10121514.81       2921029.1     10121403.87
      2921118.52     10121333.87      2921156.35      10121277.4
      2921202.19     10121234.71      2921217.81     10121211.81
      2921269.35     10121208.57      2921373.13     10121116.15
      2921395.59     10121076.74      2921396.98     10121051.05
      2921388.57     10121020.51      2921367.47     10121002.44
      2921366.08     10120979.87      2921388.06     10120952.66
      2921430.66     10120921.88      2921458.09     10120889.24
      2921448.72     10120843.76      2921462.85     10120811.62

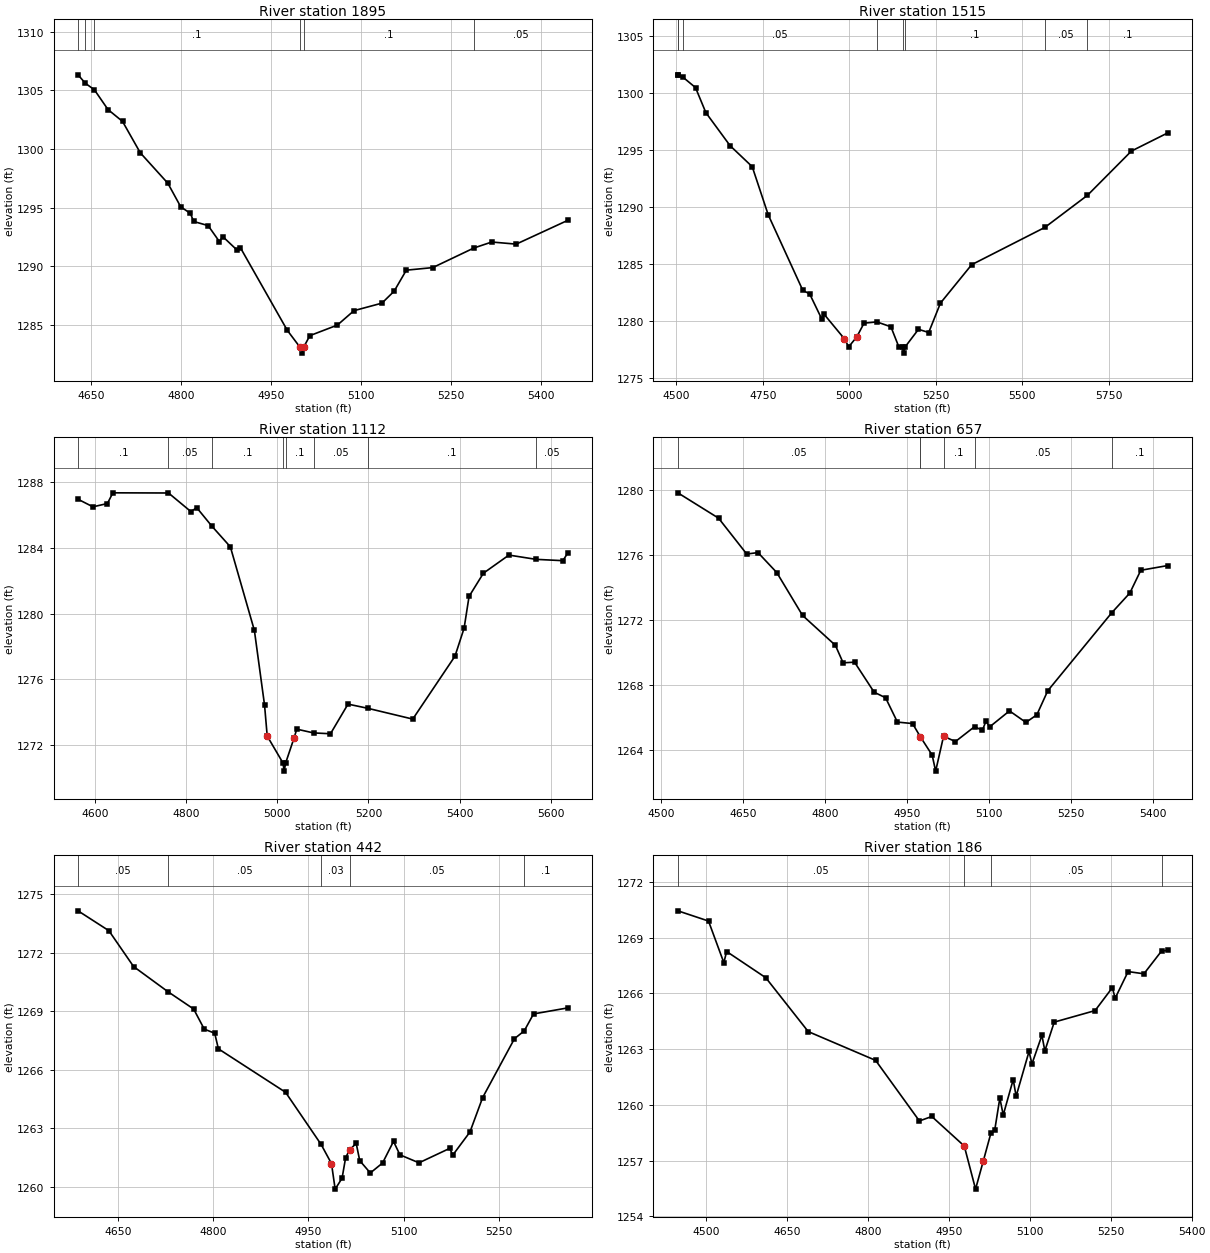
Type RM Length L Ch R = 1 ,1895    ,380,380,380
BEGIN DESCRIPTION:
UNT 1008 IN LATR 3.0
END DESCRIPTION:
XS GIS Cut Line= 3
      2920392.91     10122382.86      2920221.03      10121952.3
      2919873.84     10121886.34
#Sta/Elev= 30
    4628 1306.33  4640.2 1305.61  4655.2 1305.06    4678 1303.37  4702.2 1302.36
  4731.9 1299.68  4777.8 1297.09  4799.3 1295.08  4815.4 1294.52  4820.9 1293.83
    4845 1293.48  4863.9 1292.11  4869.3 1292.55  4893.5 1291.38  4898.9 1291.59
  4977.1 1284.55  4998.3 1283.11  5001.1 1282.61  5004.3 1283.11  5014.7  1284.1
  5060.6    1285  5088.3 1286.23  5134.9 1286.87  5155.3 1287.89  5175.6 1289.68
  5219.7  1289.9  5288.3 1291.57  5318.1 1292.08  5358.9  1291.9    5445 1293.93
#Mann= 6 ,-1 , 0
    4628      .1       0  4640.2     .05       0  4655.2      .1       0
  4998.3     .07       0  5004.3      .1       0  5288.3     .05       0
Bank Sta=4998.3,5004.3
XS Rating Curve= 0 ,0
Exp/Cntr=0.3,0.1

Type RM Length L Ch R = 1 ,1515    ,403,403,403
BEGIN DESCRIPTION:
Mapping XS 226861e2
END DESCRIPTION:
XS GIS Cut Line= 4
      2920625.55     10122304.72      2920639.44     10121929.73
      2920427.63     10121632.86      2919754.05     10121573.83
#Sta/Elev= 30
    4504 1301.59  4504.8 1301.59    4518  1301.4    4555 1300.47    4585 1298.27
  4655.1 1295.37    4719 1293.53  4765.2 1289.31  4865.2 1282.68    4885 1282.37
  4920.6 1280.13  4926.8 1280.58  4984.9 1278.45  4998.1 1277.73  5021.4  1278.6
  5042.3  1279.8  5079.4 1279.91    5120 1279.48  5143.1  1277.7  5153.9 1277.67
  5156.6 1277.17  5159.9 1277.67  5199.7 1279.26  5229.2 1278.98  5263.2 1281.56
  5353.5 1284.93    5565  1288.2  5688.3 1291.02  5815.3  1294.9  5920.1 1296.49
#Mann= 8 ,-1 , 0
    4504     .05       0  4504.8      .1       0    4518     .05       0
  5079.4      .1       0  5153.9    .035       0  5159.9      .1       0
    5565     .05       0  5688.3      .1       0
#XS Ineff= 2 , 0
                         5085.62         1279.34
Permanent Ineff=
       F       F
Bank Sta=4984.9,5021.4
XS Rating Curve= 0 ,0
Exp/Cntr=0.3,0.1

Type RM Length L Ch R = 1 ,1112    ,455,455,455
BEGIN DESCRIPTION:
Mapping XS aa94d3af
END DESCRIPTION:
XS GIS Cut Line= 3
      2921097.89     10122020.15      2920824.47     10121538.42
      2920334.01      10121364.8
#Sta/Elev= 30
    4563 1286.94  4595.7 1286.48  4627.4 1286.68  4639.4 1287.33  4761.4 1287.32
  4810.6 1286.19  4823.3 1286.43  4856.4 1285.31  4897.1 1284.05  4949.8 1278.97
  4972.1 1274.43  4977.9 1272.56  5012.4 1270.93  5015.1 1270.43  5018.4 1270.93
    5037 1272.46  5042.7 1272.98  5079.5 1272.75  5116.7  1272.7  5155.1  1274.5
  5199.3 1274.24  5297.1 1273.59  5389.7 1277.41  5409.7 1279.11  5420.6 1281.04
  5452.1 1282.45    5508 1283.55  5567.6 1283.29  5626.3 1283.21  5637.2 1283.68
#Mann= 8 ,-1 , 0
    4563      .1       0  4761.4     .05       0  4856.4      .1       0
  5012.4     .07       0  5018.4      .1       0  5079.5     .05       0
  5199.3      .1       0  5567.6     .05       0
Bank Sta=4977.9,5037
XS Rating Curve= 0 ,0
Exp/Cntr=0.3,0.1

Type RM Length L Ch R = 1 ,657     ,215,215,215
BEGIN DESCRIPTION:
UNT 1008 IN LATR 2.0
END DESCRIPTION:
XS GIS Cut Line= 4
      2921367.01     10121686.02      2921310.58     10121460.29
      2921084.89     10121208.56      2920759.32     10121191.19
#Sta/Elev= 30
  4530.5 1279.82    4605 1278.26  4656.6 1276.05  4677.2 1276.14  4711.6 1274.91
  4758.8 1272.27  4818.9 1270.43  4833.1 1269.35    4854 1269.39  4889.9 1267.54
  4910.8  1267.2  4932.5  1265.7  4960.2 1265.61  4974.4  1264.8  4996.1 1263.67
  5002.5 1262.68    5017 1264.83  5038.7  1264.5  5073.8 1265.42    5088 1265.19
  5094.7 1265.76  5101.2  1265.4  5137.7 1266.39  5167.8 1265.68  5187.8 1266.15
  5207.8 1267.63  5325.1 1272.44  5358.1 1273.65  5378.1 1275.05  5427.3 1275.34
#Mann= 6 ,-1 , 0
  4530.5     .05       0  4974.4      .1       0  4974.4     .07       0
    5017      .1       0  5073.8     .05       0  5325.1      .1       0
Bank Sta=4974.4,5017
XS Rating Curve= 0 ,0
Exp/Cntr=0.3,0.1

Type RM Length L Ch R = 1 ,442     ,256,256,256
BEGIN DESCRIPTION:
Mapping XS efb86a26
END DESCRIPTION:
XS GIS Cut Line= 3
       2921503.3     10121536.36        2921288.     10121109.23
      2920994.63     10121081.45
#Sta/Elev= 30
  4586.3 1274.15    4635 1273.13    4674 1271.29  4727.8 1270.01  4768.8 1269.11
  4785.5 1268.08    4802 1267.87  4807.8 1267.07  4913.8 1264.84    4970 1262.16
  4986.3 1261.18  4992.1 1259.87    5003 1260.43  5008.6 1261.48  5014.8 1261.88
  5025.3 1262.22  5030.9 1261.33  5047.6  1260.7  5066.9 1261.21  5084.2 1262.32
  5094.3 1261.63  5124.4 1261.22  5172.8 1261.96  5177.8 1261.62  5204.8  1262.8
  5224.9 1264.57  5275.1 1267.59  5290.5 1267.99  5305.2 1268.86  5359.3 1269.17
#Mann= 5 ,-1 , 0
  4586.3     .05       0  4727.8     .05       0    4970     .03       0
  5014.8     .05       0  5290.5      .1       0
Bank Sta=4986.3,5014.8
XS Rating Curve= 0 ,0
Exp/Cntr=0.3,0.1

Type RM Length L Ch R = 1 ,186     ,149,149,149
BEGIN DESCRIPTION:
Mapping XS e0944594
END DESCRIPTION:
XS GIS Cut Line= 4
      2921558.47     10121475.85      2921419.13     10120993.29
      2921351.66     10120927.29       2921064.2      10121046.1
#Sta/Elev= 30
  4447.8 1270.45  4504.6  1269.9    4533 1267.66  4538.2 1268.26  4610.7 1266.85
  4689.4 1263.95  4814.3  1262.4  4895.4 1259.14  4918.4 1259.38  4978.6 1257.79
  4999.5 1255.47  5013.9 1256.99    5028 1258.49    5035 1258.64  5044.5 1260.37
  5050.8 1259.46  5069.3 1261.37  5074.7 1260.47  5098.6 1262.88    5104 1262.21
  5122.5 1263.75  5127.9 1262.91  5145.3 1264.46    5221 1265.08  5252.9 1266.31
  5258.3 1265.75  5282.2 1267.18  5311.5 1267.06  5344.3 1268.29  5355.5 1268.32
#Mann= 4 ,-1 , 0
  4447.8     .05       0  4978.6     .03       0    5028     .05       0
  5344.3      .1       0
Bank Sta=4978.6,5013.9
XS Rating Curve= 0 ,0
Exp/Cntr=0.3,0.1

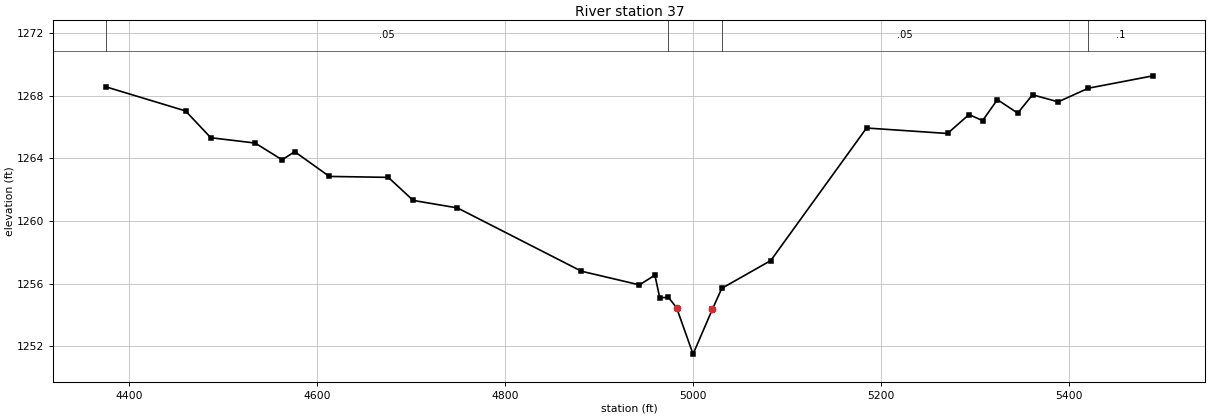
Type RM Length L Ch R = 1 ,37      ,0,0,0
BEGIN DESCRIPTION:
UNT 1008 IN LATR 1.0
END DESCRIPTION:
XS GIS Cut Line= 4
       2921609.8     10121436.26        2921469.      10120848.1
        2921403.      10120839.3      2921018.72     10121060.77
#Sta/Elev= 30
  4374.9 1268.57  4459.8 1267.03  4486.7 1265.32  4533.9 1264.98  4562.6 1263.91
    4576 1264.43  4612.9 1262.85  4675.7 1262.79  4702.1 1261.32  4749.3 1260.84
  4881.3  1256.8    4943 1255.93  4959.5 1256.55  4964.6 1255.11  4973.9 1255.13
  4982.5 1254.48  5000.1 1251.51  5020.6 1254.36  5030.7 1255.71  5082.8 1257.48
  5184.8 1265.94    5271 1265.59  5293.9  1266.8  5308.3 1266.41  5324.1 1267.75
  5345.7 1266.89  5361.5 1268.06  5388.8 1267.61  5420.9 1268.48  5489.8 1269.27
#Mann= 4 ,-1 , 0
  4374.9     .05       0  4973.9     .03       0  5030.7     .05       0
  5420.9      .1       0
Bank Sta=4982.5,5020.6
XS Rating Curve= 0 ,0
Exp/Cntr=0.3,0.1

Chan Stop Cuts=-1
Use User Specified Reach Order=0
Composite Channel Slope=5