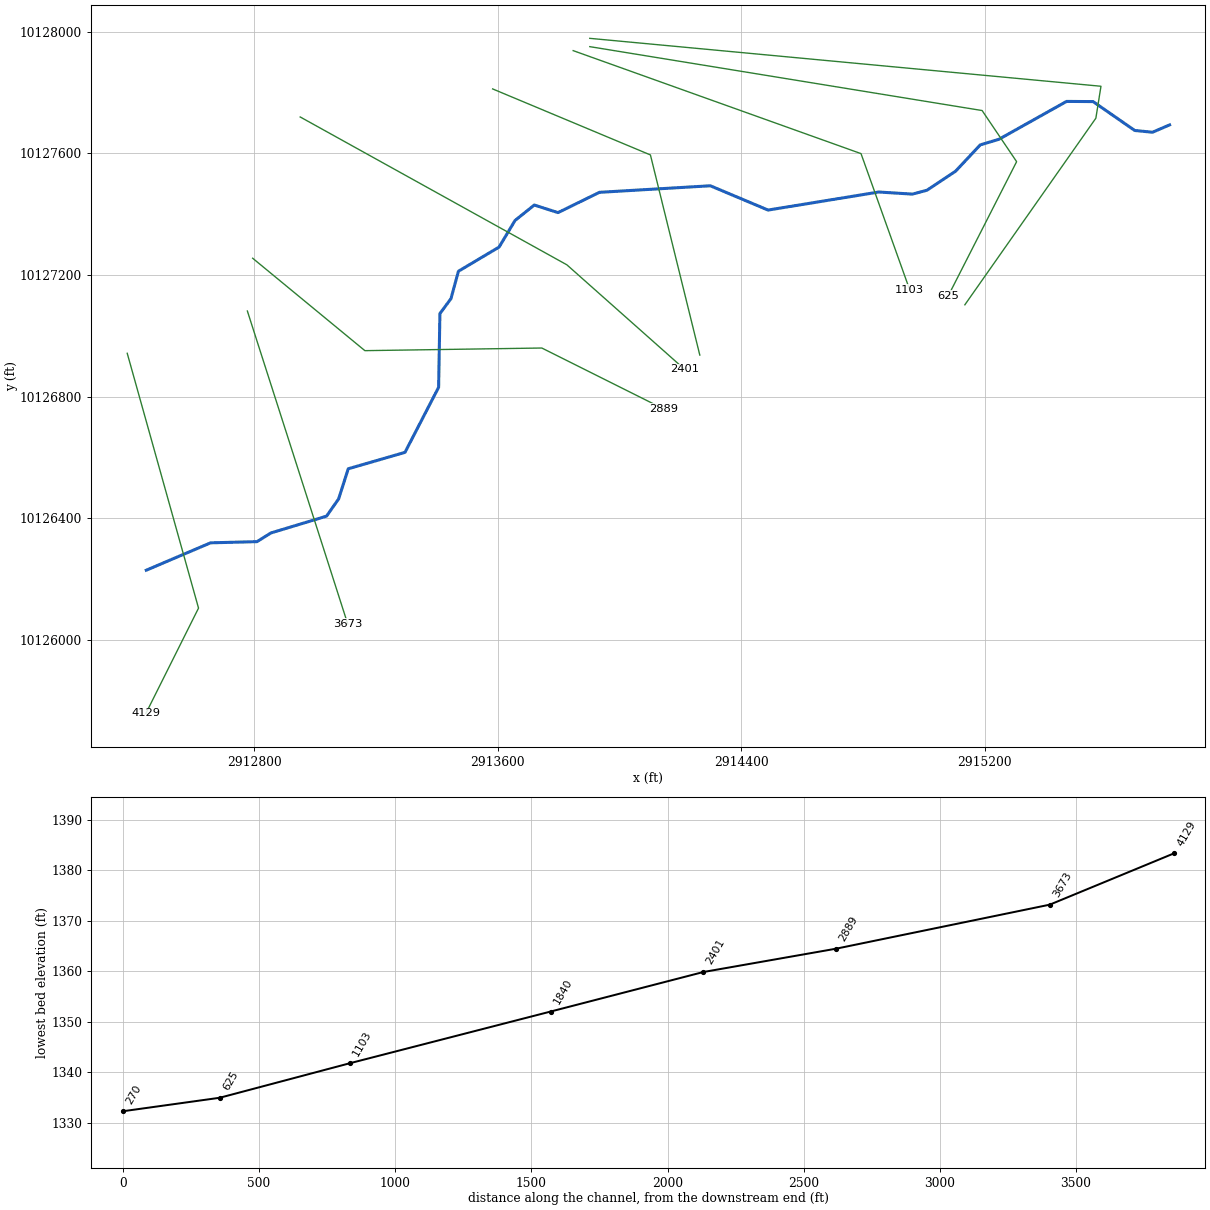
--- UNT 0010 IN LATR.prj (project) ---

Proj Title=UNT 1010 IN LATR Base Level Engineering
Current Plan=p01
Default Exp/Contr=0.3,0.1
English Units
Geom File=g01
Flow File=f01
Plan File=p01
BEGIN DESCRIPTION:
UNT 1010 IN LATR
END DESCRIPTION:

--- UNT 0010 IN LATR.p01 (plan) ---

Plan Title=Multiple Run
Short Identifier=Multiple
Geom File=g01
Flow File=f01
Subcritical Flow
K Sum by GR= 0
Std Step Tol= 0.01
Critical Tol= 0.01
Num of Std Step Trials= 20
Max Error Tol= 0.3
Flow Tol Ratio= 0.001
Split Flow NTrial= 30
Split Flow Tol= 0.02
Split Flow Ratio= 0.02
Log Output Level= 0
Friction Slope Method= 1
Unsteady Friction Slope Method= 2
Unsteady Bridges Friction Slope Method= 1
Parabolic Critical Depth
Global Vel Dist=  1 , 1 , 1
Global Log Level= 0
CheckData=True
Encroach Param= -1, 0, 0, 0
BEGIN DESCRIPTION:
Multiple Run
END DESCRIPTION:

--- UNT 0010 IN LATR.f01 (steady flow) ---

Flow Title=Multiple
Number of Profiles=7
Profile Names=10-year,25-year,50-year,1pct_min,100-year,1pct_plu,500-year
River Rch & RM= UNT 1010 IN LATR,Reach-1,4129
    1030    1516    1945    1826    2470    3341    4001
Boundary for River Rch & Prof#=UNT 1010 IN LATR,Reach-1,1
Up Type=0
Dn Type=3
Dn Slope=0.005
Boundary for River Rch & Prof#=UNT 1010 IN LATR,Reach-1,2
Up Type=0
Dn Type=3
Dn Slope=0.005
Boundary for River Rch & Prof#=UNT 1010 IN LATR,Reach-1,3
Up Type=0
Dn Type=3
Dn Slope=0.005
Boundary for River Rch & Prof#=UNT 1010 IN LATR,Reach-1,4
Up Type=0
Dn Type=3
Dn Slope=0.005
Boundary for River Rch & Prof#=UNT 1010 IN LATR,Reach-1,5
Up Type=0
Dn Type=3
Dn Slope=0.005
Boundary for River Rch & Prof#=UNT 1010 IN LATR,Reach-1,6
Up Type=0
Dn Type=3
Dn Slope=0.005
Boundary for River Rch & Prof#=UNT 1010 IN LATR,Reach-1,7
Up Type=0
Dn Type=3
Dn Slope=0.005

--- UNT 0010 IN LATR.g01 (geometry) ---

Geom Title=Existing Conditions

River Reach=UNT 1010 IN LATR,Reach-1
Reach XY= 30
      2912444.58     10126229.85      2912655.72     10126319.81
      2912808.47     10126323.73      2912854.08     10126352.24
      2913037.02     10126407.48      2913076.84     10126464.28
      2913108.41     10126563.26      2913294.96     10126617.20
      2913405.52     10126831.11      2913409.79     10127073.50
      2913446.10     10127122.56      2913470.63     10127212.62
      2913604.23     10127292.02      2913656.70     10127379.52
      2913720.02     10127430.27      2913798.03     10127405.35
      2913934.17     10127472.04      2914298.76     10127493.57
      2914488.63     10127413.72      2914852.52     10127473.07
      2914963.01     10127466.17      2915010.91     10127478.97
      2915104.86     10127541.41      2915185.99     10127627.96
      2915247.36     10127646.37      2915469.72     10127770.90
      2915556.99     10127770.33      2915693.83     10127675.37
      2915752.29     10127669.58      2915808.47     10127693.73

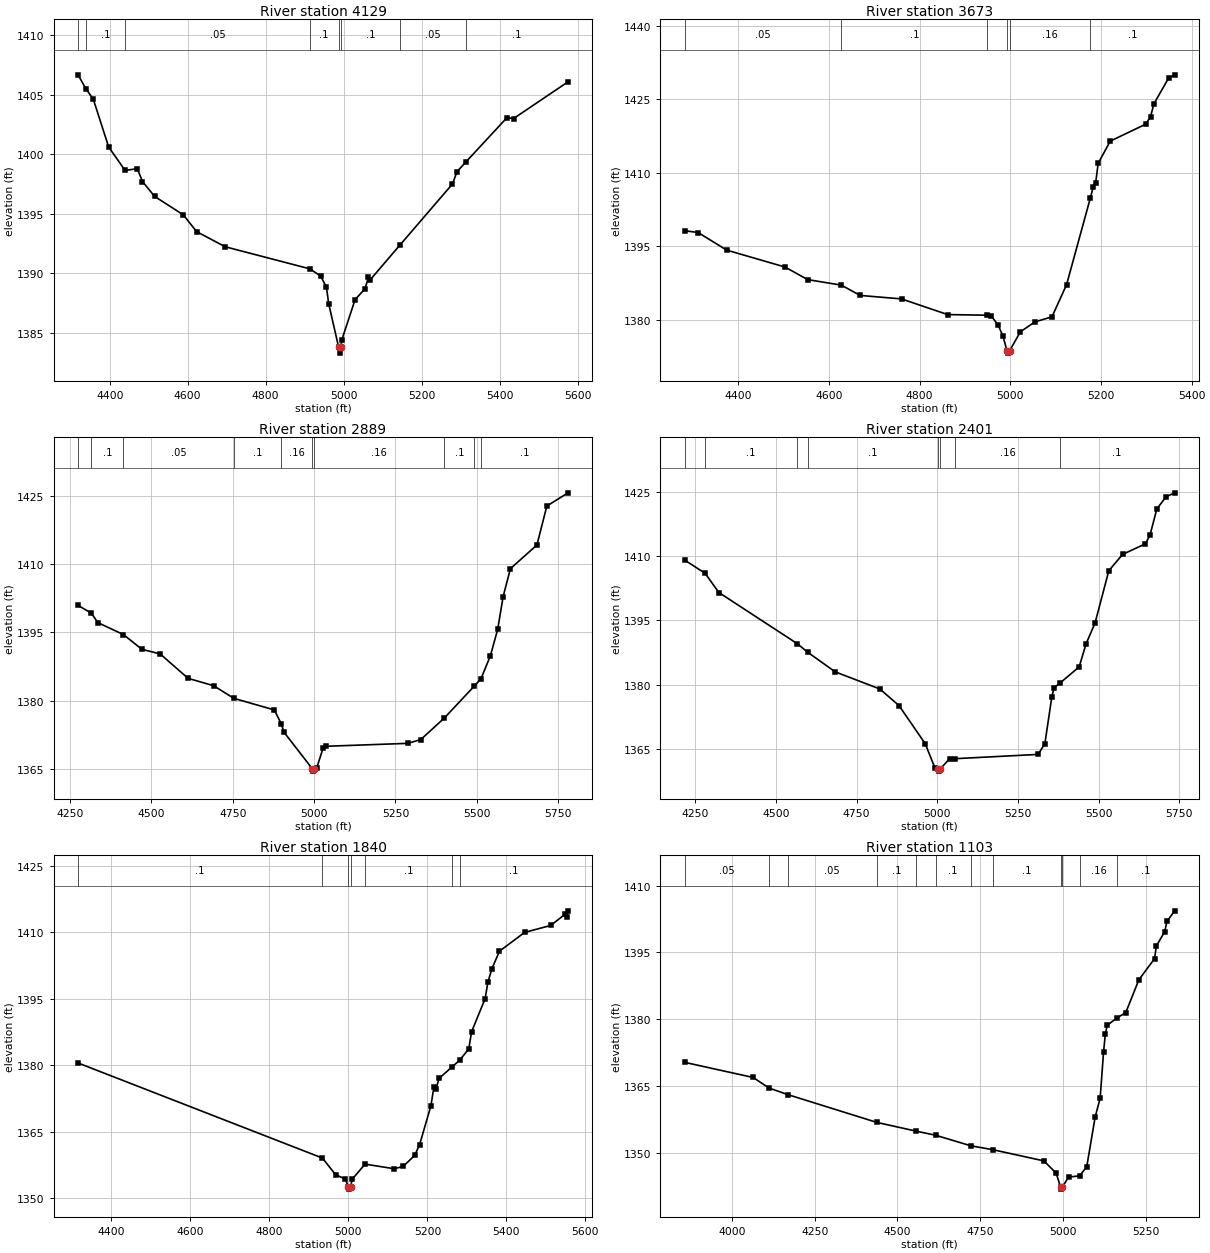
Type RM Length L Ch R = 1,4129,456,456,456
BEGIN DESCRIPTION:
UNT 1010 IN LATR 6.0
END DESCRIPTION:
XS GIS Cut Line= 3
      2912381.90     10126942.90      2912616.27     10126105.22
      2912443.27     10125759.21
#Sta/Elev= 30
  4318.8 1406.65  4338.6 1405.50  4358.0 1404.60  4397.3 1400.60  4439.5 1398.63
  4470.8 1398.78  4484.1 1397.70  4515.3 1396.45  4588.8 1394.91  4622.9 1393.50
  4696.4 1392.23  4913.2 1390.38  4941.0 1389.78  4956.0 1388.84  4961.7 1387.46
  4987.2 1383.81  4989.9 1383.31  4993.2 1383.81  4995.4 1384.42  5029.5 1387.80
  5055.2 1388.72  5063.6 1389.68  5068.8 1389.48  5145.7 1392.42  5279.3 1397.50
  5290.9 1398.53  5312.8 1399.31  5419.0 1403.06  5435.8 1402.98  5575.5 1406.06
#Mann=8,-1,0
  4318.8    0.16       0  4338.6     0.1       0  4439.5    0.05       0
  4913.2     0.1       0  4987.2    0.07       0  4993.2     0.1       0
  5145.7    0.05       0  5312.8     0.1       0
Bank Sta=4987.2,4993.2
Exp/Cntr=0.3,0.1

Type RM Length L Ch R = 1,3673,784,784,784
BEGIN DESCRIPTION:
UNT 1010 IN LATR 5.0
END DESCRIPTION:
XS GIS Cut Line= 2
      2912776.85     10127081.81      2913106.73     10126053.11
#Sta/Elev= 30
  4282.3 1398.16  4311.8 1397.79  4374.8 1394.20  4503.3 1390.75  4553.3 1388.18
  4627.6 1387.05  4669.1 1384.95  4760.3 1384.24  4861.9 1381.04  4949.2 1380.91
  4958.3 1380.76  4973.4 1378.87  4983.9 1376.67  4992.7 1373.67  4995.4 1373.17
  4998.7 1373.67  5022.5 1377.54  5054.7 1379.56  5092.0 1380.58  5124.2 1387.14
  5176.7 1404.86  5183.2 1407.18  5188.4 1407.94  5193.9 1411.92  5220.5 1416.45
  5298.9 1419.93  5309.4 1421.47  5316.9 1424.09  5349.1 1429.31  5362.6 1429.99
#Mann=6,-1,0
  4282.3    0.05       0  4627.6     0.1       0  4949.2    0.16       0
  4992.7    0.07       0  4998.7    0.16       0  5176.7     0.1       0
Bank Sta=4992.7,4998.7
Exp/Cntr=0.3,0.1

Type RM Length L Ch R = 1,2889,488,488,488
BEGIN DESCRIPTION:
UNT 1010 IN LATR 4.0
END DESCRIPTION:
XS GIS Cut Line= 4
      2912794.22     10127255.40      2913163.15     10126951.57
      2913744.75     10126960.25      2914143.75     10126760.75
#Sta/Elev= 30
  4274.6 1400.93  4315.5 1399.24  4335.3 1397.15  4414.1 1394.51  4470.9 1391.27
  4526.9 1390.26  4612.9 1384.88  4691.1 1383.27  4753.7 1380.48  4877.9 1377.93
  4898.8 1374.93  4907.9 1373.00  4994.9 1364.97  4997.6 1364.47  5000.9 1364.97
  5007.9 1365.11  5027.9 1369.57  5037.9 1369.94  5287.9 1370.58  5327.9 1371.41
  5400.3 1376.15  5492.8 1383.21  5513.0 1384.79  5542.0 1389.87  5564.4 1395.69
  5581.1 1402.89  5603.5 1409.02  5684.9 1414.23  5715.3 1422.78  5780.3 1425.70
#Mann=10,-1,0
  4274.6    0.16       0  4315.5     0.1       0  4414.1    0.05       0
  4753.7     0.1       0  4898.8    0.16       0  4994.9    0.07       0
  5000.9    0.16       0  5400.3     0.1       0  5492.8    0.05       0
  5513.0     0.1       0
Bank Sta=4994.9,5000.9
Exp/Cntr=0.3,0.1

Type RM Length L Ch R = 1,2401,561,561,561
BEGIN DESCRIPTION:
UNT 1010 IN LATR 3.0
END DESCRIPTION:
XS GIS Cut Line= 3
      2912950.49     10127719.79      2913827.21     10127233.69
      2914213.52     10126890.79
#Sta/Elev= 30
  4217.1 1409.04  4280.2 1405.97  4322.9 1401.49  4565.8 1389.57  4599.1 1387.52
  4683.6 1382.99  4821.9 1379.00  4881.4 1375.13  4962.7 1366.24  4992.3 1360.67
  5003.2 1360.35  5005.9 1359.85  5009.2 1360.35  5038.0 1362.71  5055.6 1362.75
  5312.8 1363.75  5333.7 1366.29  5355.0 1377.08  5362.1 1379.30  5379.9 1380.34
  5439.9 1384.15  5461.6 1389.57  5489.2 1394.39  5531.9 1406.57  5574.5 1410.37
  5645.6 1412.86  5659.8 1414.94  5680.7 1420.96  5709.2 1423.80  5736.1 1424.73
#Mann=8,-1,0
  4217.1    0.16       0  4280.2     0.1       0  4565.8    0.16       0
  4599.1     0.1       0  5003.2    0.07       0  5009.2     0.1       0
  5055.6    0.16       0  5379.9     0.1       0
Bank Sta=5003.2,5009.2
Exp/Cntr=0.3,0.1

Type RM Length L Ch R = 1,1840,737,737,737
BEGIN DESCRIPTION:
Mapping XS 1b4c46e5
END DESCRIPTION:
XS GIS Cut Line= 3
      2913583.12     10127811.96      2914101.78     10127594.95
      2914264.10     10126937.00
#Sta/Elev= 30
  4315.9 1380.50  4934.4 1359.04  4967.8 1355.28  4992.7 1354.29  5000.0 1352.53
  5002.7 1352.03  5006.0 1352.53  5009.3 1354.21  5042.2 1357.67  5116.3 1356.63
  5138.8 1357.16  5167.8 1359.63  5180.3 1362.06  5209.0 1370.86  5216.6 1375.15
  5221.8 1374.64  5229.6 1377.02  5261.6 1379.55  5281.8 1381.13  5304.7 1383.68
  5312.0 1387.57  5346.2 1395.04  5353.2 1398.75  5363.5 1401.82  5382.5 1405.73
  5445.9 1409.96  5512.1 1411.54  5548.4 1414.06  5553.6 1413.38  5555.8 1414.84
#Mann=7,-1,0
  4315.9     0.1       0  4934.4    0.05       0  5000.0   0.035       0
  5006.0    0.05       0  5042.2     0.1       0  5261.6    0.16       0
  5281.8     0.1       0
Bank Sta=5000,5006
Exp/Cntr=0.3,0.1

Type RM Length L Ch R = 1,1103,478,478,478
BEGIN DESCRIPTION:
UNT 1010 IN LATR 2.0
END DESCRIPTION:
XS GIS Cut Line= 3
      2913847.84     10127937.84      2914794.05     10127599.29
      2914954.06     10127151.69
#Sta/Elev= 30
  3857.3 1370.29  4063.8 1366.90  4112.1 1364.52  4169.0 1363.04  4437.2 1356.81
  4556.8 1354.83  4615.1 1353.92  4721.5 1351.55  4788.7 1350.66  4942.5 1348.15
  4979.5 1345.40  4992.6 1342.31  4995.3 1341.81  4998.6 1342.31  5016.8 1344.51
  5050.4 1344.80  5071.9 1346.84  5097.3 1358.01  5112.4 1362.23  5122.8 1372.72
  5128.1 1376.73  5133.7 1378.61  5163.8 1380.32  5189.7 1381.45  5229.2 1388.82
  5276.7 1393.59  5282.3 1396.44  5307.5 1399.68  5314.2 1401.96  5337.6 1404.34
#Mann=12,-1,0
  3857.3    0.05       0  4112.1     0.1       0  4169.0    0.05       0
  4437.2     0.1       0  4556.8    0.05       0  4615.1     0.1       0
  4721.5    0.05       0  4788.7     0.1       0  4992.6    0.07       0
  4998.6     0.1       0  5050.4    0.16       0  5163.8     0.1       0
Bank Sta=4992.6,4998.6
Exp/Cntr=0.3,0.1

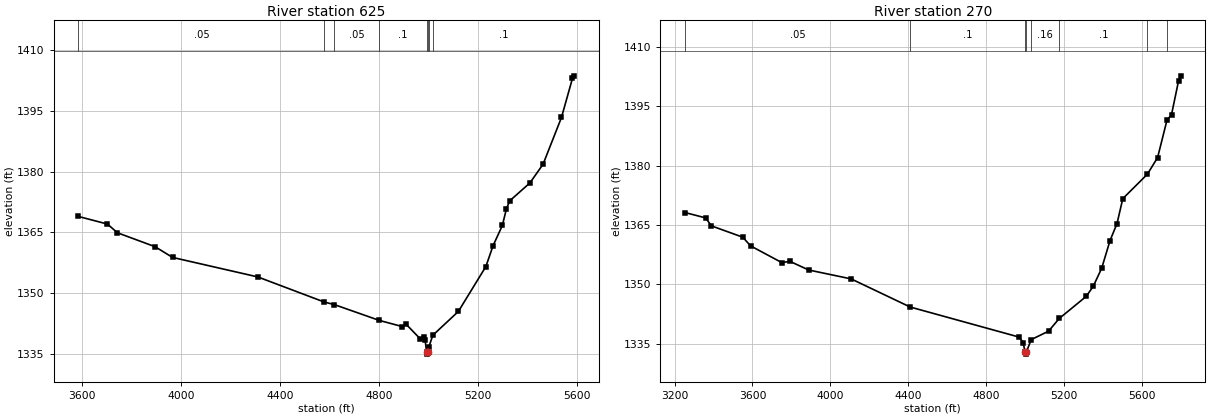
Type RM Length L Ch R = 1,625,355,355,355
BEGIN DESCRIPTION:
Mapping XS 5f725461
END DESCRIPTION:
XS GIS Cut Line= 4
      2913902.44     10127950.95      2915192.16     10127740.90
      2915305.59     10127572.85      2915080.85     10127131.77
#Sta/Elev= 30
  3583.7 1368.94  3701.3 1367.06  3741.8 1364.91  3893.8 1361.48  3964.7 1358.83
  4309.2 1354.02  4578.3 1347.82  4617.9 1347.21  4799.8 1343.31  4892.9 1341.78
  4907.9 1342.41  4964.8 1338.82  4979.8 1339.21  4985.8 1338.37  4991.8 1335.48
  4994.5 1334.98  4997.8 1335.48  5000.3 1336.65  5016.9 1339.64  5120.0 1345.50
  5231.2 1356.57  5260.5 1361.74  5297.9 1366.71  5314.6 1370.87  5327.9 1372.80
  5409.1 1377.19  5462.5 1381.81  5536.9 1393.35  5581.4 1403.00  5588.2 1403.62
#Mann=8,-1,0
  3583.7    0.05       0  4578.3     0.1       0  4617.9    0.05       0
  4799.8     0.1       0  4991.8    0.07       0  4997.8     0.1       0
  5000.3    0.16       0  5016.9     0.1       0
Bank Sta=4991.8,4997.8
Exp/Cntr=0.3,0.1

Type RM Length L Ch R = 1,270,0,0,0
BEGIN DESCRIPTION:
UNT 1010 IN LATR 1.0
END DESCRIPTION:
XS GIS Cut Line= 4
      2913902.42     10127978.26      2915582.86     10127820.72
      2915566.06     10127715.69      2915135.44     10127102.33
#Sta/Elev= 30
  3252.8 1368.13  3359.6 1366.77  3389.4 1364.75  3550.1 1361.89  3590.3 1359.69
  3751.0 1355.45  3791.2 1355.79  3888.6 1353.59  4106.2 1351.34  4409.0 1344.23
  4967.9 1336.63  4988.2 1335.26  4998.7 1332.82  5001.5 1332.32  5004.7 1332.82
  5029.9 1335.99  5118.8 1338.12  5173.9 1341.34  5312.3 1346.93  5348.0 1349.46
  5391.5 1354.04  5434.3 1361.05  5470.0 1365.32  5499.7 1371.63  5626.3 1377.84
  5678.3 1382.03  5726.1 1391.42  5749.8 1392.91  5785.5 1401.35  5796.4 1402.69
#Mann=8,-1,0
  3252.8    0.05       0  4409.0     0.1       0  4998.7    0.07       0
  5004.7     0.1       0  5029.9    0.16       0  5173.9     0.1       0
  5626.3    0.05       0  5726.1     0.1       0
Bank Sta=4998.7,5004.7
Exp/Cntr=0.3,0.1

Chan Stop Cuts=-1