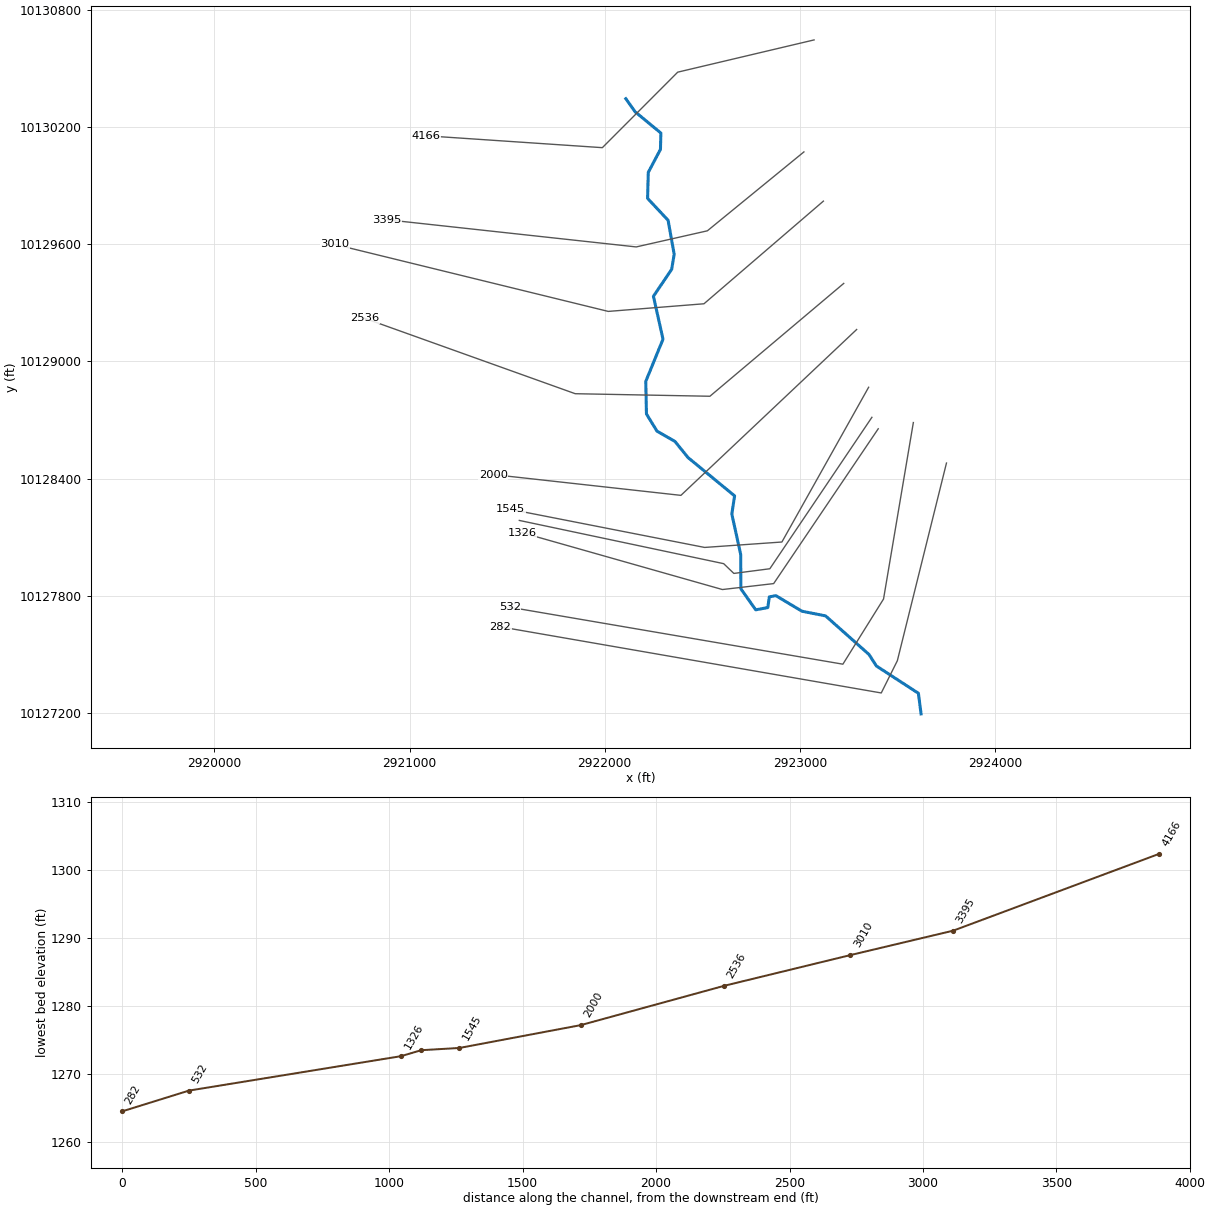
--- UNT 0011 IN LATR.prj (project) ---

Proj Title=UNT 1011 IN LATR Base Level Engineering
Current Plan=p01
Default Exp/Contr=0.3,0.1
English Units
Geom File=g01
Flow File=f01
Plan File=p01
BEGIN DESCRIPTION:
UNT 1011 IN LATR
END DESCRIPTION:

--- UNT 0011 IN LATR.p01 (plan) ---

Plan Title=Multiple Run
Short Identifier=Multiple
Geom File=g01
Flow File=f01
Subcritical Flow
K Sum by GR= 0
Std Step Tol= 0.01
Critical Tol= 0.01
Num of Std Step Trials= 20
Max Error Tol= 0.3
Flow Tol Ratio= 0.001
Split Flow NTrial= 30
Split Flow Tol= 0.02
Split Flow Ratio= 0.02
Log Output Level= 0
Friction Slope Method= 1
Unsteady Friction Slope Method= 2
Unsteady Bridges Friction Slope Method= 1
Parabolic Critical Depth
Global Vel Dist=  1 , 1 , 1
Global Log Level= 0
CheckData=True
Encroach Param= -1, 0, 0, 0
BEGIN DESCRIPTION:
Multiple Run
END DESCRIPTION:

--- UNT 0011 IN LATR.f01 (steady flow) ---

Flow Title=Multiple
Number of Profiles=7
Profile Names=10-year,25-year,50-year,1pct_min,100-year,1pct_plu,500-year
River Rch & RM= UNT 1011 IN LATR,Reach-1,4166
     825    1194    1514    1406    1901    2571    3008
Boundary for River Rch & Prof#=UNT 1011 IN LATR,Reach-1,1
Up Type=0
Dn Type=3
Dn Slope=0.005
Boundary for River Rch & Prof#=UNT 1011 IN LATR,Reach-1,2
Up Type=0
Dn Type=3
Dn Slope=0.005
Boundary for River Rch & Prof#=UNT 1011 IN LATR,Reach-1,3
Up Type=0
Dn Type=3
Dn Slope=0.005
Boundary for River Rch & Prof#=UNT 1011 IN LATR,Reach-1,4
Up Type=0
Dn Type=3
Dn Slope=0.005
Boundary for River Rch & Prof#=UNT 1011 IN LATR,Reach-1,5
Up Type=0
Dn Type=3
Dn Slope=0.005
Boundary for River Rch & Prof#=UNT 1011 IN LATR,Reach-1,6
Up Type=0
Dn Type=3
Dn Slope=0.005
Boundary for River Rch & Prof#=UNT 1011 IN LATR,Reach-1,7
Up Type=0
Dn Type=3
Dn Slope=0.005

--- UNT 0011 IN LATR.g01 (geometry) ---

Geom Title=Existing Conditions

River Reach=UNT 1011 IN LATR,Reach-1
Reach XY= 30
      2922108.23     10130344.01      2922155.41     10130277.43
      2922287.70     10130168.53      2922285.61     10130085.07
      2922223.19     10129967.17      2922219.65     10129834.13
      2922324.71     10129722.13      2922355.88     10129548.19
      2922343.03     10129471.31      2922249.61     10129333.36
      2922298.68     10129113.94      2922210.33     10128897.96
      2922213.88     10128731.26      2922267.80     10128643.44
      2922360.07     10128590.71      2922426.74     10128508.42
      2922665.54     10128312.33      2922651.31     10128219.29
      2922696.73     10128012.84      2922697.75     10127836.72
      2922773.79     10127729.43      2922835.77     10127740.89
      2922843.57     10127795.48      2922876.56     10127801.99
      2923011.29     10127722.14      2923131.69     10127698.35
      2923354.06     10127501.29      2923392.29     10127441.95
      2923607.39     10127302.55      2923621.11     10127197.19

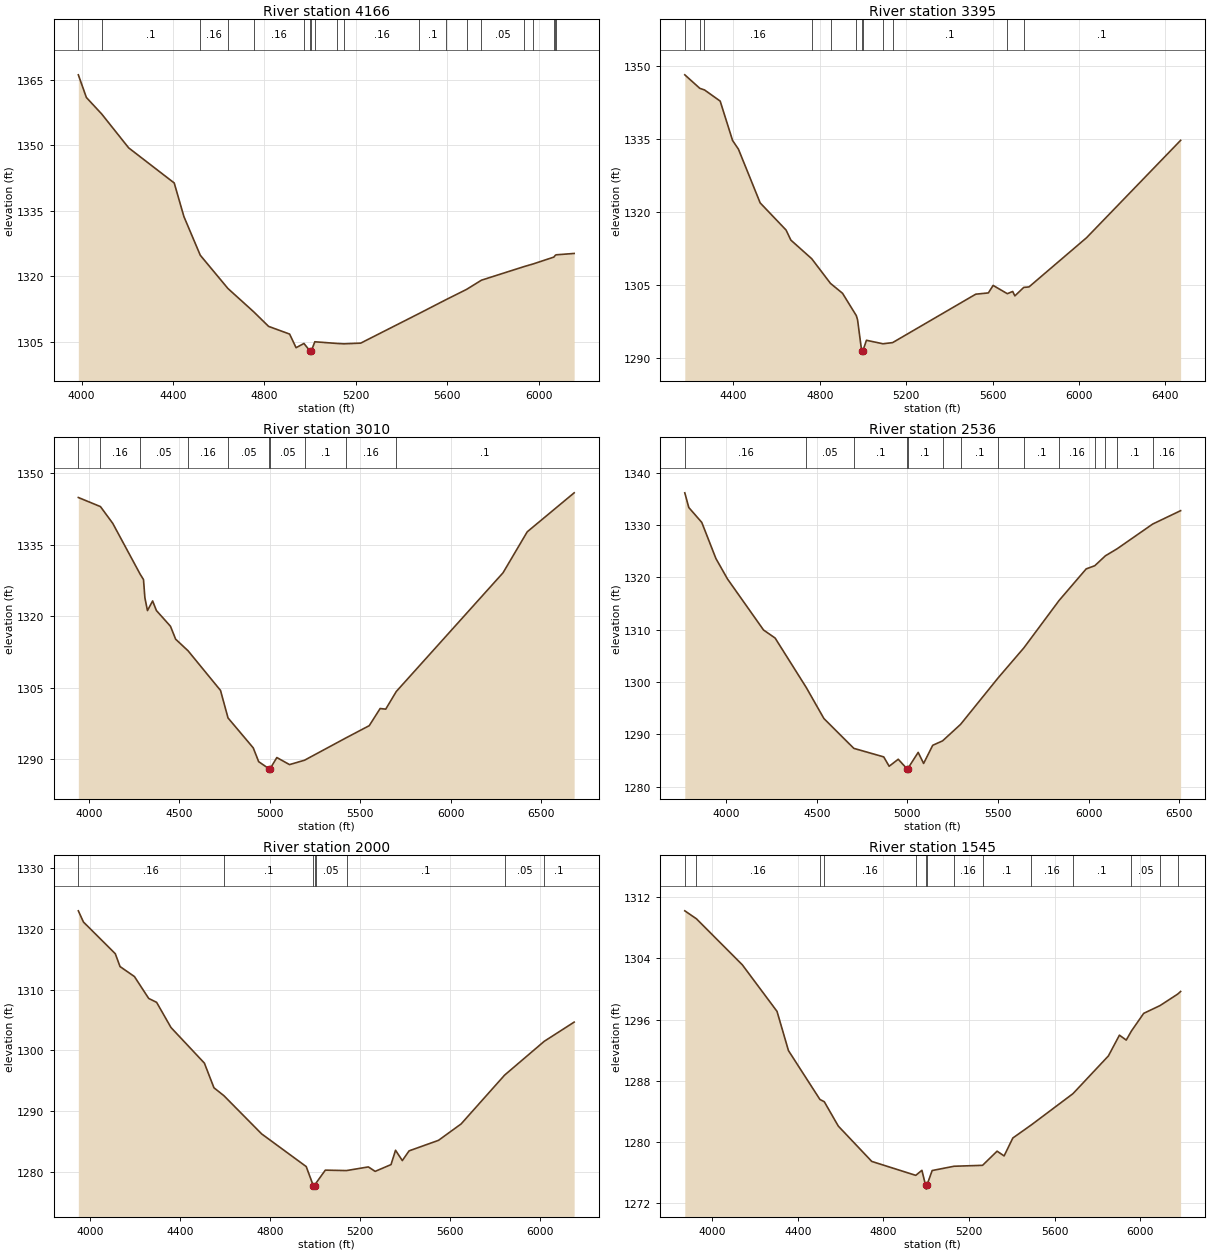
Type RM Length L Ch R = 1,4166,771,771,771
BEGIN DESCRIPTION:
UNT 1011 IN LATR 6.0
END DESCRIPTION:
XS GIS Cut Line= 4
      2923072.86     10130644.86      2922374.09     10130479.93
      2921987.80     10130093.64      2921085.01     10130154.41
#Sta/Elev= 30
  3986.1 1366.07  4021.4 1360.88  4088.1 1357.12  4206.4 1349.35  4405.6 1341.32
  4448.0 1333.63  4519.5 1324.79  4640.4 1317.18  4753.0 1311.85  4818.5 1308.50
  4910.4 1306.74  4938.7 1303.62  4973.1 1304.59  4999.3 1302.88  5002.1 1302.38
  5005.3 1302.88  5020.7 1304.98  5118.3 1304.59  5148.9 1304.51  5221.5 1304.67
  5477.0 1311.45  5596.6 1314.67  5685.0 1316.98  5749.5 1319.07  5936.4 1322.19
  5976.9 1322.81  6066.5 1324.36  6072.3 1324.74  6076.6 1324.88  6155.2 1325.19
#Mann=20,-1,0
  3986.1    0.05       0  4088.1     0.1       0  4519.5    0.16       0
  4640.4    0.05       0  4753.0    0.16       0  4973.1    0.05       0
  4999.3   0.035       0  5005.3    0.05       0  5020.7    0.16       0
  5118.3    0.05       0  5148.9    0.16       0  5477.0     0.1       0
  5596.6    0.05       0  5685.0     0.1       0  5749.5    0.05       0
  5936.4     0.1       0  5976.9    0.16       0  6066.5     0.1       0
  6072.3    0.16       0  6076.6     0.1       0
Bank Sta=4999.3,5005.3
Exp/Cntr=0.3,0.1

Type RM Length L Ch R = 1,3395,385,385,385
BEGIN DESCRIPTION:
UNT 1011 IN LATR 5.0
END DESCRIPTION:
XS GIS Cut Line= 4
      2923020.78     10130071.93      2922526.00     10129668.29
      2922161.41     10129585.83      2920885.38     10129724.72
#Sta/Elev= 30
  4174.6 1348.22  4244.1 1345.45  4265.8 1345.12  4338.4 1342.83  4395.8 1334.75
  4423.1 1332.95  4523.6 1321.93  4643.5 1316.36  4665.8 1314.29  4762.3 1310.47
  4849.3 1305.40  4904.9 1303.38  4968.8 1298.79  4974.6 1297.94  4993.4 1291.59
  4996.1 1291.09  4999.4 1291.59  5015.7 1293.73  5092.1 1293.01  5137.0 1293.25
  5521.8 1303.19  5580.3 1303.45  5602.3 1304.99  5668.1 1303.29  5692.9 1303.75
  5702.9 1302.84  5744.1 1304.58  5768.3 1304.68  6034.9 1314.78  6470.5 1334.77
#Mann=12,-1,0
  4174.6    0.05       0  4244.1     0.1       0  4265.8    0.16       0
  4762.3     0.1       0  4849.3    0.16       0  4968.8     0.1       0
  4993.4    0.07       0  4999.4     0.1       0  5092.1    0.16       0
  5137.0     0.1       0  5668.1    0.16       0  5744.1     0.1       0
Bank Sta=4993.4,4999.4
Exp/Cntr=0.3,0.1

Type RM Length L Ch R = 1,3010,474,474,474
BEGIN DESCRIPTION:
UNT 1011 IN LATR 4.0
END DESCRIPTION:
XS GIS Cut Line= 4
      2923120.58     10129820.18      2922508.63     10129295.03
      2922018.18     10129255.97      2920616.49     10129598.80
#Sta/Elev= 30
  3941.5 1344.93  4063.8 1343.02  4131.7 1339.51  4283.6 1328.82  4301.8 1327.71
  4309.5 1323.89  4323.7 1321.19  4352.3 1323.22  4373.1 1321.21  4451.0 1317.90
  4479.6 1315.19  4548.1 1312.76  4727.6 1304.44  4769.2 1298.66  4908.6 1292.38
  4938.7 1289.48  4995.8 1288.00  4998.6 1287.50  5001.8 1288.00  5039.0 1290.35
  5109.2 1288.87  5192.3 1289.79  5422.1 1294.49  5549.9 1297.04  5610.2 1300.64
  5641.1 1300.51  5699.4 1304.21  6289.7 1329.13  6423.5 1337.73  6682.9 1345.91
#Mann=10,-1,0
  3941.5    0.05       0  4063.8    0.16       0  4283.6    0.05       0
  4548.1    0.16       0  4769.2    0.05       0  4995.8    0.04       0
  5001.8    0.05       0  5192.3     0.1       0  5422.1    0.16       0
  5699.4     0.1       0
Bank Sta=4995.8,5001.8
Exp/Cntr=0.3,0.1

Type RM Length L Ch R = 1,2536,536,536,536
BEGIN DESCRIPTION:
UNT 1011 IN LATR 3.0
END DESCRIPTION:
XS GIS Cut Line= 4
      2923224.78     10129399.20      2922539.02     10128821.94
      2921848.91     10128834.96      2920768.18     10129221.25
#Sta/Elev= 30
  3772.3 1336.14  3794.4 1333.33  3865.9 1330.49  3943.9 1323.59  4007.6 1319.69
  4206.6 1309.93  4270.3 1308.40  4442.4 1298.93  4539.6 1293.01  4704.4 1287.32
  4869.3 1285.69  4899.3 1283.90  4949.3 1285.24  4996.3 1283.47  4999.0 1282.97
  5002.3 1283.47  5059.3 1286.55  5089.3 1284.44  5139.3 1287.90  5194.2 1288.76
  5293.0 1291.90  5500.8 1300.81  5642.4 1306.53  5836.3 1315.57  5985.9 1321.61
  6033.0 1322.21  6091.8 1324.11  6156.4 1325.45  6352.3 1330.17  6506.6 1332.73
#Mann=14,-1,0
  3772.3    0.16       0  4442.4    0.05       0  4704.4     0.1       0
  4996.3    0.07       0  5002.3     0.1       0  5194.2    0.16       0
  5293.0     0.1       0  5500.8    0.16       0  5642.4     0.1       0
  5836.3    0.16       0  6033.0     0.1       0  6091.8    0.16       0
  6156.4     0.1       0  6352.3    0.16       0
Bank Sta=4996.3,5002.3
Exp/Cntr=0.3,0.1

Type RM Length L Ch R = 1,2000,455,455,455
BEGIN DESCRIPTION:
Mapping XS 9eca658a
END DESCRIPTION:
XS GIS Cut Line= 3
      2923291.02     10129163.46      2922390.40     10128314.92
      2921429.05     10128421.25
#Sta/Elev= 30
  3949.0 1322.94  3971.8 1321.10  4113.4 1315.89  4134.4 1313.78  4198.4 1312.14
  4261.9 1308.54  4297.1 1307.90  4361.0 1303.76  4509.5 1297.91  4552.0 1293.86
  4596.2 1292.56  4764.0 1286.28  4962.2 1280.91  4994.4 1277.70  4997.2 1277.20
  5000.4 1277.70  5005.2 1278.16  5047.2 1280.32  5141.5 1280.25  5238.6 1280.85
  5268.8 1280.12  5339.3 1281.23  5359.4 1283.59  5389.6 1281.89  5419.7 1283.49
  5550.5 1285.22  5651.1 1287.92  5844.4 1295.94  6020.4 1301.49  6153.6 1304.65
#Mann=8,-1,0
  3949.0    0.16       0  4596.2     0.1       0  4994.4    0.07       0
  5000.4     0.1       0  5005.2    0.05       0  5141.5     0.1       0
  5844.4    0.05       0  6020.4     0.1       0
Bank Sta=4994.4,5000.4
Exp/Cntr=0.3,0.1

Type RM Length L Ch R = 1,1545,143,143,143
BEGIN DESCRIPTION:
UNT 1011 IN LATR 2.0
END DESCRIPTION:
XS GIS Cut Line= 4
      2923352.40     10128867.98      2922907.94     10128076.28
      2922512.11     10128048.50      2921519.10     10128242.94
#Sta/Elev= 30
  3872.3 1310.21  3926.7 1309.17  4141.2 1303.15  4303.2 1297.07  4356.7 1291.94
  4503.6 1285.56  4524.1 1285.26  4589.5 1282.08  4745.8 1277.46  4951.4 1275.64
  4980.2 1276.30  4997.2 1274.34  5000.0 1273.84  5003.2 1274.34  5028.1 1276.27
  5130.2 1276.83  5263.5 1276.95  5331.4 1278.80  5364.2 1278.18  5404.9 1280.52
  5490.7 1282.22  5686.1 1286.32  5851.5 1291.25  5903.0 1293.96  5934.8 1293.32
  5959.2 1294.51  6016.3 1296.81  6092.9 1297.83  6175.3 1299.33  6188.9 1299.67
#Mann=14,-1,0
  3872.3    0.05       0  3926.7    0.16       0  4503.6     0.1       0
  4524.1    0.16       0  4951.4     0.1       0  4997.2    0.07       0
  5003.2     0.1       0  5130.2    0.16       0  5263.5     0.1       0
  5490.7    0.16       0  5686.1     0.1       0  5959.2    0.05       0
  6092.9     0.1       0  6175.3    0.05       0
Bank Sta=4997.2,5003.2
Exp/Cntr=0.3,0.1

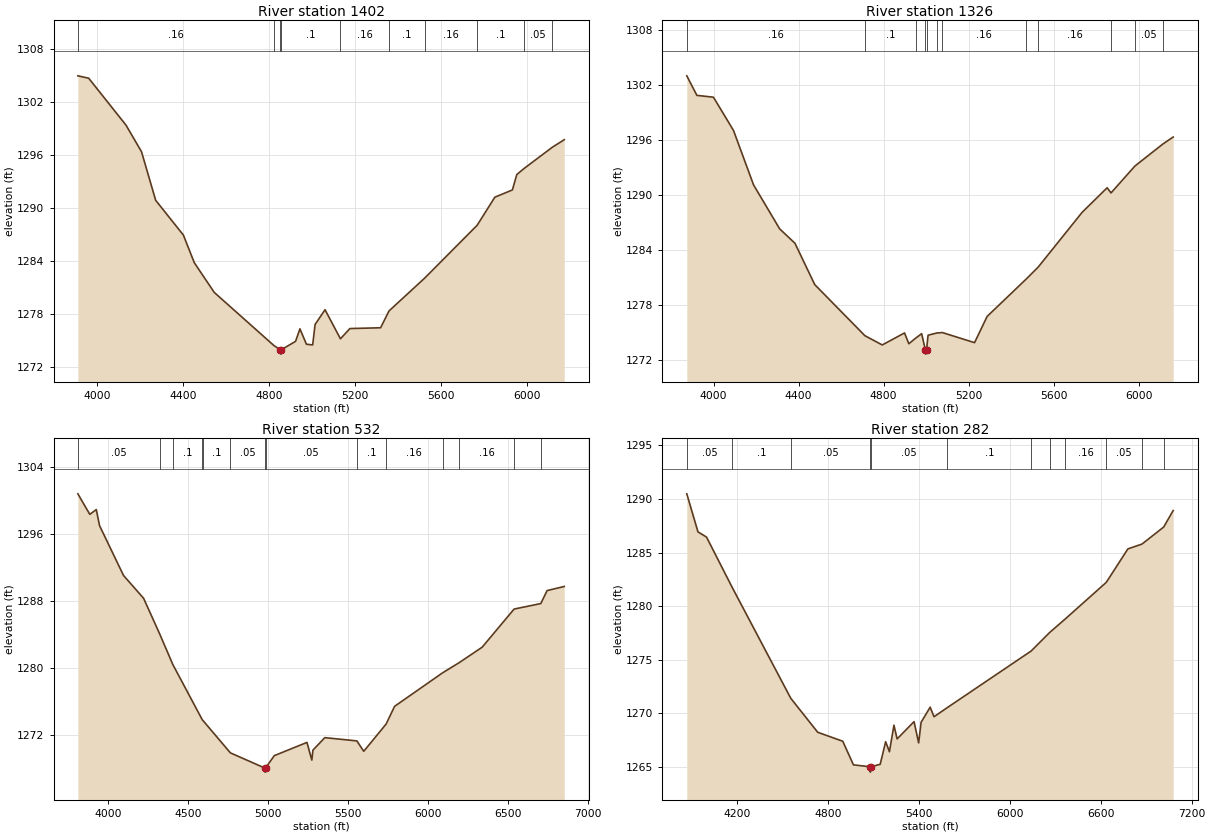
Type RM Length L Ch R = 1,1402,76,76,76
BEGIN DESCRIPTION:
Mapping XS 986853b6
END DESCRIPTION:
XS GIS Cut Line= 5
      2923369.15     10128714.25      2922846.13     10127939.49
      2922661.66     10127915.61      2922609.58     10127965.53
      2921562.40     10128186.67
#Sta/Elev= 30
  3910.6 1304.97  3961.0 1304.70  4134.8 1299.39  4206.8 1296.39  4272.7 1290.90
  4401.6 1286.97  4452.5 1283.84  4545.5 1280.48  4822.0 1274.50  4851.7 1274.01
  4854.5 1273.51  4857.7 1274.01  4923.7 1274.96  4943.9 1276.37  4974.1 1274.63
  5003.2 1274.55  5014.4 1276.86  5060.7 1278.53  5132.5 1275.24  5176.2 1276.40
  5319.3 1276.49  5358.3 1278.39  5523.8 1282.09  5768.7 1288.08  5850.8 1291.25
  5932.5 1292.07  5953.0 1293.81  5985.5 1294.47  6117.3 1296.88  6173.8 1297.75
#Mann=10,-1,0
  3910.6    0.16       0  4822.0     0.1       0  4851.7    0.07       0
  4857.7     0.1       0  5132.5    0.16       0  5358.3     0.1       0
  5523.8    0.16       0  5768.7     0.1       0  5985.5    0.05       0
  6117.3     0.1       0
Bank Sta=4851.7,4857.7
Exp/Cntr=0.3,0.1

Type RM Length L Ch R = 1,1326,794,794,794
BEGIN DESCRIPTION:
Mapping XS a7ad4738
END DESCRIPTION:
XS GIS Cut Line= 4
      2923401.68     10128655.63      2922865.66     10127863.53
      2922603.07     10127833.15      2921576.63     10128123.94
#Sta/Elev= 30
  3874.1 1302.96  3921.6 1300.83  3999.5 1300.63  4093.7 1297.01  4188.2 1291.07
  4311.0 1286.28  4382.9 1284.71  4475.8 1280.21  4711.7 1274.64  4793.4 1273.63
  4898.2 1274.94  4918.3 1273.76  4950.6 1274.37  4978.7 1274.86  4995.8 1273.13
  4998.6 1272.63  5001.8 1273.13  5008.9 1274.69  5049.5 1274.93  5076.2 1274.98
  5227.5 1273.88  5286.7 1276.74  5469.9 1280.80  5526.6 1282.11  5733.7 1288.09
  5851.1 1290.76  5869.4 1290.20  5981.8 1293.13  6113.3 1295.53  6161.7 1296.29
#Mann=12,-1,0
  3874.1    0.16       0  4711.7     0.1       0  4950.6    0.16       0
  4995.8    0.07       0  5001.8    0.16       0  5049.5     0.1       0
  5076.2    0.16       0  5469.9     0.1       0  5526.6    0.16       0
  5869.4     0.1       0  5981.8    0.05       0  6113.3     0.1       0
Bank Sta=4995.8,5001.8
Exp/Cntr=0.3,0.1

Type RM Length L Ch R = 1,532,250,250,250
BEGIN DESCRIPTION:
UNT 1011 IN LATR 1.0
END DESCRIPTION:
XS GIS Cut Line= 4
      2923581.56     10128687.43      2923428.77     10127784.61
      2923220.44     10127451.28      2921512.79     10127742.83
#Sta/Elev= 30
  3812.5 1300.82  3887.2 1298.37  3927.8 1298.94  3948.1 1297.02  4097.9 1291.07
  4223.8 1288.33  4324.6 1284.06  4406.5 1280.42  4590.9 1273.81  4595.4 1273.72
  4766.2 1269.87  4980.1 1268.07  4982.8 1267.57  4986.1 1268.07  5040.9 1269.54
  5245.0 1271.12  5275.4 1269.01  5282.4 1270.20  5356.6 1271.69  5557.0 1271.30
  5600.0 1270.06  5739.7 1273.31  5792.8 1275.43  6092.6 1279.43  6193.5 1280.61
  6340.6 1282.50  6539.9 1287.05  6707.0 1287.71  6746.4 1289.26  6853.6 1289.75
#Mann=14,-1,0
  3812.5    0.05       0  4324.6    0.16       0  4406.5     0.1       0
  4590.9    0.16       0  4595.4     0.1       0  4766.2    0.05       0
  4980.1   0.035       0  4986.1    0.05       0  5557.0     0.1       0
  5739.7    0.16       0  6092.6    0.05       0  6193.5    0.16       0
  6539.9    0.05       0  6707.0     0.1       0
Bank Sta=4980.1,4986.1
Exp/Cntr=0.3,0.1

Type RM Length L Ch R = 1,282,0,0,0
BEGIN DESCRIPTION:
Mapping XS 724664ff
END DESCRIPTION:
XS GIS Cut Line= 4
      2923751.31     10128480.28      2923499.57     10127468.99
      2923417.11     10127304.06      2921463.98     10127642.60
#Sta/Elev= 30
  3868.9 1290.49  3942.7 1286.94  3999.3 1286.45  4167.7 1281.78  4554.9 1271.41
  4732.7 1268.24  4898.0 1267.40  4968.3 1265.20  5077.1 1265.02  5079.9 1264.52
  5083.1 1265.02  5144.8 1265.25  5180.8 1267.36  5205.7 1266.42  5235.5 1268.90
  5256.5 1267.62  5368.1 1269.23  5398.5 1267.25  5414.7 1269.17  5474.4 1270.58
  5500.0 1269.69  5588.6 1270.55  6140.5 1275.82  6262.0 1277.54  6363.0 1278.78
  6636.5 1282.23  6778.8 1285.35  6871.7 1285.80  7015.1 1287.39  7077.7 1288.93
#Mann=12,-1,0
  3868.9    0.05       0  4167.7     0.1       0  4554.9    0.05       0
  5077.1    0.04       0  5083.1    0.05       0  5588.6     0.1       0
  6140.5    0.16       0  6262.0    0.05       0  6363.0    0.16       0
  6636.5    0.05       0  6871.7     0.1       0  7015.1    0.05       0
Bank Sta=5077.1,5083.1
Exp/Cntr=0.3,0.1

Chan Stop Cuts=-1