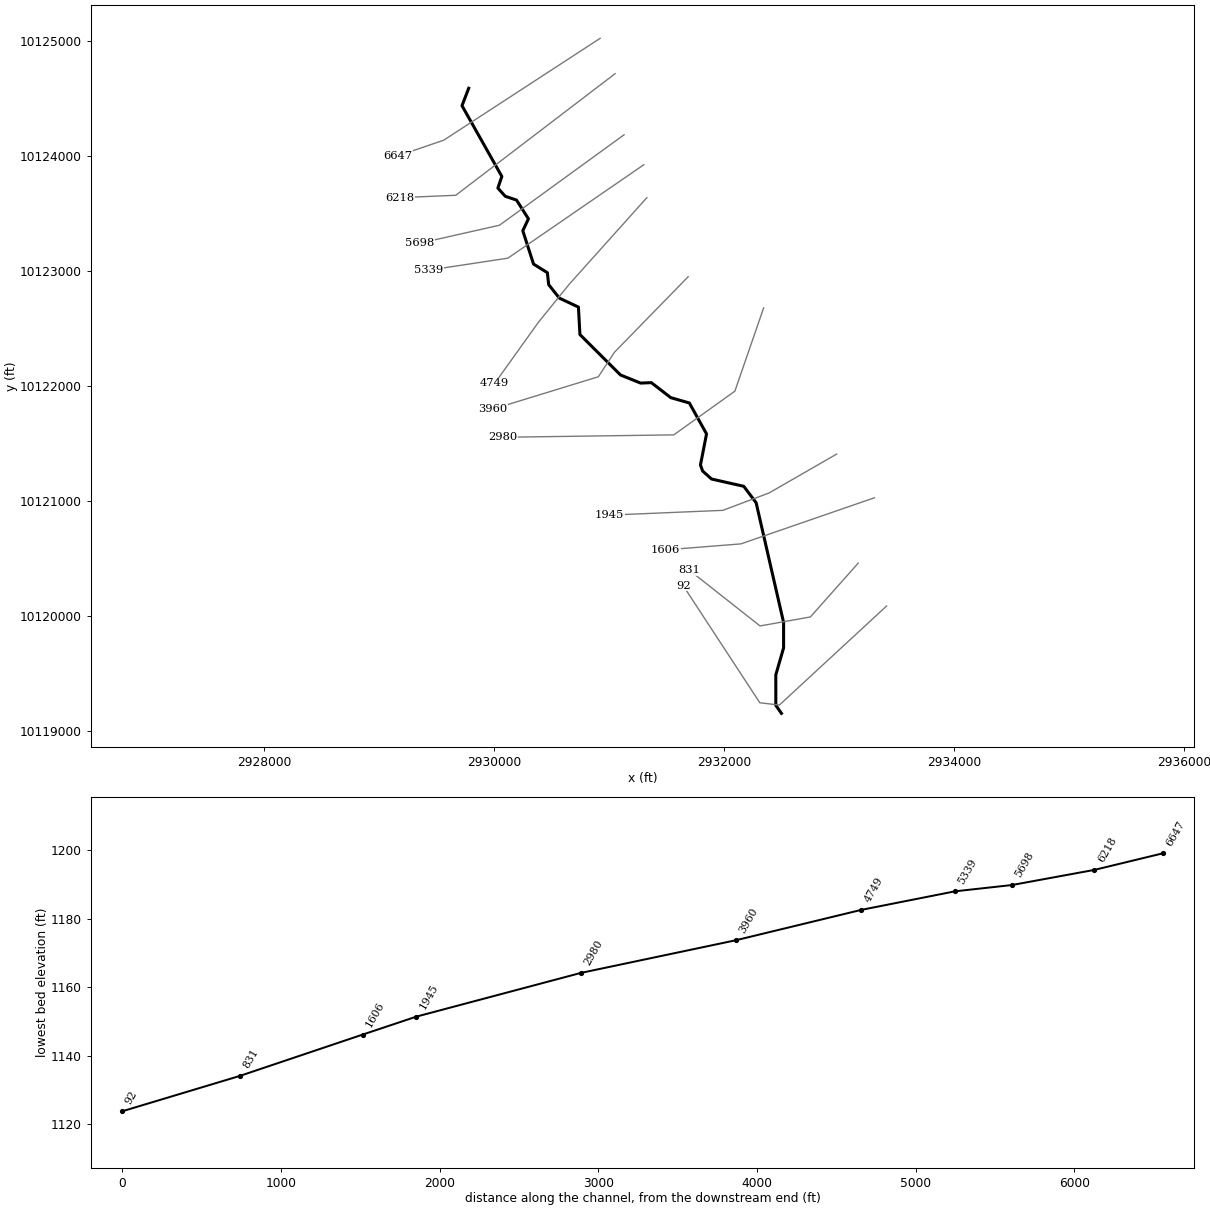
--- UNT 0012 IN LATR.prj (project) ---

Proj Title=UNT 1012 IN LATR Base Level Engineering
Current Plan=p01
Default Exp/Contr=0.3,0.1
English Units
Geom File=g01
Flow File=f01
Plan File=p01
BEGIN DESCRIPTION:
UNT 1012 IN LATR
END DESCRIPTION:

--- UNT 0012 IN LATR.p01 (plan) ---

Plan Title=Multiple Run
Short Identifier=Multiple
Geom File=g01
Flow File=f01
Subcritical Flow
K Sum by GR= 0
Std Step Tol= 0.01
Critical Tol= 0.01
Num of Std Step Trials= 20
Max Error Tol= 0.3
Flow Tol Ratio= 0.001
Split Flow NTrial= 30
Split Flow Tol= 0.02
Split Flow Ratio= 0.02
Log Output Level= 0
Friction Slope Method= 1
Unsteady Friction Slope Method= 2
Unsteady Bridges Friction Slope Method= 1
Parabolic Critical Depth
Global Vel Dist=  1 , 1 , 1
Global Log Level= 0
CheckData=True
Encroach Param= -1, 0, 0, 0
BEGIN DESCRIPTION:
Multiple Run
END DESCRIPTION:

--- UNT 0012 IN LATR.f01 (steady flow) ---

Flow Title=Multiple
Number of Profiles=7
Profile Names=10-year,25-year,50-year,1pct_min,100-year,1pct_plu,500-year
River Rch & RM= UNT 1012 IN LATR,Reach-1,6647
     846    1225    1553    1442    1950    2637    3085
River Rch & RM= UNT 1012 IN LATR,Reach-1,5698
    1327    1965    2530    2380    3219    4353    5235
Boundary for River Rch & Prof#=UNT 1012 IN LATR,Reach-1,1
Up Type=0
Dn Type=3
Dn Slope=0.005
Boundary for River Rch & Prof#=UNT 1012 IN LATR,Reach-1,2
Up Type=0
Dn Type=3
Dn Slope=0.005
Boundary for River Rch & Prof#=UNT 1012 IN LATR,Reach-1,3
Up Type=0
Dn Type=3
Dn Slope=0.005
Boundary for River Rch & Prof#=UNT 1012 IN LATR,Reach-1,4
Up Type=0
Dn Type=3
Dn Slope=0.005
Boundary for River Rch & Prof#=UNT 1012 IN LATR,Reach-1,5
Up Type=0
Dn Type=3
Dn Slope=0.005
Boundary for River Rch & Prof#=UNT 1012 IN LATR,Reach-1,6
Up Type=0
Dn Type=3
Dn Slope=0.005
Boundary for River Rch & Prof#=UNT 1012 IN LATR,Reach-1,7
Up Type=0
Dn Type=3
Dn Slope=0.005

--- UNT 0012 IN LATR.g01 (geometry) ---

Geom Title=Existing Conditions

River Reach=UNT 1012 IN LATR,Reach-1
Reach XY= 30
      2929778.97     10124588.95      2929720.84     10124437.73
      2930067.20     10123822.37      2930032.72     10123721.27
      2930097.12     10123649.91      2930194.87     10123617.04
      2930298.36     10123454.05      2930249.40     10123350.41
      2930342.86     10123060.59      2930463.20     10122985.46
      2930474.52     10122881.56      2930567.45     10122764.42
      2930733.20     10122686.58      2930746.26     10122447.60
      2931099.23     10122096.03      2931274.01     10122025.62
      2931367.13     10122029.56      2931535.96     10121899.13
      2931697.70     10121852.61      2931847.10     10121583.70
      2931794.18     10121313.58      2931813.14     10121260.82
      2931891.04     10121191.39      2932171.15     10121128.12
      2932278.48     10120984.62      2932517.23     10119943.70
      2932517.17     10119723.50      2932449.35     10119488.57
      2932449.53     10119223.75      2932498.47     10119153.73

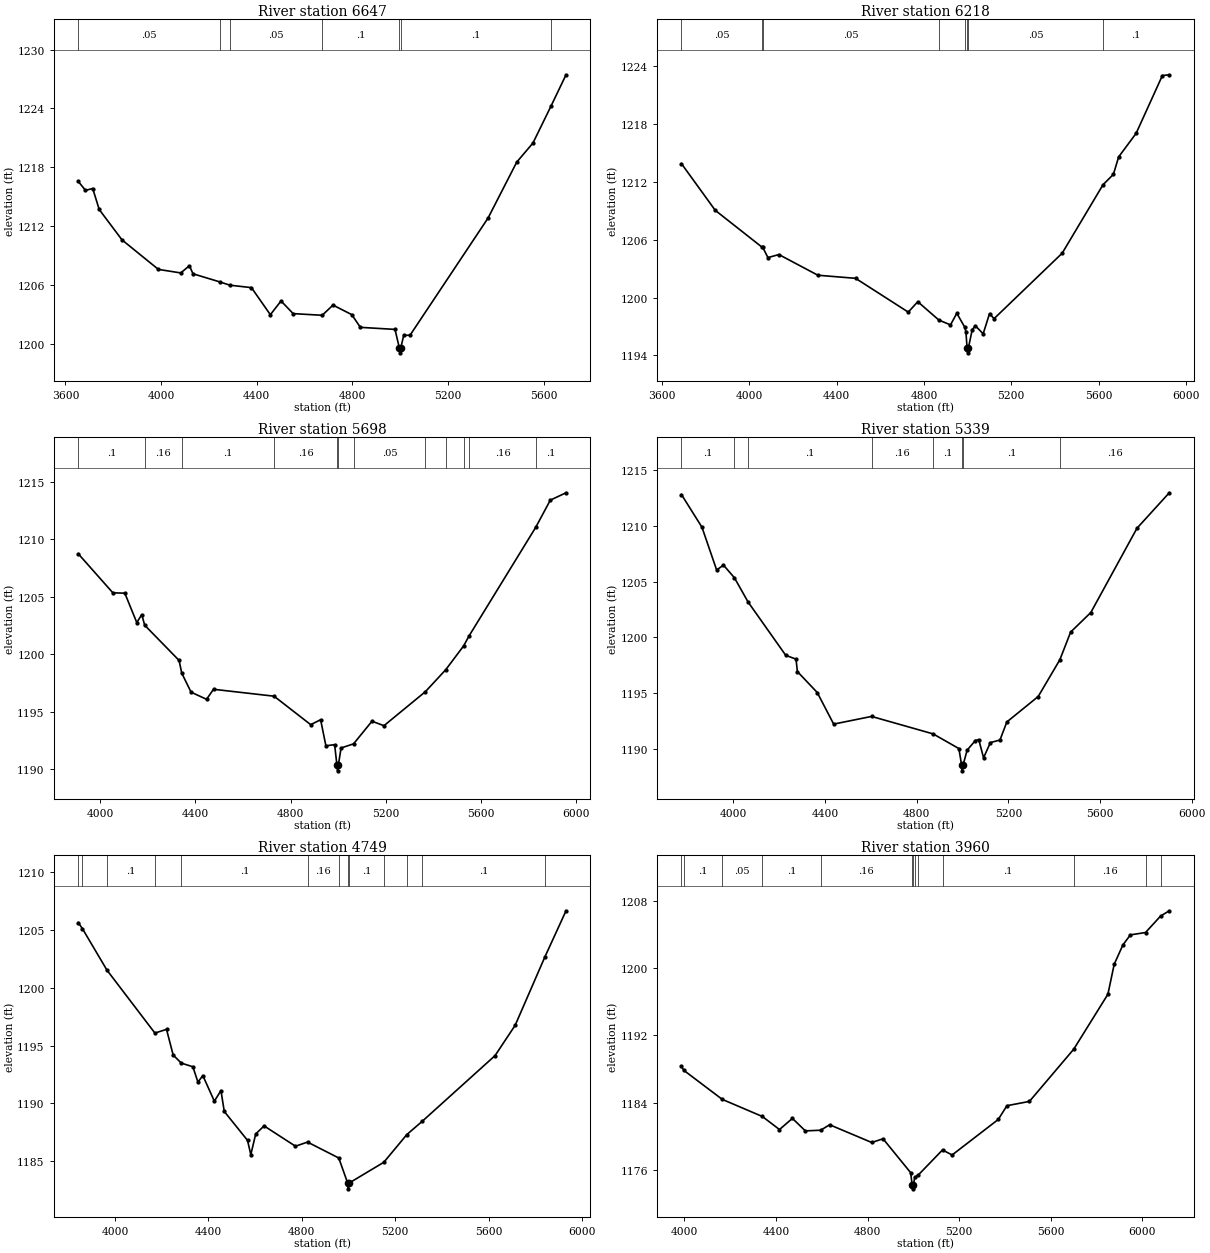
Type RM Length L Ch R = 1,6647,429,429,429
BEGIN DESCRIPTION:
UNT 1012 IN LATR 12.0
END DESCRIPTION:
XS GIS Cut Line= 3
      2930921.87     10125023.36      2929562.45     10124137.91
      2929166.63     10124002.50
#Sta/Elev= 30
  3653.5 1216.56  3683.8 1215.64  3714.1 1215.83  3741.2 1213.69  3836.6 1210.59
  3988.8 1207.58  4082.3 1207.22  4118.5 1207.95  4133.7 1207.13  4245.0 1206.31
  4288.1 1205.97  4378.1 1205.72  4457.2 1202.96  4501.9 1204.36  4552.6 1203.07
  4674.1 1202.90  4719.2 1203.94  4797.6 1202.97  4833.8 1201.67  4978.7 1201.46
  4996.8 1199.57  4999.6 1199.07  5002.8 1199.57  5015.0 1200.84  5042.0 1200.88
  5368.0 1212.82  5487.9 1218.52  5555.8 1220.47  5631.0 1224.22  5694.2 1227.43
#Mann=7,-1,0
  3653.5    0.05       0  4245.0     0.1       0  4288.1    0.05       0
  4674.1     0.1       0  4996.8    0.07       0  5002.8     0.1       0
  5631.0    0.05       0
Bank Sta=4996.8,5002.8
Exp/Cntr=0.3,0.1

Type RM Length L Ch R = 1,6218,520,520,520
BEGIN DESCRIPTION:
UNT 1012 IN LATR 11.0
END DESCRIPTION:
XS GIS Cut Line= 3
      2931052.00     10124716.01      2929666.62     10123658.75
      2929176.99     10123637.91
#Sta/Elev= 30
  3690.2 1213.91  3844.9 1209.06  4060.4 1205.21  4061.9 1205.23  4086.1 1204.15
  4136.0 1204.47  4314.7 1202.32  4487.1 1202.00  4728.3 1198.49  4771.9 1199.57
  4868.1 1197.67  4921.6 1197.16  4950.6 1198.37  4985.9 1196.96  4992.3 1196.45
  4997.5 1194.76  5000.3 1194.26  5003.5 1194.76  5021.3 1196.68  5035.9 1197.06
  5071.2 1196.24  5100.3 1198.33  5121.1 1197.81  5432.9 1204.61  5619.8 1211.72
  5667.4 1212.80  5691.3 1214.61  5771.4 1217.06  5891.5 1223.06  5923.0 1223.14
#Mann=8,-1,0
  3690.2    0.05       0  4060.4     0.1       0  4061.9    0.05       0
  4868.1    0.16       0  4985.9    0.05       0  4997.5   0.035       0
  5003.5    0.05       0  5619.8     0.1       0
Bank Sta=4997.5,5003.5
Exp/Cntr=0.3,0.1

Type RM Length L Ch R = 1,5698,359,359,359
BEGIN DESCRIPTION:
UNT 1012 IN LATR 10.0
END DESCRIPTION:
XS GIS Cut Line= 3
      2931130.20     10124184.82      2930046.83     10123398.33
      2929354.09     10123242.07
#Sta/Elev= 30
  3908.4 1208.74  4053.8 1205.34  4104.0 1205.31  4154.3 1202.75  4175.2 1203.44
  4187.5 1202.52  4332.1 1199.45  4343.1 1198.35  4382.3 1196.69  4447.3 1196.07
  4476.6 1196.94  4730.8 1196.34  4884.8 1193.86  4926.5 1194.29  4948.6 1192.02
  4985.3 1192.12  4995.0 1190.34  4997.7 1189.84  5001.0 1190.34  5012.3 1191.83
  5064.8 1192.19  5142.2 1194.16  5192.5 1193.77  5366.4 1196.73  5451.8 1198.64
  5527.2 1200.72  5550.9 1201.62  5829.9 1211.04  5891.3 1213.41  5957.3 1214.05
#Mann=12,-1,0
  3908.4     0.1       0  4187.5    0.16       0  4343.1     0.1       0
  4730.8    0.16       0  4995.0    0.07       0  5001.0    0.16       0
  5064.8    0.05       0  5366.4     0.1       0  5451.8    0.05       0
  5527.2     0.1       0  5550.9    0.16       0  5829.9     0.1       0
Bank Sta=4995,5001
Exp/Cntr=0.3,0.1

Type RM Length L Ch R = 1,5339,590,590,590
BEGIN DESCRIPTION:
UNT 1012 IN LATR 9.0
END DESCRIPTION:
XS GIS Cut Line= 3
      2931302.03     10123924.37      2930119.75     10123111.87
      2929432.84     10123007.79
#Sta/Elev= 30
  3772.9 1212.83  3862.2 1209.90  3926.5 1206.05  3956.3 1206.49  4004.1 1205.35
  4063.8 1203.17  4228.2 1198.38  4272.9 1198.04  4279.0 1196.92  4365.6 1195.04
  4437.3 1192.20  4602.7 1192.89  4871.5 1191.32  4984.0 1190.00  4995.9 1188.50
  4998.6 1188.00  5001.9 1188.50  5019.9 1189.86  5055.7 1190.72  5070.6 1190.81
  5091.6 1189.17  5121.4 1190.54  5163.3 1190.77  5193.1 1192.39  5330.1 1194.68
  5424.6 1197.98  5471.7 1200.47  5559.9 1202.23  5761.2 1209.80  5902.2 1212.99
#Mann=8,-1,0
  3772.9     0.1       0  4004.1    0.16       0  4063.8     0.1       0
  4602.7    0.16       0  4871.5     0.1       0  4995.9    0.07       0
  5001.9     0.1       0  5424.6    0.16       0
Bank Sta=4995.9,5001.9
Exp/Cntr=0.3,0.1

Type RM Length L Ch R = 1,4749,789,789,789
BEGIN DESCRIPTION:
UNT 1012 IN LATR 8.0
END DESCRIPTION:
XS GIS Cut Line= 4
      2931328.08     10123637.92      2930651.00     10122882.70
      2930385.37     10122554.58      2930005.19     10122023.37
#Sta/Elev= 30
  3842.2 1205.65  3860.2 1205.12  3965.2 1201.53  4170.6 1196.08  4220.4 1196.40
  4248.8 1194.18  4283.6 1193.48  4333.3 1193.16  4355.0 1191.83  4375.9 1192.40
  4425.3 1190.18  4453.6 1191.10  4467.8 1189.29  4567.3 1186.79  4581.5 1185.55
  4602.4 1187.34  4638.3 1188.04  4772.9 1186.28  4824.4 1186.64  4958.3 1185.26
  4996.4 1183.09  4999.1 1182.59  5002.4 1183.09  5151.3 1184.89  5249.9 1187.29
  5316.5 1188.45  5627.9 1194.13  5713.9 1196.75  5841.4 1202.68  5931.9 1206.67
#Mann=13,-1,0
  3842.2     0.1       0  3860.2    0.16       0  3965.2     0.1       0
  4170.6    0.16       0  4283.6     0.1       0  4824.4    0.16       0
  4958.3     0.1       0  4996.4    0.07       0  5002.4     0.1       0
  5151.3    0.16       0  5249.9    0.05       0  5316.5     0.1       0
  5841.4    0.16       0
Bank Sta=4996.4,5002.4
Exp/Cntr=0.3,0.1

Type RM Length L Ch R = 1,3960,980,980,980
BEGIN DESCRIPTION:
UNT 1012 IN LATR 6.0
END DESCRIPTION:
XS GIS Cut Line= 4
      2931687.45     10122950.41      2931046.83     10122294.16
      2930906.20     10122080.62      2929989.56     10121799.38
#Sta/Elev= 30
  3986.8 1188.36  3996.1 1187.87  4165.2 1184.39  4339.9 1182.36  4415.2 1180.80
  4471.6 1182.13  4528.2 1180.64  4595.2 1180.72  4634.3 1181.37  4818.2 1179.26
  4867.7 1179.70  4988.5 1175.66  4994.6 1174.24  4997.3 1173.74  5000.6 1174.24
  5006.4 1175.11  5021.4 1175.38  5127.5 1178.37  5169.5 1177.77  5371.1 1182.00
  5409.1 1183.64  5507.3 1184.15  5701.0 1190.37  5850.3 1196.91  5877.8 1200.48
  5915.8 1202.78  5948.5 1203.98  6014.6 1204.26  6080.5 1206.22  6118.4 1206.85
#Mann=13,-1,0
  3986.8    0.05       0  3996.1     0.1       0  4165.2    0.05       0
  4339.9     0.1       0  4595.2    0.16       0  4994.6    0.07       0
  5000.6    0.16       0  5006.4     0.1       0  5021.4    0.16       0
  5127.5     0.1       0  5701.0    0.16       0  6014.6     0.1       0
  6080.5    0.16       0
Bank Sta=4994.6,5000.6
Exp/Cntr=0.3,0.1

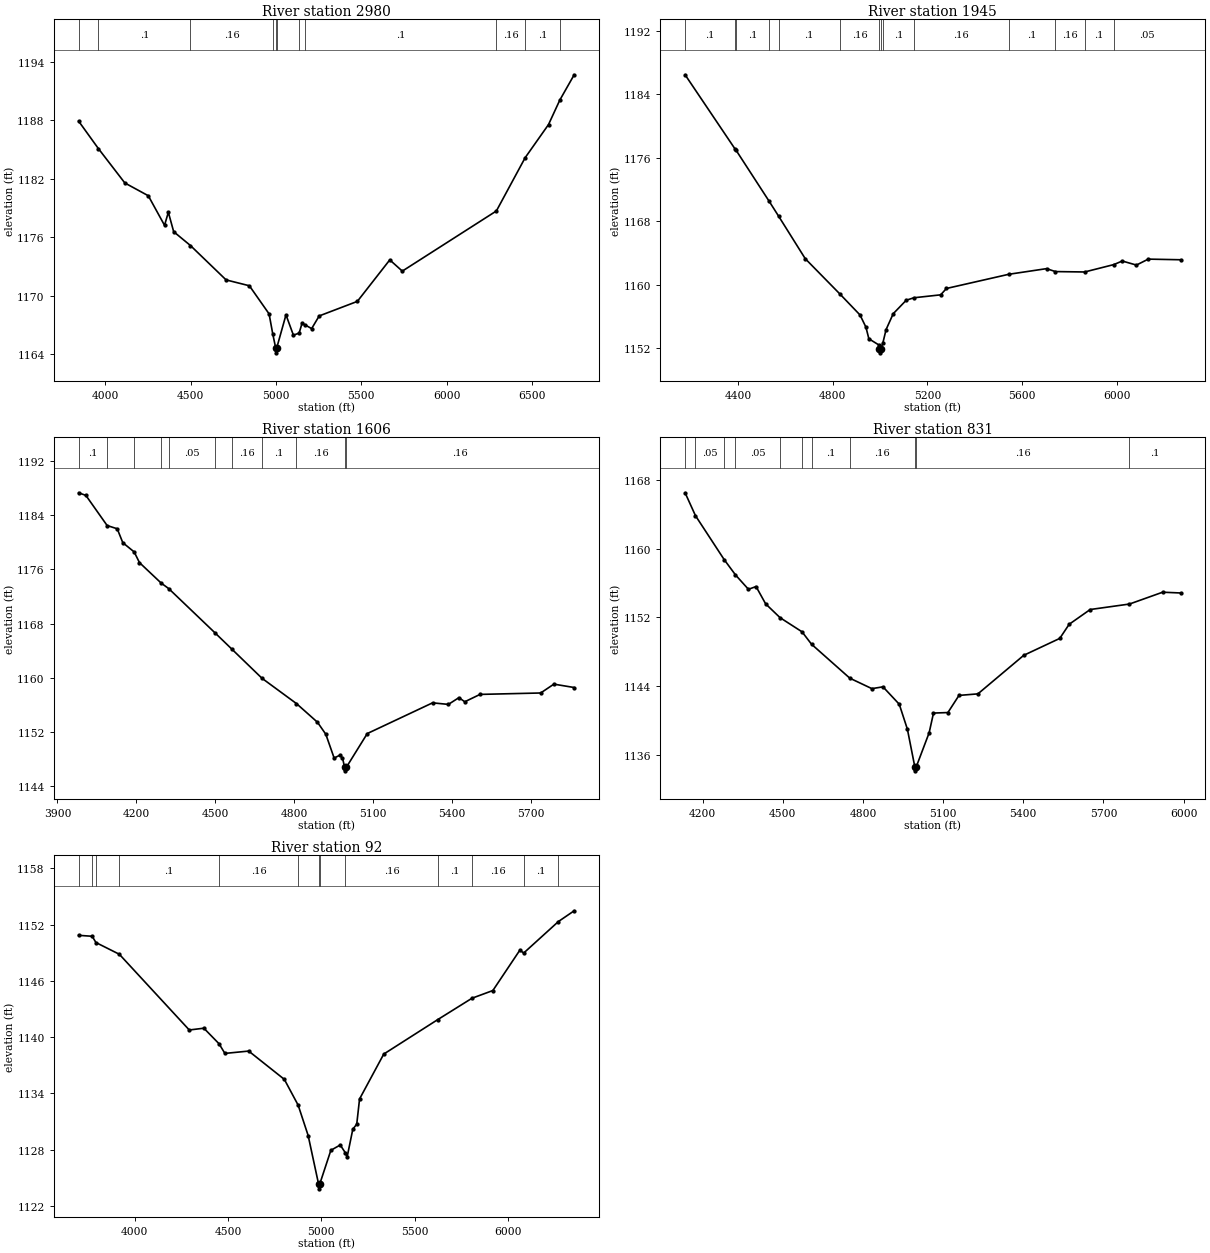
Type RM Length L Ch R = 1,2980,1035,1035,1035
BEGIN DESCRIPTION:
UNT 1012 IN LATR 5.0
END DESCRIPTION:
XS GIS Cut Line= 4
      2932343.70     10122679.57      2932093.70     10121955.62
      2931562.45     10121575.41      2930078.09     10121554.58
#Sta/Elev= 30
  3843.4 1187.90  3959.2 1185.09  4114.1 1181.57  4251.6 1180.26  4346.8 1177.23
  4369.1 1178.57  4400.3 1176.58  4498.6 1175.16  4707.5 1171.64  4843.9 1171.04
  4959.4 1168.16  4981.2 1166.08  4998.1 1164.67  5000.9 1164.17  5004.1 1164.67
  5058.4 1168.06  5101.9 1165.98  5135.5 1166.19  5152.2 1167.18  5170.8 1167.03
  5208.7 1166.65  5253.0 1167.95  5476.6 1169.44  5666.6 1173.69  5740.1 1172.54
  6291.2 1178.70  6460.0 1184.16  6596.7 1187.55  6663.0 1190.06  6747.1 1192.65
#Mann=11,-1,0
  3843.4    0.16       0  3959.2     0.1       0  4498.6    0.16       0
  4981.2     0.1       0  4998.1    0.07       0  5004.1     0.1       0
  5135.5    0.16       0  5170.8     0.1       0  6291.2    0.16       0
  6460.0     0.1       0  6663.0    0.16       0
Bank Sta=4998.1,5004.1
Exp/Cntr=0.3,0.1

Type RM Length L Ch R = 1,1945,339,339,339
BEGIN DESCRIPTION:
UNT 1012 IN LATR 4.0
END DESCRIPTION:
XS GIS Cut Line= 4
      2932979.16     10121408.77      2932390.58     10121070.20
      2931989.54     10120919.16      2931001.67     10120877.57
#Sta/Elev= 30
  4174.9 1186.47  4385.3 1177.16  4389.2 1177.02  4530.9 1170.51  4570.1 1168.67
  4683.3 1163.29  4829.9 1158.84  4914.9 1156.20  4939.8 1154.67  4952.3 1153.20
  4994.8 1152.42  4997.2 1151.93  4999.9 1151.43  5003.2 1151.93  5011.5 1152.67
  5025.1 1154.36  5055.3 1156.36  5110.4 1158.06  5142.8 1158.37  5256.1 1158.74
  5280.4 1159.54  5544.3 1161.33  5703.9 1162.04  5741.5 1161.67  5865.1 1161.62
  5988.5 1162.55  6024.2 1163.00  6084.2 1162.49  6134.3 1163.24  6271.2 1163.16
#Mann=14,-1,0
  4174.9     0.1       0  4385.3    0.16       0  4389.2     0.1       0
  4530.9    0.05       0  4570.1     0.1       0  4829.9    0.16       0
  4997.2    0.07       0  5003.2    0.16       0  5011.5     0.1       0
  5142.8    0.16       0  5544.3     0.1       0  5741.5    0.16       0
  5865.1     0.1       0  5988.5    0.05       0
Bank Sta=4997.2,5003.2
Exp/Cntr=0.3,0.1

Type RM Length L Ch R = 1,1606,775,775,775
BEGIN DESCRIPTION:
UNT 1012 IN LATR 3.0
END DESCRIPTION:
XS GIS Cut Line= 3
      2933307.24     10121028.53      2932145.79     10120627.50
      2931491.48     10120575.57
#Sta/Elev= 30
  3980.7 1187.36  4008.3 1186.97  4089.1 1182.51  4127.5 1182.03  4148.7 1179.97
  4192.0 1178.60  4212.1 1177.02  4294.9 1173.98  4323.4 1173.17  4500.7 1166.57
  4563.2 1164.22  4678.5 1159.88  4809.4 1156.14  4889.2 1153.38  4921.0 1151.60
  4952.7 1148.07  4973.9 1148.49  4984.4 1148.10  4992.7 1146.68  4995.5 1146.18
  4998.7 1146.68  5078.7 1151.70  5327.1 1156.25  5387.3 1156.02  5427.4 1157.02
  5449.6 1156.41  5507.7 1157.50  5738.4 1157.71  5788.6 1159.02  5865.8 1158.52
#Mann=11,-1,0
  3980.7     0.1       0  4089.1    0.16       0  4192.0    0.05       0
  4294.9    0.16       0  4323.4    0.05       0  4500.7     0.1       0
  4563.2    0.16       0  4678.5     0.1       0  4809.4    0.16       0
  4992.7    0.07       0  4998.7    0.16       0
Bank Sta=4992.7,4998.7
Exp/Cntr=0.3,0.1

Type RM Length L Ch R = 1,831,739,739,739
BEGIN DESCRIPTION:
UNT 1012 IN LATR 2.0
END DESCRIPTION:
XS GIS Cut Line= 4
      2933166.59     10120460.79      2932749.95     10119992.08
      2932312.45     10119913.95      2931697.84     10120398.36
#Sta/Elev= 30
  4134.8 1166.54  4173.6 1163.87  4281.1 1158.74  4323.3 1156.96  4371.8 1155.28
  4400.3 1155.60  4436.2 1153.58  4490.1 1151.97  4572.3 1150.32  4607.9 1148.87
  4751.1 1144.91  4833.7 1143.69  4875.2 1143.90  4936.1 1141.87  4966.6 1138.95
  4994.1 1134.60  4996.8 1134.10  5000.1 1134.60  5047.9 1138.54  5064.2 1140.84
  5118.1 1140.90  5159.6 1142.90  5230.4 1143.08  5402.0 1147.58  5536.6 1149.55
  5571.9 1151.20  5650.5 1152.92  5797.5 1153.56  5921.5 1154.94  5988.9 1154.85
#Mann=11,-1,0
  4134.8     0.1       0  4173.6    0.05       0  4281.1     0.1       0
  4323.3    0.05       0  4490.1     0.1       0  4572.3    0.05       0
  4607.9     0.1       0  4751.1    0.16       0  4994.1    0.07       0
  5000.1    0.16       0  5797.5     0.1       0
Bank Sta=4994.1,5000.1
Exp/Cntr=0.3,0.1

Type RM Length L Ch R = 1,92,0,0,0
BEGIN DESCRIPTION:
UNT 1012 IN LATR 1.0
END DESCRIPTION:
XS GIS Cut Line= 4
      2933412.95     10120087.60      2932480.62     10119226.11
      2932310.59     10119245.95      2931644.65     10120263.27
#Sta/Elev= 30
  3699.2 1150.86  3771.8 1150.76  3792.0 1150.09  3917.4 1148.84  4292.3 1140.76
  4370.5 1140.95  4451.9 1139.29  4483.3 1138.26  4610.9 1138.51  4802.0 1135.49
  4876.0 1132.74  4929.6 1129.50  4985.6 1124.31  4988.3 1123.81  4991.6 1124.31
  5051.3 1127.92  5101.7 1128.49  5129.1 1127.65  5138.4 1127.19  5169.0 1130.17
  5190.1 1130.71  5205.2 1133.40  5334.9 1138.19  5623.7 1141.86  5808.1 1144.15
  5919.8 1144.97  6064.6 1149.28  6085.0 1148.97  6271.1 1152.33  6355.7 1153.48
#Mann=13,-1,0
  3699.2     0.1       0  3771.8    0.16       0  3792.0    0.05       0
  3917.4     0.1       0  4451.9    0.16       0  4876.0     0.1       0
  4985.6    0.07       0  4991.6     0.1       0  5129.1    0.16       0
  5623.7     0.1       0  5808.1    0.16       0  6085.0     0.1       0
  6271.1    0.16       0
Bank Sta=4985.6,4991.6
Exp/Cntr=0.3,0.1

Chan Stop Cuts=-1