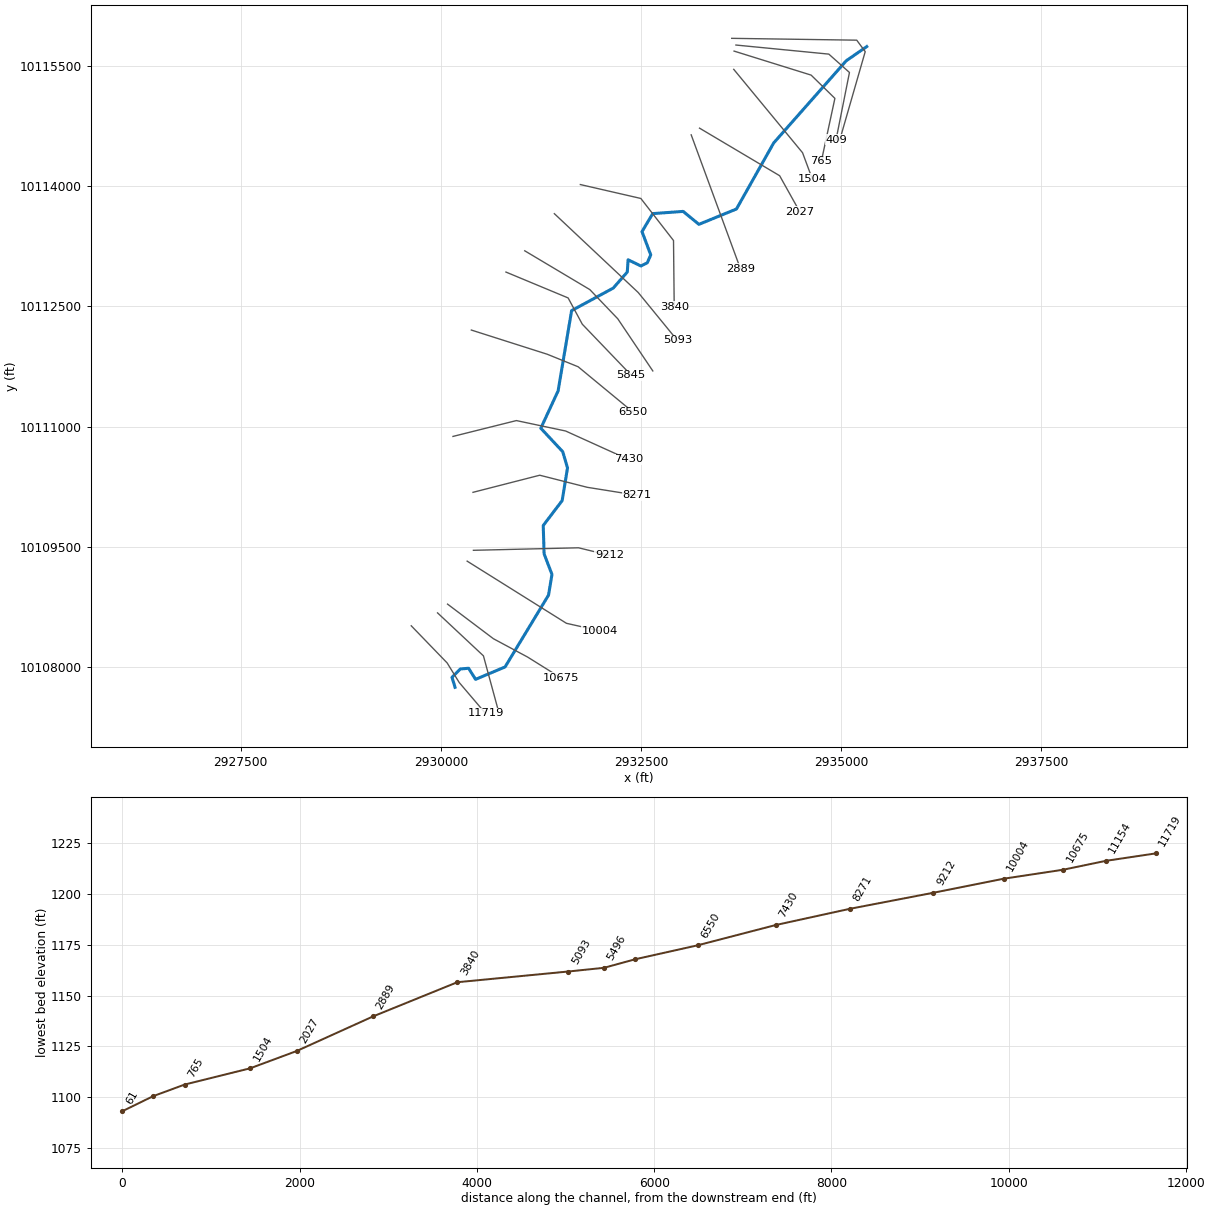
--- UNT 0013 IN LATR.prj (project) ---

Proj Title=UNT 1013 IN LATR Base Level Engineering
Current Plan=p01
Default Exp/Contr=0.3,0.1
English Units
Geom File=g01
Flow File=f01
Plan File=p01
BEGIN DESCRIPTION:
UNT 1013 IN LATR
END DESCRIPTION:

--- UNT 0013 IN LATR.p01 (plan) ---

Plan Title=Multiple Run
Short Identifier=Multiple
Geom File=g01
Flow File=f01
Subcritical Flow
K Sum by GR= 0
Std Step Tol= 0.01
Critical Tol= 0.01
Num of Std Step Trials= 20
Max Error Tol= 0.3
Flow Tol Ratio= 0.001
Split Flow NTrial= 30
Split Flow Tol= 0.02
Split Flow Ratio= 0.02
Log Output Level= 0
Friction Slope Method= 1
Unsteady Friction Slope Method= 2
Unsteady Bridges Friction Slope Method= 1
Parabolic Critical Depth
Global Vel Dist=  1 , 1 , 1
Global Log Level= 0
CheckData=True
Encroach Param= -1, 0, 0, 0
BEGIN DESCRIPTION:
Multiple Run
END DESCRIPTION:

--- UNT 0013 IN LATR.f01 (steady flow) ---

Flow Title=Multiple
Number of Profiles=7
Profile Names=10-year,25-year,50-year,1pct_min,100-year,1pct_plu,500-year
River Rch & RM= UNT 1013 IN LATR,Reach-1,11719
    1447    2152    2779    2621    3544    4793    5795
River Rch & RM= UNT 1013 IN LATR,Reach-1,5845
    1602    2392    3095    2925    3956    5350    6493
Boundary for River Rch & Prof#=UNT 1013 IN LATR,Reach-1,1
Up Type=0
Dn Type=3
Dn Slope=0.005
Boundary for River Rch & Prof#=UNT 1013 IN LATR,Reach-1,2
Up Type=0
Dn Type=3
Dn Slope=0.005
Boundary for River Rch & Prof#=UNT 1013 IN LATR,Reach-1,3
Up Type=0
Dn Type=3
Dn Slope=0.005
Boundary for River Rch & Prof#=UNT 1013 IN LATR,Reach-1,4
Up Type=0
Dn Type=3
Dn Slope=0.005
Boundary for River Rch & Prof#=UNT 1013 IN LATR,Reach-1,5
Up Type=0
Dn Type=3
Dn Slope=0.005
Boundary for River Rch & Prof#=UNT 1013 IN LATR,Reach-1,6
Up Type=0
Dn Type=3
Dn Slope=0.005
Boundary for River Rch & Prof#=UNT 1013 IN LATR,Reach-1,7
Up Type=0
Dn Type=3
Dn Slope=0.005

--- UNT 0013 IN LATR.g01 (geometry) ---

Geom Title=Existing Conditions

River Reach=UNT 1013 IN LATR,Reach-1
Reach XY= 30
      2930178.47     10107743.73      2930140.51     10107867.86
      2930244.02     10107972.44      2930347.55     10107981.72
      2930434.77     10107843.22      2930802.81     10107997.80
      2931345.41     10108894.58      2931388.52     10109153.61
      2931290.39     10109409.53      2931279.32     10109763.84
      2931515.54     10110074.84      2931582.60     10110483.68
      2931522.67     10110686.05      2931249.10     10110978.53
      2931465.33     10111445.03      2931633.48     10112446.77
      2932153.92     10112728.79      2932328.73     10112928.76
      2932339.03     10113081.85      2932498.96     10113004.23
      2932578.14     10113043.51      2932621.83     10113142.60
      2932512.53     10113433.06      2932646.34     10113658.06
      2933025.98     10113685.82      2933223.07     10113524.08
      2933691.76     10113715.68      2934156.43     10114540.34
      2935062.31     10115566.65      2935318.47     10115743.73

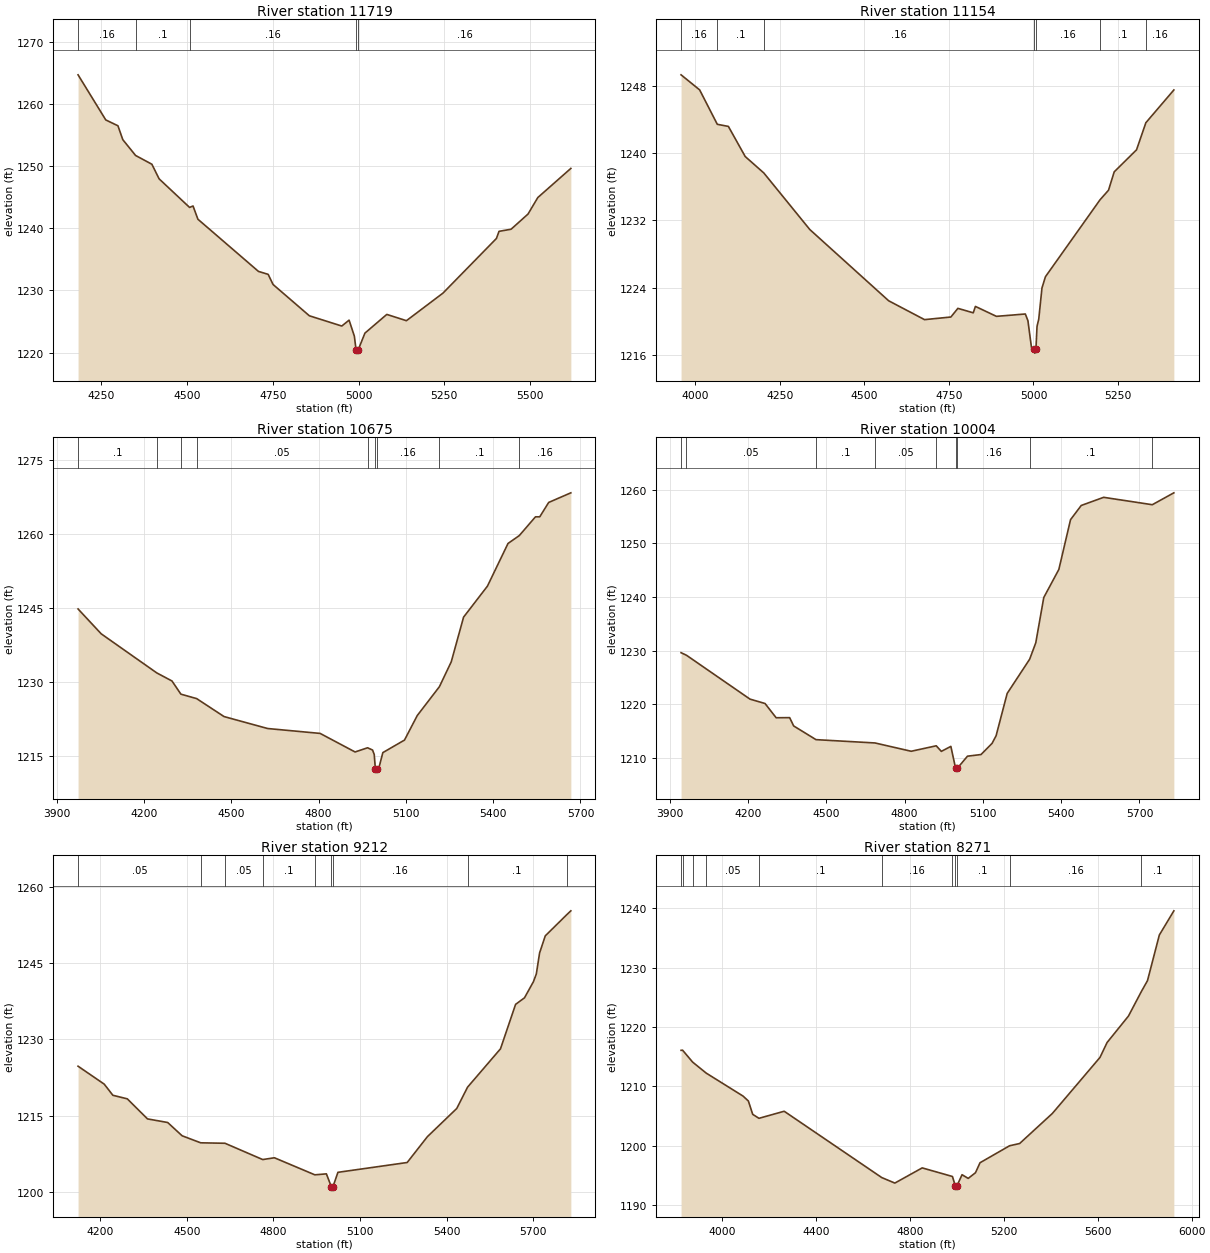
Type RM Length L Ch R = 1,11719,565,565,565
BEGIN DESCRIPTION:
UNT 1013 IN LATR 23.0
END DESCRIPTION:
XS GIS Cut Line= 4
      2929631.81     10108511.59      2930079.71     10108048.07
      2930230.75     10107803.28      2930558.50     10107418.30
#Sta/Elev= 30
  4181.7 1264.71  4262.6 1257.45  4298.1 1256.51  4312.2 1254.28  4349.6 1251.73
  4397.1 1250.32  4418.2 1247.97  4507.1 1243.37  4517.2 1243.60  4531.4 1241.47
  4708.1 1233.07  4736.4 1232.60  4750.6 1230.97  4856.6 1225.93  4951.2 1224.28
  4972.5 1225.23  4987.9 1222.64  4992.9 1220.42  4995.6 1219.92  4998.9 1220.42
  5018.7 1223.14  5082.5 1226.15  5139.8 1225.14  5246.4 1229.58  5402.3 1238.37
  5410.0 1239.52  5445.1 1239.86  5494.5 1242.30  5523.1 1244.96  5619.5 1249.65
#Mann=5,-1,0
  4181.7    0.16       0  4349.6     0.1       0  4507.1    0.16       0
  4992.9    0.07       0  4998.9    0.16       0
Bank Sta=4992.9,4998.9
Exp/Cntr=0.3,0.1

Type RM Length L Ch R = 1,11154,479,479,479
BEGIN DESCRIPTION:
UNT 1013 IN LATR 22.0
END DESCRIPTION:
XS GIS Cut Line= 3
      2929959.91     10108673.08      2930532.83     10108136.61
      2930709.48     10107487.19
#Sta/Elev= 30
  3957.5 1249.31  4012.5 1247.52  4064.7 1243.43  4097.5 1243.18  4147.3 1239.60
  4202.3 1237.65  4338.3 1230.93  4571.7 1222.46  4677.8 1220.22  4755.7 1220.53
  4776.5 1221.56  4822.0 1221.03  4828.3 1221.79  4890.5 1220.61  4976.0 1220.89
  4983.7 1220.09  4994.1 1216.93  5001.4 1216.74  5004.2 1216.24  5007.4 1216.74
  5010.6 1219.42  5015.7 1220.28  5025.2 1223.98  5035.5 1225.32  5196.8 1234.45
  5222.1 1235.60  5238.9 1237.78  5305.0 1240.40  5332.6 1243.62  5415.4 1247.51
#Mann=7,-1,0
  3957.5    0.16       0  4064.7     0.1       0  4202.3    0.16       0
  5001.4    0.07       0  5007.4    0.16       0  5196.8     0.1       0
  5332.6    0.16       0
Bank Sta=5001.4,5007.4
Exp/Cntr=0.3,0.1

Type RM Length L Ch R = 1,10675,671,671,671
BEGIN DESCRIPTION:
UNT 1013 IN LATR 21.0
END DESCRIPTION:
XS GIS Cut Line= 4
      2930084.90     10108782.45      2930657.83     10108350.15
      2931084.92     10108120.99      2931501.61     10107860.55
#Sta/Elev= 30
  3973.1 1244.74  4052.7 1239.70  4243.8 1231.78  4295.9 1230.15  4326.6 1227.48
  4380.7 1226.58  4474.9 1222.94  4624.7 1220.52  4805.1 1219.53  4925.3 1215.77
  4968.2 1216.62  4985.4 1216.16  4991.1 1215.26  4995.0 1212.39  4997.7 1211.89
  5001.0 1212.39  5007.4 1212.62  5020.7 1215.64  5095.1 1218.18  5138.9 1223.14
  5215.2 1229.00  5255.8 1234.03  5298.2 1243.08  5380.2 1249.36  5450.9 1258.00
  5489.7 1259.60  5545.3 1263.40  5560.0 1263.40  5590.7 1266.31  5666.9 1268.26
#Mann=9,-1,0
  3973.1     0.1       0  4243.8    0.16       0  4326.6     0.1       0
  4380.7    0.05       0  4968.2    0.16       0  4995.0    0.07       0
  5001.0    0.16       0  5215.2     0.1       0  5489.7    0.16       0
Bank Sta=4995,5001
Exp/Cntr=0.3,0.1

Type RM Length L Ch R = 1,10004,792,792,792
BEGIN DESCRIPTION:
UNT 1013 IN LATR 19.0
END DESCRIPTION:
XS GIS Cut Line= 3
      2930329.71     10109318.90      2931569.29     10108542.86
      2931984.74     10108449.39
#Sta/Elev= 30
  3943.6 1229.59  3964.4 1229.11  4207.7 1220.92  4265.4 1220.10  4307.9 1217.44
  4359.7 1217.46  4375.1 1215.91  4460.7 1213.35  4686.8 1212.73  4825.4 1211.18
  4921.4 1212.20  4940.9 1211.16  4977.4 1212.09  4995.7 1207.97  4998.4 1207.47
  5001.7 1207.97  5041.1 1210.26  5093.0 1210.57  5135.4 1212.66  5150.7 1214.07
  5193.2 1221.98  5279.3 1228.37  5302.8 1231.44  5333.4 1239.89  5391.2 1245.14
  5436.0 1254.44  5477.0 1257.09  5562.8 1258.61  5749.3 1257.23  5831.9 1259.45
#Mann=9,-1,0
  3943.6    0.16       0  3964.4    0.05       0  4460.7     0.1       0
  4686.8    0.05       0  4921.4    0.16       0  4995.7    0.07       0
  5001.7    0.16       0  5279.3     0.1       0  5749.3    0.16       0
Bank Sta=4995.7,5001.7
Exp/Cntr=0.3,0.1

Type RM Length L Ch R = 1,9212,941,941,941
BEGIN DESCRIPTION:
UNT 1013 IN LATR 17.0
END DESCRIPTION:
XS GIS Cut Line= 3
      2930407.81     10109454.32      2931720.33     10109485.57
      2932104.63     10109392.09
#Sta/Elev= 30
  4122.7 1224.72  4213.4 1221.20  4243.4 1219.01  4293.4 1218.31  4363.4 1214.37
  4433.4 1213.66  4483.5 1211.05  4547.9 1209.67  4632.1 1209.58  4762.8 1206.38
  4803.5 1206.73  4943.6 1203.38  4983.6 1203.57  5000.6 1201.07  5003.4 1200.57
  5006.6 1201.07  5023.6 1203.87  5263.7 1205.80  5333.7 1210.87  5435.6 1216.42
  5473.0 1220.60  5587.2 1228.14  5639.5 1236.87  5670.4 1238.16  5701.3 1241.32
  5711.5 1242.86  5722.7 1246.97  5742.4 1250.33  5816.2 1254.45  5831.1 1255.25
#Mann=9,-1,0
  4122.7    0.05       0  4547.9     0.1       0  4632.1    0.05       0
  4762.8     0.1       0  4943.6    0.16       0  5000.6    0.07       0
  5006.6    0.16       0  5473.0     0.1       0  5816.2    0.16       0
Bank Sta=5000.6,5006.6
Exp/Cntr=0.3,0.1

Type RM Length L Ch R = 1,8271,841,841,841
BEGIN DESCRIPTION:
UNT 1013 IN LATR 15.0
END DESCRIPTION:
XS GIS Cut Line= 4
      2930402.63     10110178.28      2931235.96     10110391.82
      2931829.71     10110240.78      2932449.54     10110141.81
#Sta/Elev= 30
  3823.6 1216.08  3830.0 1216.11  3872.8 1214.10  3930.8 1212.24  4087.7 1208.37
  4110.5 1207.54  4129.0 1205.29  4155.7 1204.62  4263.2 1205.81  4679.0 1194.63
  4734.9 1193.70  4851.5 1196.26  4980.4 1194.81  4993.0 1193.18  4995.7 1192.68
  4999.0 1193.18  5021.3 1195.11  5047.6 1194.49  5078.5 1195.44  5098.0 1197.13
  5223.9 1199.99  5266.8 1200.37  5406.6 1205.45  5609.2 1214.88  5639.6 1217.40
  5730.7 1221.86  5785.9 1226.01  5811.7 1227.82  5862.3 1235.52  5924.2 1239.60
#Mann=11,-1,0
  3823.6     0.1       0  3830.0    0.05       0  3872.8     0.1       0
  3930.8    0.05       0  4155.7     0.1       0  4679.0    0.16       0
  4980.4     0.1       0  4993.0    0.07       0  4999.0     0.1       0
  5223.9    0.16       0  5785.9     0.1       0
Bank Sta=4993,4999
Exp/Cntr=0.3,0.1

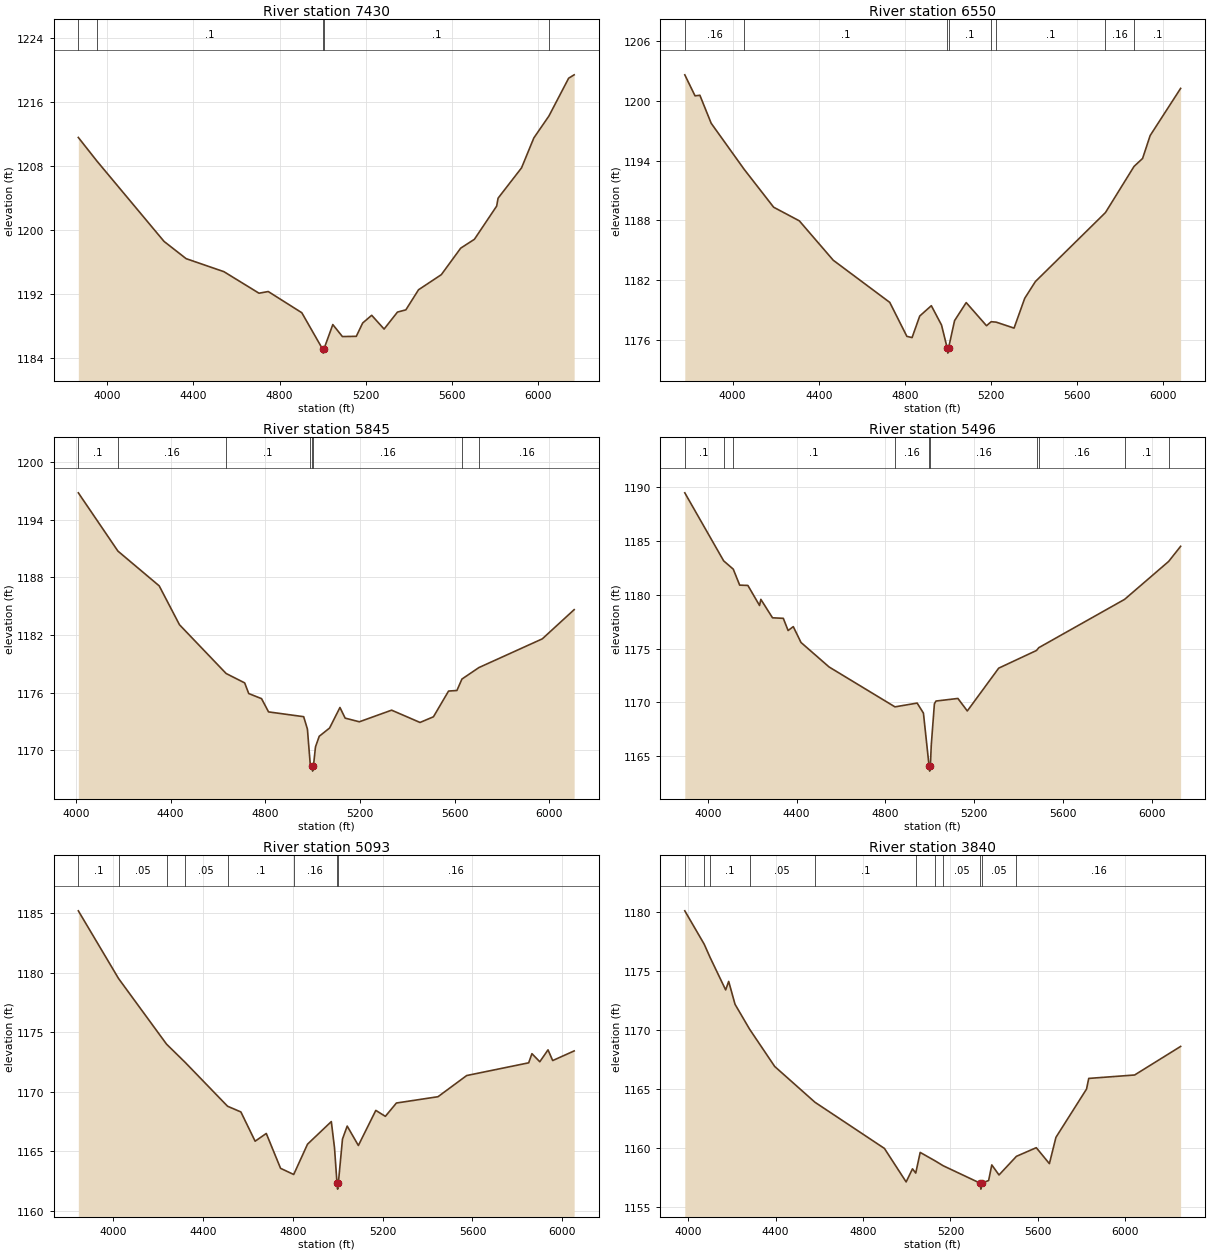
Type RM Length L Ch R = 1,7430,880,880,880
BEGIN DESCRIPTION:
UNT 1013 IN LATR 13.0
END DESCRIPTION:
XS GIS Cut Line= 4
      2930152.58     10110876.18      2930944.29     10111074.11
      2931558.87     10110943.90      2932340.14     10110589.73
#Sta/Elev= 30
  3865.8 1211.61  3951.2 1208.69  4263.6 1198.62  4366.3 1196.46  4541.9 1194.83
  4704.7 1192.14  4747.5 1192.35  4903.4 1189.70  5000.0 1185.15  5002.8 1184.65
  5006.0 1185.15  5047.3 1188.22  5091.9 1186.72  5156.4 1186.75  5186.1 1188.42
  5227.9 1189.38  5285.5 1187.66  5347.5 1189.78  5386.5 1190.06  5445.3 1192.57
  5551.2 1194.46  5641.0 1197.77  5704.8 1198.88  5808.1 1203.03  5814.7 1204.02
  5923.6 1207.81  5980.7 1211.55  6050.9 1214.30  6142.4 1219.02  6167.9 1219.44
#Mann=5,-1,0
  3865.8    0.05       0  3951.2     0.1       0  5000.0    0.07       0
  5006.0     0.1       0  6050.9    0.16       0
Bank Sta=5000,5006
Exp/Cntr=0.3,0.1

Type RM Length L Ch R = 1,6550,705,705,705
BEGIN DESCRIPTION:
UNT 1013 IN LATR 12.0
END DESCRIPTION:
XS GIS Cut Line= 4
      2930381.78     10112204.32      2931329.71     10111902.24
      2931715.12     10111745.99      2932402.33     10111178.52
#Sta/Elev= 30
  3777.9 1202.60  3825.5 1200.49  3847.9 1200.55  3900.4 1197.74  4053.5 1193.12
  4190.3 1189.32  4309.7 1187.95  4467.1 1184.00  4729.5 1179.77  4809.0 1176.36
  4833.1 1176.24  4868.6 1178.40  4922.5 1179.44  4969.8 1177.50  4996.3 1175.18
  4999.0 1174.68  5002.3 1175.18  5030.4 1177.94  5084.4 1179.75  5178.7 1177.43
  5200.3 1177.83  5223.4 1177.79  5306.6 1177.19  5356.1 1180.18  5405.6 1181.86
  5730.9 1188.78  5863.6 1193.41  5903.3 1194.21  5938.5 1196.51  6079.9 1201.24
#Mann=8,-1,0
  3777.9    0.16       0  4053.5     0.1       0  4996.3    0.07       0
  5002.3     0.1       0  5200.3    0.16       0  5223.4     0.1       0
  5730.9    0.16       0  5863.6     0.1       0
Bank Sta=4996.3,5002.3
Exp/Cntr=0.3,0.1

Type RM Length L Ch R = 1,5845,349,349,349
BEGIN DESCRIPTION:
UNT 1013 IN LATR 10.0
END DESCRIPTION:
XS GIS Cut Line= 4
      2930814.10     10112928.27      2931590.12     10112605.36
      2931767.21     10112277.24      2932376.60     10111641.80
#Sta/Elev= 30
  4010.6 1196.80  4177.8 1190.73  4352.1 1187.11  4437.7 1183.06  4634.7 1177.98
  4713.1 1177.00  4730.2 1175.89  4784.3 1175.36  4813.9 1173.98  4962.2 1173.48
  4978.0 1172.19  4989.8 1168.56  4997.3 1168.31  5000.0 1167.81  5003.3 1168.31
  5012.1 1170.34  5027.9 1171.44  5071.6 1172.30  5115.4 1174.44  5137.3 1173.33
  5197.3 1172.95  5333.5 1174.16  5453.6 1172.88  5510.2 1173.47  5574.0 1176.15
  5609.3 1176.21  5630.5 1177.40  5702.4 1178.60  5970.0 1181.59  6104.4 1184.63
#Mann=8,-1,0
  4010.6     0.1       0  4177.8    0.16       0  4634.7     0.1       0
  4989.8    0.16       0  4997.3    0.07       0  5003.3    0.16       0
  5630.5     0.1       0  5702.4    0.16       0
Bank Sta=4997.3,5003.3
Exp/Cntr=0.3,0.1

Type RM Length L Ch R = 1,5496,403,403,403
BEGIN DESCRIPTION:
UNT 1013 IN LATR 9.0
END DESCRIPTION:
XS GIS Cut Line= 4
      2931048.45     10113193.91      2931860.96     10112709.53
      2932209.92     10112344.94      2932647.42     10111693.90
#Sta/Elev= 30
  3896.0 1189.44  4071.2 1183.13  4114.5 1182.36  4143.4 1180.88  4180.4 1180.85
  4233.0 1178.99  4238.8 1179.56  4291.4 1177.85  4340.0 1177.80  4361.7 1176.67
  4385.0 1177.03  4419.9 1175.56  4546.4 1173.29  4843.3 1169.59  4943.4 1169.94
  4971.7 1169.01  4997.0 1164.13  4999.7 1163.63  5003.0 1164.13  5006.9 1166.01
  5021.1 1169.87  5028.3 1170.13  5127.0 1170.37  5169.5 1169.21  5311.0 1173.18
  5481.4 1174.82  5491.8 1175.08  5878.5 1179.56  6077.2 1183.08  6131.0 1184.48
#Mann=10,-1,0
  3896.0     0.1       0  4071.2    0.05       0  4114.5     0.1       0
  4843.3    0.16       0  4997.0    0.07       0  5003.0    0.16       0
  5481.4     0.1       0  5491.8    0.16       0  5878.5     0.1       0
  6077.2    0.16       0
Bank Sta=4997,5003
Exp/Cntr=0.3,0.1

Type RM Length L Ch R = 1,5093,1253,1253,1253
BEGIN DESCRIPTION:
UNT 1013 IN LATR 8.0
END DESCRIPTION:
XS GIS Cut Line= 3
      2931418.28     10113657.41      2932465.12     10112673.07
      2932954.12     10112074.83
#Sta/Elev= 30
  3843.7 1185.21  4022.9 1179.52  4236.8 1174.00  4318.6 1172.49  4508.7 1168.78
  4568.1 1168.30  4631.6 1165.84  4681.3 1166.49  4744.9 1163.56  4803.5 1163.04
  4865.1 1165.59  4971.1 1167.49  4985.3 1165.29  4996.4 1162.31  4999.2 1161.81
  5002.4 1162.31  5020.9 1166.02  5041.9 1167.11  5091.7 1165.48  5169.4 1168.43
  5211.9 1167.93  5261.2 1169.05  5446.5 1169.58  5574.3 1171.36  5850.7 1172.43
  5865.1 1173.20  5900.2 1172.52  5936.8 1173.52  5957.7 1172.62  6053.3 1173.43
#Mann=8,-1,0
  3843.7     0.1       0  4022.9    0.05       0  4236.8     0.1       0
  4318.6    0.05       0  4508.7     0.1       0  4803.5    0.16       0
  4996.4    0.07       0  5002.4    0.16       0
Bank Sta=4996.4,5002.4
Exp/Cntr=0.3,0.1

Type RM Length L Ch R = 1,3840,951,951,951
BEGIN DESCRIPTION:
UNT 1013 IN LATR 7.0
END DESCRIPTION:
XS GIS Cut Line= 4
      2931742.77     10114020.99      2932497.93     10113847.39
      2932905.92     10113322.22      2932914.60     10112493.25
#Sta/Elev= 30
  3984.4 1180.11  4073.3 1177.28  4100.4 1176.15  4171.4 1173.41  4185.2 1174.13
  4214.3 1172.19  4281.0 1170.08  4395.9 1166.92  4580.1 1163.89  4897.8 1159.98
  4997.3 1157.14  5026.3 1158.25  5041.2 1157.89  5061.6 1159.64  5131.3 1158.91
  5166.9 1158.51  5336.4 1157.03  5339.2 1156.53  5342.4 1157.03  5374.7 1157.26
  5389.2 1158.58  5422.3 1157.73  5502.0 1159.31  5592.8 1160.04  5652.8 1158.69
  5682.8 1160.92  5822.8 1165.01  5832.8 1165.91  6042.8 1166.20  6253.3 1168.62
#Mann=11,-1,0
  3984.4     0.1       0  4073.3    0.05       0  4100.4     0.1       0
  4281.0    0.05       0  4580.1     0.1       0  5041.2    0.05       0
  5131.3     0.1       0  5166.9    0.05       0  5336.4    0.07       0
  5342.4    0.05       0  5502.0    0.16       0
Bank Sta=5336.4,5342.4
Exp/Cntr=0.3,0.1

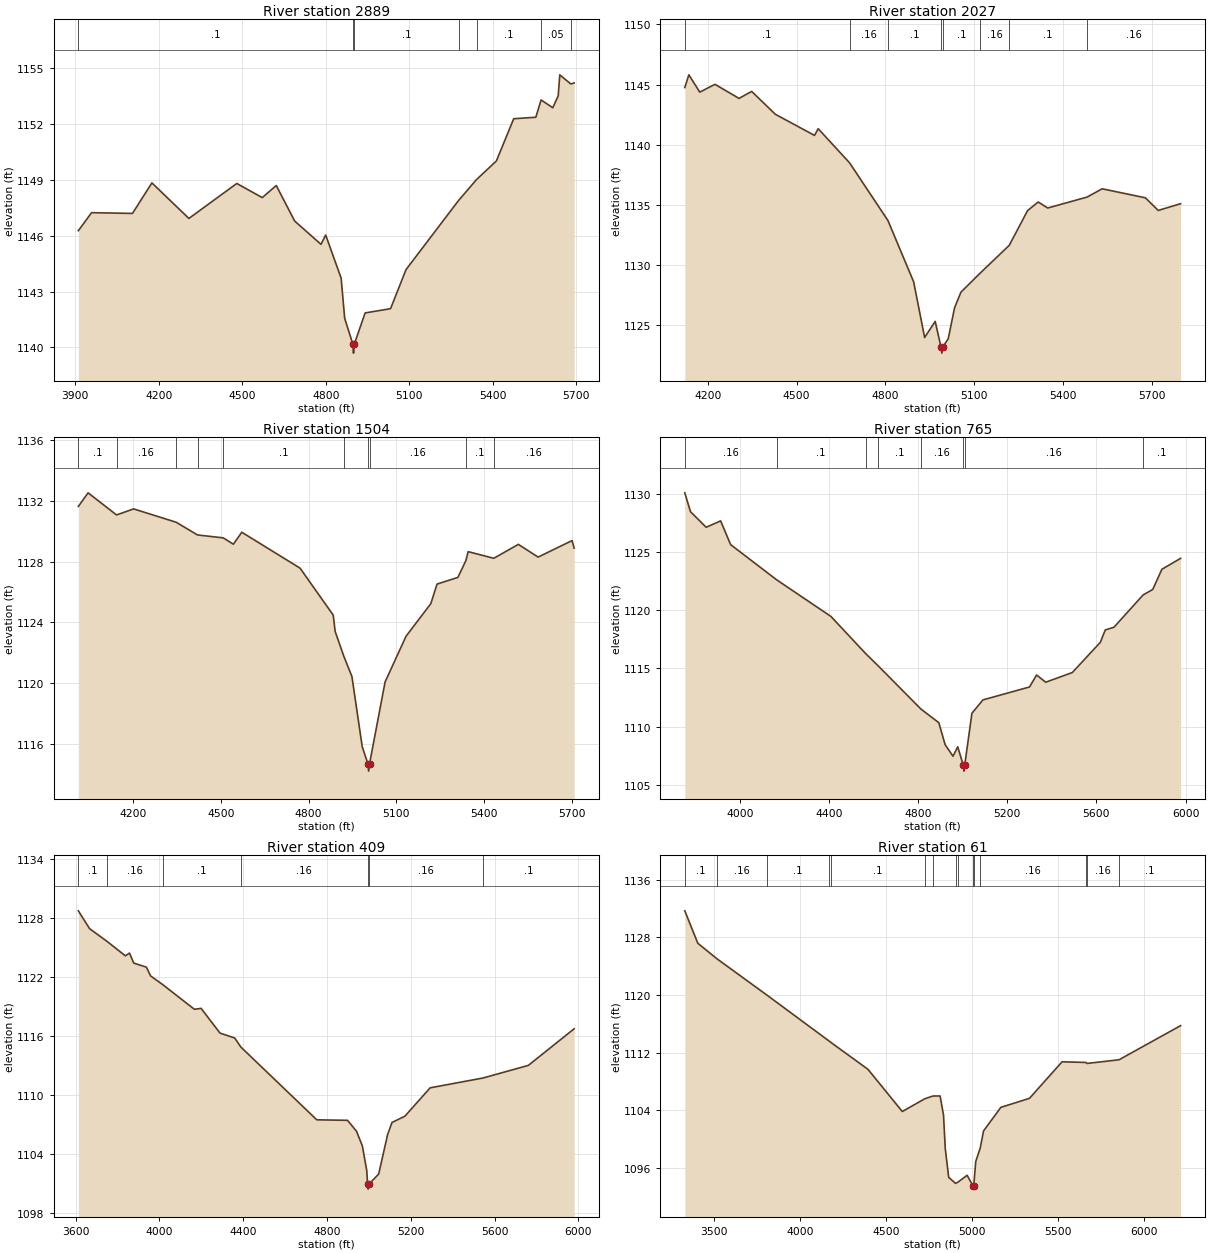
Type RM Length L Ch R = 1,2889,862,862,862
BEGIN DESCRIPTION:
UNT 1013 IN LATR 5.0
END DESCRIPTION:
XS GIS Cut Line= 2
      2933126.57     10114641.86      2933741.16     10112969.95
#Sta/Elev= 30
  3911.2 1146.27  3958.7 1147.24  4105.7 1147.20  4175.6 1148.84  4308.4 1146.93
  4480.5 1148.81  4572.0 1148.05  4622.3 1148.70  4688.5 1146.79  4782.9 1145.54
  4799.8 1146.04  4855.4 1143.72  4868.1 1141.56  4897.1 1140.19  4899.8 1139.69
  4903.1 1140.19  4941.5 1141.85  5032.9 1142.08  5088.5 1144.18  5277.0 1147.89
  5341.7 1149.02  5413.1 1150.02  5475.4 1152.29  5554.8 1152.37  5573.7 1153.30
  5615.7 1152.88  5635.2 1153.52  5640.9 1154.65  5680.3 1154.16  5692.5 1154.21
#Mann=7,-1,0
  3911.2     0.1       0  4897.1    0.07       0  4903.1     0.1       0
  5277.0    0.05       0  5341.7     0.1       0  5573.7    0.05       0
  5680.3     0.1       0
Bank Sta=4897.1,4903.1
Exp/Cntr=0.3,0.1

Type RM Length L Ch R = 1,2027,523,523,523
BEGIN DESCRIPTION:
UNT 1013 IN LATR 4.0
END DESCRIPTION:
XS GIS Cut Line= 3
      2933230.73     10114725.17      2934230.75     10114131.40
      2934480.76     10113683.46
#Sta/Elev= 30
  4122.0 1144.75  4135.7 1145.81  4172.7 1144.37  4224.0 1145.02  4305.3 1143.85
  4348.1 1144.43  4428.0 1142.53  4560.5 1140.77  4572.9 1141.33  4679.0 1138.49
  4808.7 1133.69  4895.6 1128.59  4932.7 1123.96  4968.4 1125.30  4988.1 1123.16
  4990.9 1122.66  4994.1 1123.16  5012.5 1123.86  5034.0 1126.44  5055.4 1127.73
  5118.9 1129.28  5218.8 1131.63  5280.8 1134.52  5316.8 1135.23  5348.7 1134.73
  5481.7 1135.64  5532.7 1136.33  5678.9 1135.58  5722.4 1134.53  5798.0 1135.09
#Mann=8,-1,0
  4122.0     0.1       0  4679.0    0.16       0  4808.7     0.1       0
  4988.1    0.07       0  4994.1     0.1       0  5118.9    0.16       0
  5218.8     0.1       0  5481.7    0.16       0
Bank Sta=4988.1,4994.1
Exp/Cntr=0.3,0.1

Type RM Length L Ch R = 1,1504,739,739,739
BEGIN DESCRIPTION:
UNT 1013 IN LATR 3.0
END DESCRIPTION:
XS GIS Cut Line= 3
      2933657.83     10115459.53      2934517.21     10114417.86
      2934636.99     10114094.97
#Sta/Elev= 30
  4012.7 1131.64  4046.1 1132.54  4143.4 1131.08  4201.7 1131.48  4347.0 1130.60
  4420.1 1129.76  4507.9 1129.57  4542.7 1129.15  4571.4 1129.94  4770.7 1127.57
  4884.1 1124.47  4890.5 1123.40  4919.8 1121.78  4947.9 1120.42  4983.1 1115.79
  5002.3 1114.68  5005.0 1114.18  5008.3 1114.68  5061.2 1120.06  5132.9 1123.08
  5217.6 1125.23  5238.8 1126.52  5310.1 1126.96  5337.4 1128.07  5345.3 1128.66
  5432.7 1128.22  5516.8 1129.14  5584.3 1128.30  5700.4 1129.39  5707.5 1128.89
#Mann=10,-1,0
  4012.7     0.1       0  4143.4    0.16       0  4347.0     0.1       0
  4420.1    0.16       0  4507.9     0.1       0  4919.8    0.16       0
  5002.3    0.07       0  5008.3    0.16       0  5337.4     0.1       0
  5432.7    0.16       0
Bank Sta=5002.3,5008.3
Exp/Cntr=0.3,0.1

Type RM Length L Ch R = 1,765,356,356,356
BEGIN DESCRIPTION:
UNT 1013 IN LATR 2.0
END DESCRIPTION:
XS GIS Cut Line= 4
      2933661.99     10115687.29      2934623.98     10115387.48
      2934920.67     10115097.01      2934751.41     10114311.47
#Sta/Elev= 30
  3751.7 1130.09  3777.3 1128.47  3847.6 1127.13  3912.6 1127.68  3957.5 1125.64
  4163.9 1122.62  4407.9 1119.47  4563.8 1116.28  4619.8 1115.23  4812.2 1111.51
  4892.4 1110.34  4920.7 1108.45  4956.1 1107.46  4977.2 1108.27  5002.5 1106.68
  5005.3 1106.18  5008.5 1106.68  5041.0 1111.15  5090.4 1112.30  5299.6 1113.41
  5331.3 1114.44  5372.2 1113.82  5491.7 1114.65  5617.8 1117.25  5639.7 1118.31
  5678.7 1118.54  5809.3 1121.31  5853.0 1121.79  5893.9 1123.52  5978.1 1124.46
#Mann=8,-1,0
  3751.7    0.16       0  4163.9     0.1       0  4563.8    0.16       0
  4619.8     0.1       0  4812.2    0.16       0  5002.5    0.07       0
  5008.5    0.16       0  5809.3     0.1       0
Bank Sta=5002.5,5008.5
Exp/Cntr=0.3,0.1

Type RM Length L Ch R = 1,409,348,348,348
BEGIN DESCRIPTION:
Mapping XS 7fb7f6b6
END DESCRIPTION:
XS GIS Cut Line= 4
      2933684.99     10115762.96      2934844.98     10115649.56
      2935102.49     10115420.40      2934934.75     10114579.30
#Sta/Elev= 30
  3612.4 1128.73  3666.1 1126.92  3751.1 1125.60  3836.9 1124.16  3856.7 1124.44
  3877.1 1123.42  3937.4 1123.01  3957.5 1122.12  4017.6 1121.20  4166.6 1118.73
  4198.7 1118.82  4289.1 1116.31  4359.4 1115.81  4388.2 1114.90  4751.3 1107.50
  4897.9 1107.45  4940.6 1106.35  4969.0 1104.84  4989.9 1102.34  4993.8 1100.96
  4996.5 1100.46  4999.8 1100.96  5046.8 1101.99  5089.4 1106.00  5110.3 1107.23
  5172.1 1107.87  5292.6 1110.75  5545.6 1111.75  5761.6 1113.03  5980.3 1116.75
#Mann=7,-1,0
  3612.4     0.1       0  3751.1    0.16       0  4017.6     0.1       0
  4388.2    0.16       0  4993.8    0.07       0  4999.8    0.16       0
  5545.6     0.1       0
Bank Sta=4993.8,4999.8
Exp/Cntr=0.3,0.1

Type RM Length L Ch R = 1,61,0,0,0
BEGIN DESCRIPTION:
UNT 1013 IN LATR 1.0
END DESCRIPTION:
XS GIS Cut Line= 4
      2933632.63     10115846.63      2935193.32     10115823.72
      2935299.28     10115680.54      2934981.52     10114578.42
#Sta/Elev= 30
  3329.3 1131.67  3405.1 1127.17  3515.7 1125.03  3808.9 1119.95  4165.9 1113.66
  4180.1 1113.40  4395.3 1109.68  4595.3 1103.82  4726.3 1105.59  4773.3 1105.97
  4815.3 1105.98  4835.3 1103.32  4845.3 1098.69  4865.3 1094.69  4905.0 1093.85
  4919.3 1094.02  4972.7 1094.97  5005.2 1093.55  5008.0 1093.05  5011.2 1093.55
  5022.8 1096.89  5048.7 1098.73  5068.3 1101.13  5169.0 1104.40  5335.6 1105.65
  5525.3 1110.72  5663.0 1110.63  5670.5 1110.49  5856.8 1111.00  6215.3 1115.74
#Mann=15,-1,0
  3329.3     0.1       0  3515.7    0.16       0  3808.9     0.1       0
  4165.9    0.16       0  4180.1     0.1       0  4726.3    0.16       0
  4773.3     0.1       0  4905.0    0.05       0  4919.3     0.1       0
  5005.2    0.07       0  5011.2     0.1       0  5048.7    0.16       0
  5663.0     0.1       0  5670.5    0.16       0  5856.8     0.1       0
Bank Sta=5005.2,5011.2
Exp/Cntr=0.3,0.1

Chan Stop Cuts=-1