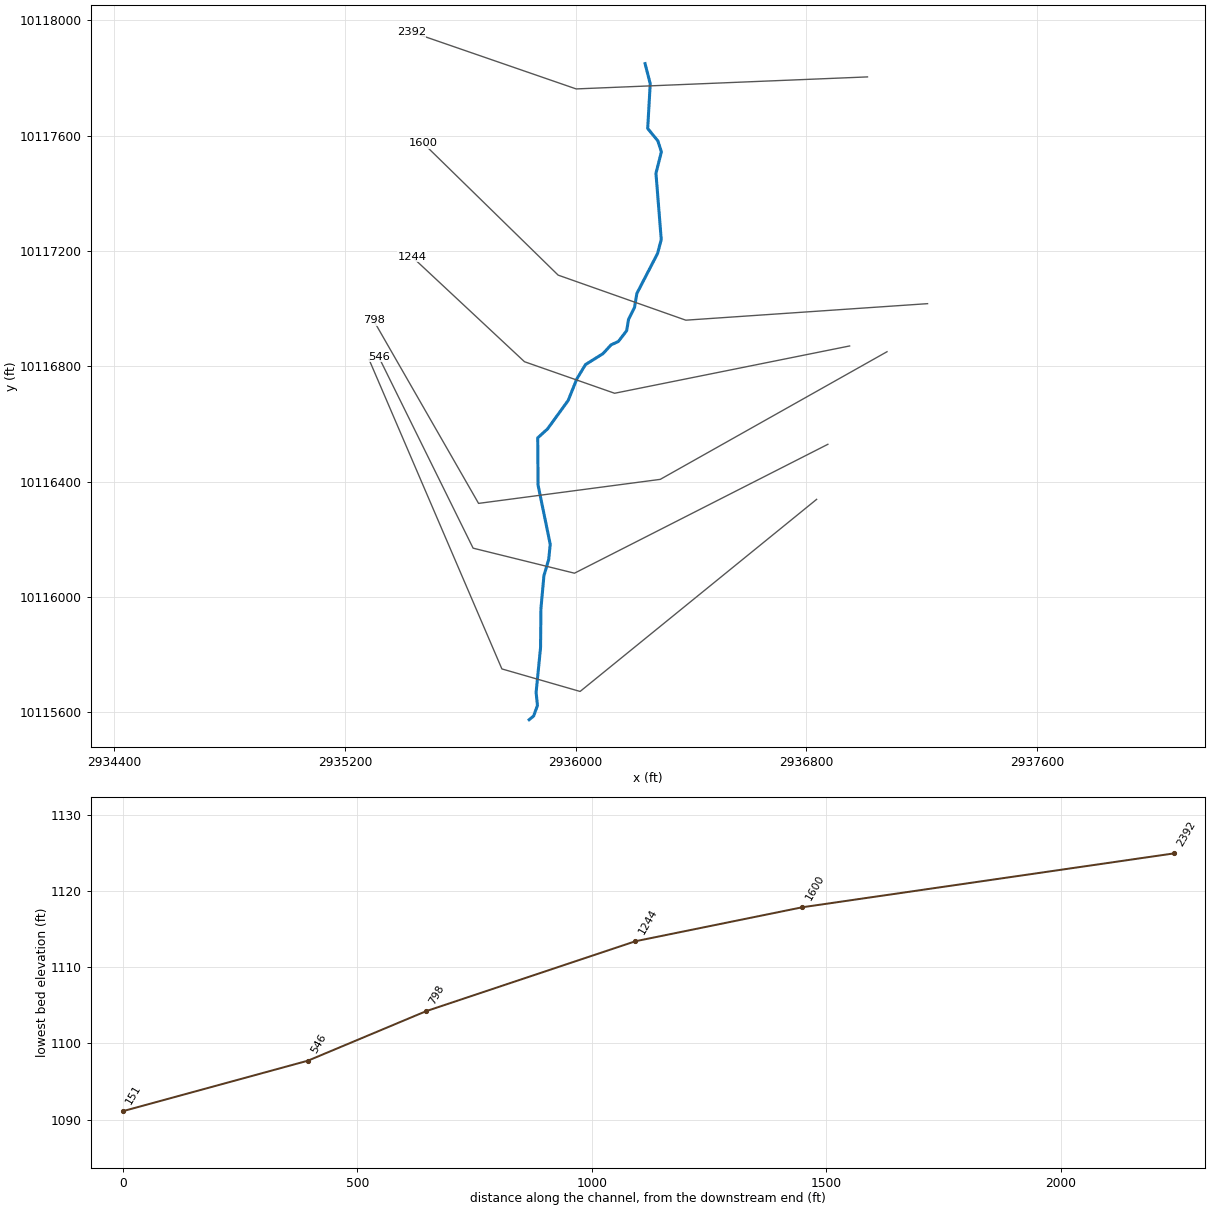
--- UNT 0014 IN LATR.prj (project) ---

Proj Title=UNT 1014 IN LATR Base Level Engineering
Current Plan=p01
Default Exp/Contr=0.3,0.1
English Units
Geom File=g01
Flow File=f01
Plan File=p01
BEGIN DESCRIPTION:
UNT 1014 IN LATR
END DESCRIPTION:

--- UNT 0014 IN LATR.p01 (plan) ---

Plan Title=Multiple Run
Short Identifier=Multiple
Geom File=g01
Flow File=f01
Subcritical Flow
K Sum by GR= 0
Std Step Tol= 0.01
Critical Tol= 0.01
Num of Std Step Trials= 20
Max Error Tol= 0.3
Flow Tol Ratio= 0.001
Split Flow NTrial= 30
Split Flow Tol= 0.02
Split Flow Ratio= 0.02
Log Output Level= 0
Friction Slope Method= 1
Unsteady Friction Slope Method= 2
Unsteady Bridges Friction Slope Method= 1
Parabolic Critical Depth
Global Vel Dist=  1 , 1 , 1
Global Log Level= 0
CheckData=True
Encroach Param= -1, 0, 0, 0
BEGIN DESCRIPTION:
Multiple Run
END DESCRIPTION:

--- UNT 0014 IN LATR.f01 (steady flow) ---

Flow Title=Multiple
Number of Profiles=7
Profile Names=10-year,25-year,50-year,1pct_min,100-year,1pct_plu,500-year
River Rch & RM= UNT 1014 IN LATR,Reach-1,2392
     644     912    1139    1042    1410    1906    2165
Boundary for River Rch & Prof#=UNT 1014 IN LATR,Reach-1,1
Up Type=0
Dn Type=3
Dn Slope=0.005
Boundary for River Rch & Prof#=UNT 1014 IN LATR,Reach-1,2
Up Type=0
Dn Type=3
Dn Slope=0.005
Boundary for River Rch & Prof#=UNT 1014 IN LATR,Reach-1,3
Up Type=0
Dn Type=3
Dn Slope=0.005
Boundary for River Rch & Prof#=UNT 1014 IN LATR,Reach-1,4
Up Type=0
Dn Type=3
Dn Slope=0.005
Boundary for River Rch & Prof#=UNT 1014 IN LATR,Reach-1,5
Up Type=0
Dn Type=3
Dn Slope=0.005
Boundary for River Rch & Prof#=UNT 1014 IN LATR,Reach-1,6
Up Type=0
Dn Type=3
Dn Slope=0.005
Boundary for River Rch & Prof#=UNT 1014 IN LATR,Reach-1,7
Up Type=0
Dn Type=3
Dn Slope=0.005

--- UNT 0014 IN LATR.g01 (geometry) ---

Geom Title=Existing Conditions

River Reach=UNT 1014 IN LATR,Reach-1
Reach XY= 30
      2936240.49     10117849.34      2936258.43     10117779.84
      2936249.66     10117624.26      2936284.83     10117581.46
      2936297.16     10117543.61      2936278.31     10117468.81
      2936296.67     10117238.99      2936283.92     10117190.95
      2936212.09     10117052.20      2936204.06     10117004.20
      2936183.18     10116962.26      2936176.90     10116923.46
      2936147.96     10116885.69      2936122.43     10116873.79
      2936094.70     10116843.54      2936033.89     10116805.50
      2936004.05     10116756.22      2935973.76     10116680.97
      2935902.07     10116582.17      2935868.26     10116551.39
      2935869.39     10116387.50      2935911.56     10116182.46
      2935906.32     10116129.62      2935889.69     10116073.23
      2935879.37     10115959.18      2935878.04     10115824.02
      2935862.62     10115668.64      2935867.28     10115623.15
      2935854.07     10115586.74      2935838.47     10115573.73

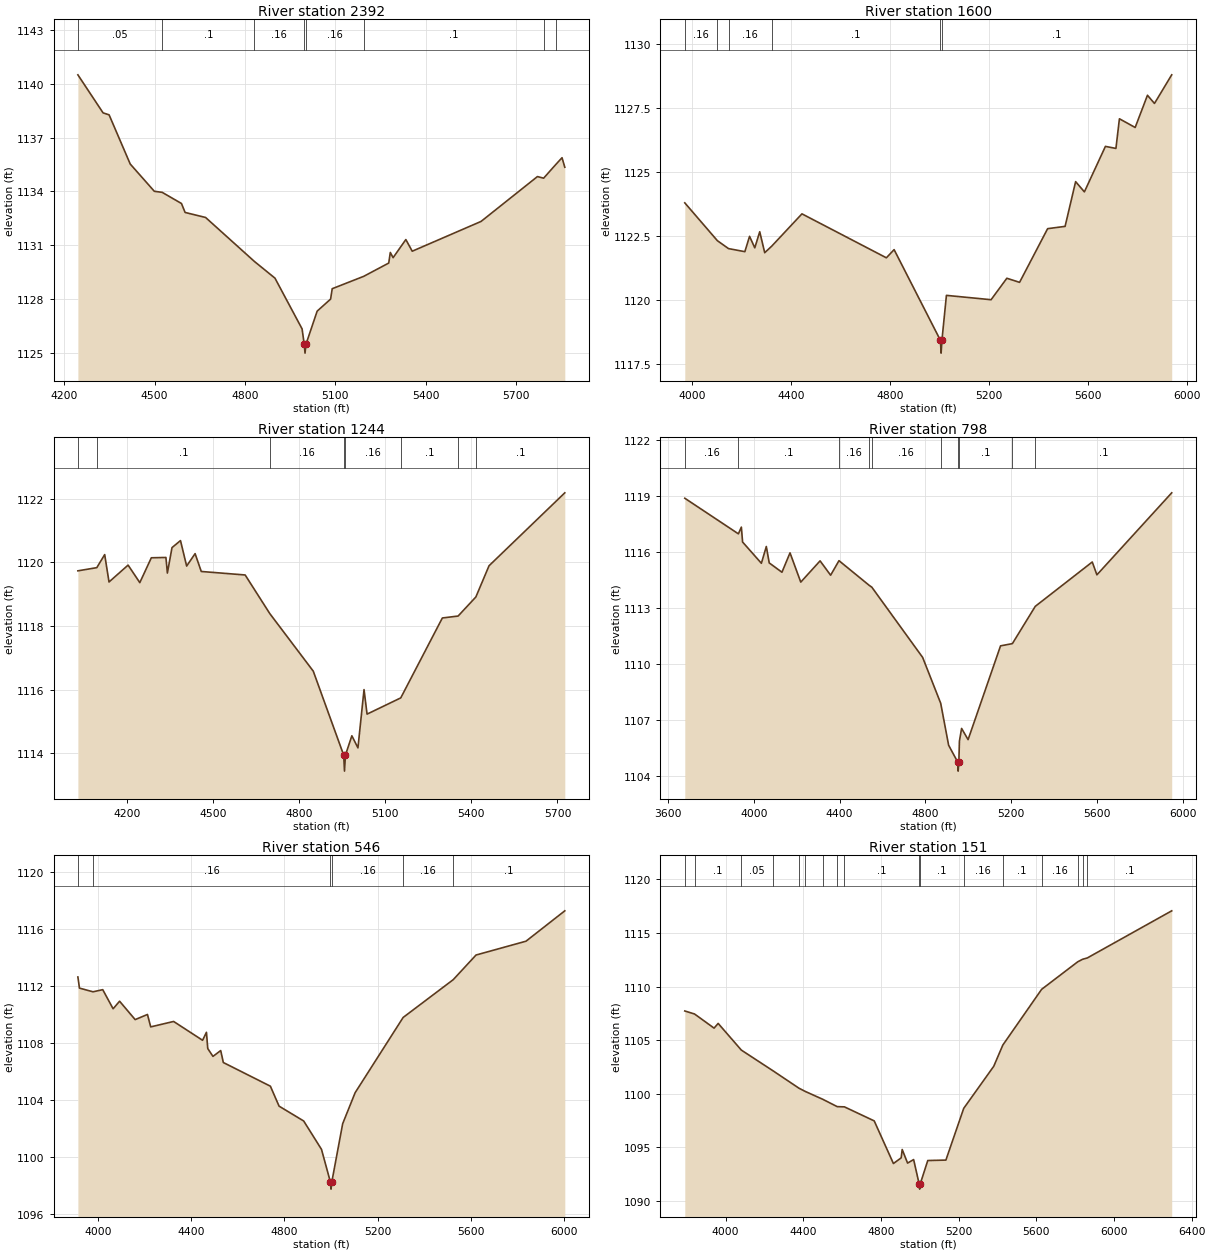
Type RM Length L Ch R = 1,2392,792,792,792
BEGIN DESCRIPTION:
UNT 1014 IN LATR 4.0
END DESCRIPTION:
XS GIS Cut Line= 3
      2937011.99     10117803.28      2936001.58     10117761.61
      2935429.80     10117959.13
#Sta/Elev= 30
  4245.7 1140.50  4329.3 1138.38  4349.3 1138.27  4419.4 1135.53  4499.4 1134.01
  4525.5 1133.95  4589.5 1133.33  4601.6 1132.83  4669.6 1132.55  4831.6 1130.10
  4899.8 1129.17  4989.9 1126.34  4996.9 1125.49  4999.6 1124.99  5002.9 1125.49
  5039.9 1127.33  5084.5 1128.00  5089.9 1128.58  5194.5 1129.27  5277.5 1130.01
  5282.7 1130.60  5292.0 1130.31  5334.3 1131.32  5355.5 1130.67  5584.0 1132.33
  5771.1 1134.83  5791.6 1134.74  5832.4 1135.51  5852.7 1135.88  5861.9 1135.35
#Mann=8,-1,0
  4245.7    0.05       0  4525.5     0.1       0  4831.6    0.16       0
  4996.9    0.07       0  5002.9    0.16       0  5194.5     0.1       0
  5791.6    0.16       0  5832.4     0.1       0
Bank Sta=4996.9,5002.9
Exp/Cntr=0.3,0.1

Type RM Length L Ch R = 1,1600,356,356,356
BEGIN DESCRIPTION:
UNT 1014 IN LATR 3.0
END DESCRIPTION:
XS GIS Cut Line= 4
      2937220.28     10117016.82      2936381.79     10116959.53
      2935939.08     10117115.78      2935470.34     10117574.10
#Sta/Elev= 30
  3971.9 1123.79  4103.4 1122.31  4148.4 1122.00  4214.3 1121.88  4233.3 1122.48
  4254.4 1122.03  4274.4 1122.66  4294.5 1121.84  4323.2 1122.10  4444.8 1123.36
  4785.6 1121.64  4816.8 1121.96  5003.8 1118.41  5006.5 1117.91  5009.8 1118.41
  5028.0 1120.17  5208.2 1120.00  5271.9 1120.84  5323.3 1120.68  5436.5 1122.78
  5507.0 1122.87  5549.5 1124.62  5584.9 1124.22  5669.8 1126.00  5712.2 1125.92
  5726.3 1127.08  5789.9 1126.74  5839.5 1128.00  5867.8 1127.68  5937.4 1128.80
#Mann=6,-1,0
  3971.9    0.16       0  4103.4     0.1       0  4148.4    0.16       0
  4323.2     0.1       0  5003.8    0.07       0  5009.8     0.1       0
Bank Sta=5003.8,5009.8
Exp/Cntr=0.3,0.1

Type RM Length L Ch R = 1,1244,446,446,446
BEGIN DESCRIPTION:
Mapping XS a68b667c
END DESCRIPTION:
XS GIS Cut Line= 4
      2936949.99     10116870.12      2936134.84     10116706.05
      2935822.34     10116815.43      2935431.73     10117180.01
#Sta/Elev= 30
  4028.7 1119.73  4094.6 1119.83  4122.1 1120.24  4137.2 1119.38  4203.7 1119.91
  4244.5 1119.36  4284.7 1120.14  4335.5 1120.15  4340.6 1119.66  4356.7 1120.46
  4386.3 1120.68  4407.7 1119.88  4437.2 1120.27  4458.7 1119.71  4611.7 1119.60
  4697.3 1118.39  4849.0 1116.58  4955.1 1113.94  4957.8 1113.44  4961.1 1113.94
  4983.5 1114.55  5004.7 1114.17  5025.9 1116.00  5036.5 1115.23  5153.9 1115.74
  5298.9 1118.25  5353.8 1118.31  5415.7 1118.91  5461.6 1119.89  5725.6 1122.18
#Mann=8,-1,0
  4028.7    0.16       0  4094.6     0.1       0  4697.3    0.16       0
  4955.1    0.07       0  4961.1    0.16       0  5153.9     0.1       0
  5353.8    0.16       0  5415.7     0.1       0
Bank Sta=4955.1,4961.1
Exp/Cntr=0.3,0.1

Type RM Length L Ch R = 1,798,252,252,252
BEGIN DESCRIPTION:
UNT 1014 IN LATR 2.0
END DESCRIPTION:
XS GIS Cut Line= 4
      2937079.68     10116850.14      2936293.25     10116407.44
      2935663.04     10116324.11      2935298.68     10116959.15
#Sta/Elev= 30
  3678.6 1118.89  3928.5 1116.98  3942.3 1117.34  3948.1 1116.54  4035.7 1115.40
  4058.7 1116.30  4072.3 1115.42  4131.6 1114.92  4169.2 1115.96  4219.3 1114.39
  4309.4 1115.53  4358.5 1114.76  4397.5 1115.54  4539.1 1114.21  4550.5 1114.12
  4787.6 1110.35  4871.8 1107.89  4908.7 1105.64  4950.4 1104.75  4953.1 1104.25
  4956.4 1104.75  4959.1 1105.86  4969.2 1106.54  4999.5 1105.94  5150.8 1110.97
  5206.0 1111.09  5312.7 1113.09  5578.5 1115.47  5600.1 1114.78  5948.9 1119.18
#Mann=10,-1,0
  3678.6    0.16       0  3928.5     0.1       0  4397.5    0.16       0
  4539.1     0.1       0  4550.5    0.16       0  4871.8     0.1       0
  4950.4    0.07       0  4956.4     0.1       0  5206.0    0.16       0
  5312.7     0.1       0
Bank Sta=4950.4,4956.4
Exp/Cntr=0.3,0.1

Type RM Length L Ch R = 1,546,395,395,395
BEGIN DESCRIPTION:
Mapping XS 09a289cf
END DESCRIPTION:
XS GIS Cut Line= 4
      2936874.54     10116529.04      2935995.68     10116082.01
      2935644.12     10116168.82      2935316.41     10116832.92
#Sta/Elev= 30
  3914.7 1112.62  3921.5 1111.84  3979.5 1111.58  4021.3 1111.73  4065.8 1110.39
  4093.6 1110.92  4160.4 1109.63  4213.2 1109.99  4227.1 1109.12  4325.4 1109.50
  4449.6 1108.18  4466.2 1108.74  4471.8 1107.60  4494.1 1107.05  4527.4 1107.46
  4538.6 1106.62  4740.5 1104.96  4777.7 1103.56  4883.3 1102.52  4959.7 1100.53
  4997.9 1098.24  5000.6 1097.74  5003.9 1098.24  5050.6 1102.33  5103.9 1104.50
  5309.9 1109.78  5524.7 1112.43  5622.7 1114.16  5837.0 1115.13  6003.4 1117.26
#Mann=6,-1,0
  3914.7     0.1       0  3979.5    0.16       0  4997.9    0.07       0
  5003.9    0.16       0  5309.9    0.16       0  5524.7     0.1       0
Bank Sta=4997.9,5003.9
Exp/Cntr=0.3,0.1

Type RM Length L Ch R = 1,151,0,0,0
BEGIN DESCRIPTION:
UNT 1014 IN LATR 1.0
END DESCRIPTION:
XS GIS Cut Line= 4
      2936835.53     10116338.09      2936015.21     10115671.85
      2935743.94     10115749.98      2935283.15     10116823.37
#Sta/Elev= 30
  3790.1 1107.72  3840.2 1107.44  3940.9 1106.12  3961.9 1106.56  4081.2 1104.07
  4245.7 1102.12  4377.2 1100.52  4410.3 1100.21  4500.1 1099.48  4574.9 1098.79
  4612.1 1098.77  4765.4 1097.46  4864.3 1093.48  4904.3 1094.01  4909.5 1094.79
  4937.2 1093.52  4968.4 1093.85  4996.6 1091.59  4999.3 1091.09  5002.6 1091.59
  5041.2 1093.76  5134.5 1093.80  5226.3 1098.63  5381.0 1102.56  5427.7 1104.54
  5627.4 1109.74  5813.3 1112.31  5838.6 1112.55  5862.6 1112.67  6297.3 1117.07
#Mann=17,-1,0
  3790.1    0.16       0  3840.2     0.1       0  4081.2    0.05       0
  4245.7    0.16       0  4377.2    0.05       0  4410.3    0.16       0
  4500.1     0.1       0  4574.9    0.16       0  4612.1     0.1       0
  4996.6    0.07       0  5002.6     0.1       0  5226.3    0.16       0
  5427.7     0.1       0  5627.4    0.16       0  5813.3     0.1       0
  5838.6    0.16       0  5862.6     0.1       0
Bank Sta=4996.6,5002.6
Exp/Cntr=0.3,0.1

Chan Stop Cuts=-1