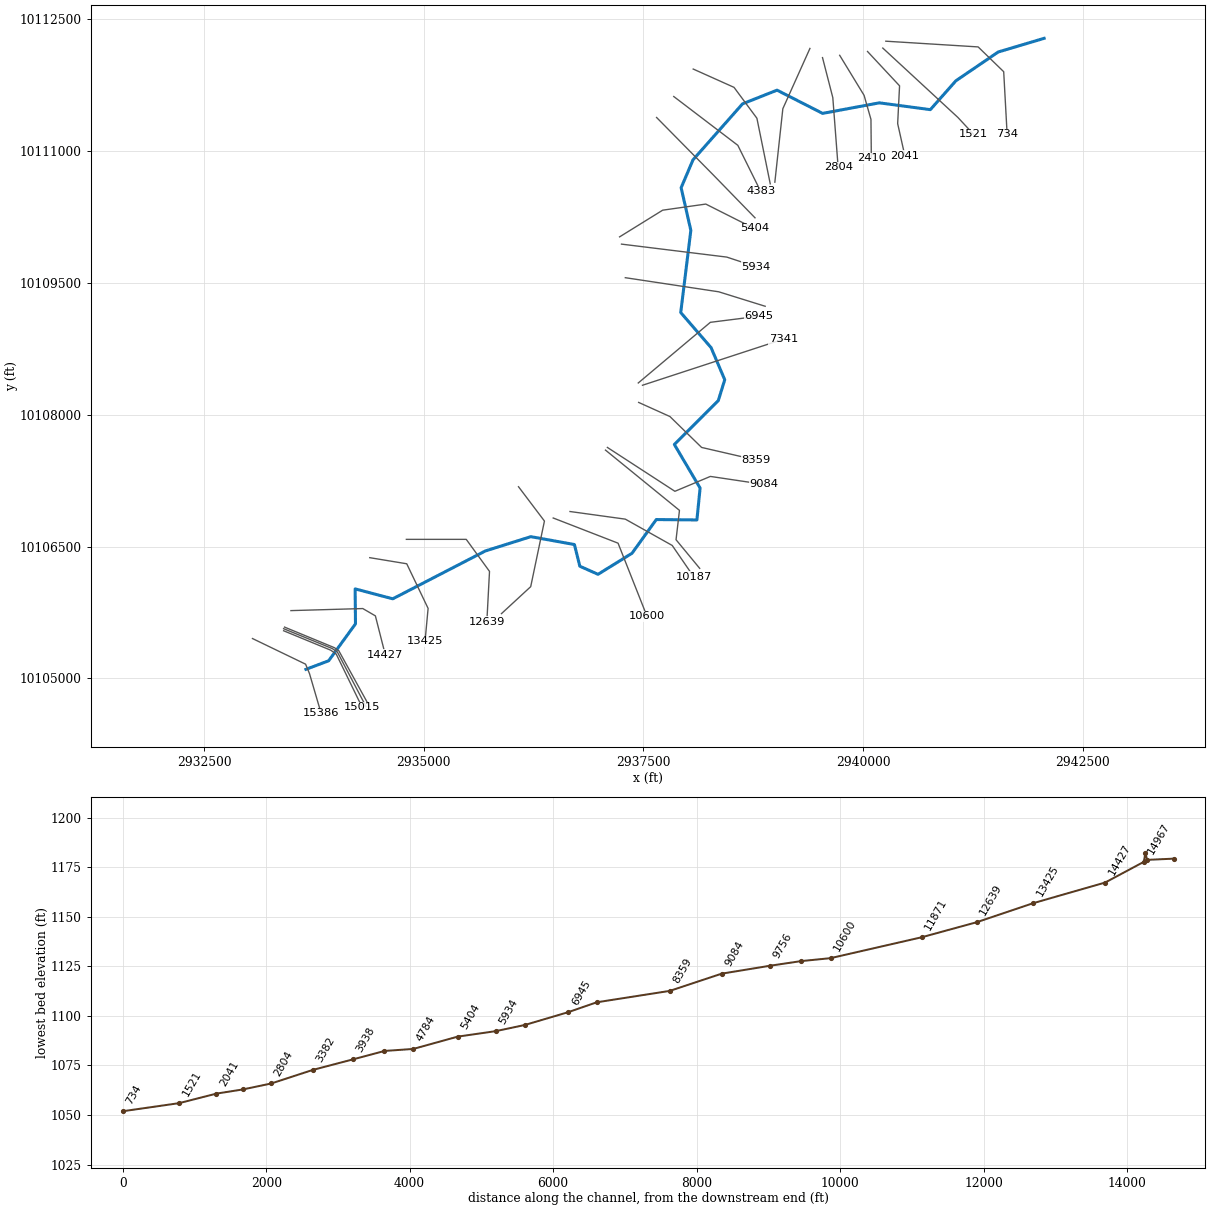
--- UNT 0015 IN LATR.prj (project) ---

Proj Title=UNT 1015 IN LATR Base Level Engineering
Current Plan=p01
Default Exp/Contr=0.3,0.1
English Units
Geom File=g01
Flow File=f01
Plan File=p01
BEGIN DESCRIPTION:
UNT 1015 IN LATR
END DESCRIPTION:

--- UNT 0015 IN LATR.p01 (plan) ---

Plan Title=Multiple Run
Short Identifier=Multiple
Geom File=g01
Flow File=f01
Subcritical Flow
K Sum by GR= 0
Std Step Tol= 0.01
Critical Tol= 0.01
Num of Std Step Trials= 20
Max Error Tol= 0.3
Flow Tol Ratio= 0.001
Split Flow NTrial= 30
Split Flow Tol= 0.02
Split Flow Ratio= 0.02
Log Output Level= 0
Friction Slope Method= 1
Unsteady Friction Slope Method= 2
Unsteady Bridges Friction Slope Method= 1
Parabolic Critical Depth
Global Vel Dist=  1 , 1 , 1
Global Log Level= 0
CheckData=True
Encroach Param= -1, 0, 0, 0
BEGIN DESCRIPTION:
Multiple Run
END DESCRIPTION:

--- UNT 0015 IN LATR.f01 (steady flow) ---

Flow Title=Multiple
Number of Profiles=7
Profile Names=10-year,25-year,50-year,1pct_min,100-year,1pct_plu,500-year
River Rch & RM= UNT 1015 IN LATR,Reach-1,15386
     801    1154    1459    1352    1828    2473    2880
River Rch & RM= UNT 1015 IN LATR,Reach-1,12639
    1358    2008    2584    2429    3285    4443    5335
River Rch & RM= UNT 1015 IN LATR,Reach-1,7341
    1686    2513    3250    3067    4148    5610    6793
Boundary for River Rch & Prof#=UNT 1015 IN LATR,Reach-1,1
Up Type=0
Dn Type=3
Dn Slope=0.005
Boundary for River Rch & Prof#=UNT 1015 IN LATR,Reach-1,2
Up Type=0
Dn Type=3
Dn Slope=0.005
Boundary for River Rch & Prof#=UNT 1015 IN LATR,Reach-1,3
Up Type=0
Dn Type=3
Dn Slope=0.005
Boundary for River Rch & Prof#=UNT 1015 IN LATR,Reach-1,4
Up Type=0
Dn Type=3
Dn Slope=0.005
Boundary for River Rch & Prof#=UNT 1015 IN LATR,Reach-1,5
Up Type=0
Dn Type=3
Dn Slope=0.005
Boundary for River Rch & Prof#=UNT 1015 IN LATR,Reach-1,6
Up Type=0
Dn Type=3
Dn Slope=0.005
Boundary for River Rch & Prof#=UNT 1015 IN LATR,Reach-1,7
Up Type=0
Dn Type=3
Dn Slope=0.005

--- UNT 0015 IN LATR.g01 (geometry) ---

Geom Title=Existing Conditions

River Reach=UNT 1015 IN LATR,Reach-1
Reach XY= 30
      2933659.14     10105103.73      2933917.51     10105200.95
      2934223.10     10105621.39      2934219.14     10106019.25
      2934647.29     10105906.27      2935699.87     10106450.34
      2936218.56     10106613.51      2936714.19     10106523.87
      2936775.91     10106277.22      2936982.71     10106185.15
      2937369.88     10106424.81      2937645.91     10106808.17
      2938107.98     10106803.68      2938144.27     10107166.70
      2937851.27     10107662.57      2938351.06     10108161.59
      2938424.75     10108398.84      2938269.34     10108764.19
      2937923.98     10109163.54      2938038.84     10110098.77
      2937928.47     10110583.73      2938063.54     10110901.06
      2938627.00     10111538.24      2939019.91     10111693.99
      2939538.41     10111429.77      2940183.52     10111549.80
      2940764.05     10111472.27      2941054.69     10111800.56
      2941535.80     10112128.11      2942058.47     10112283.73

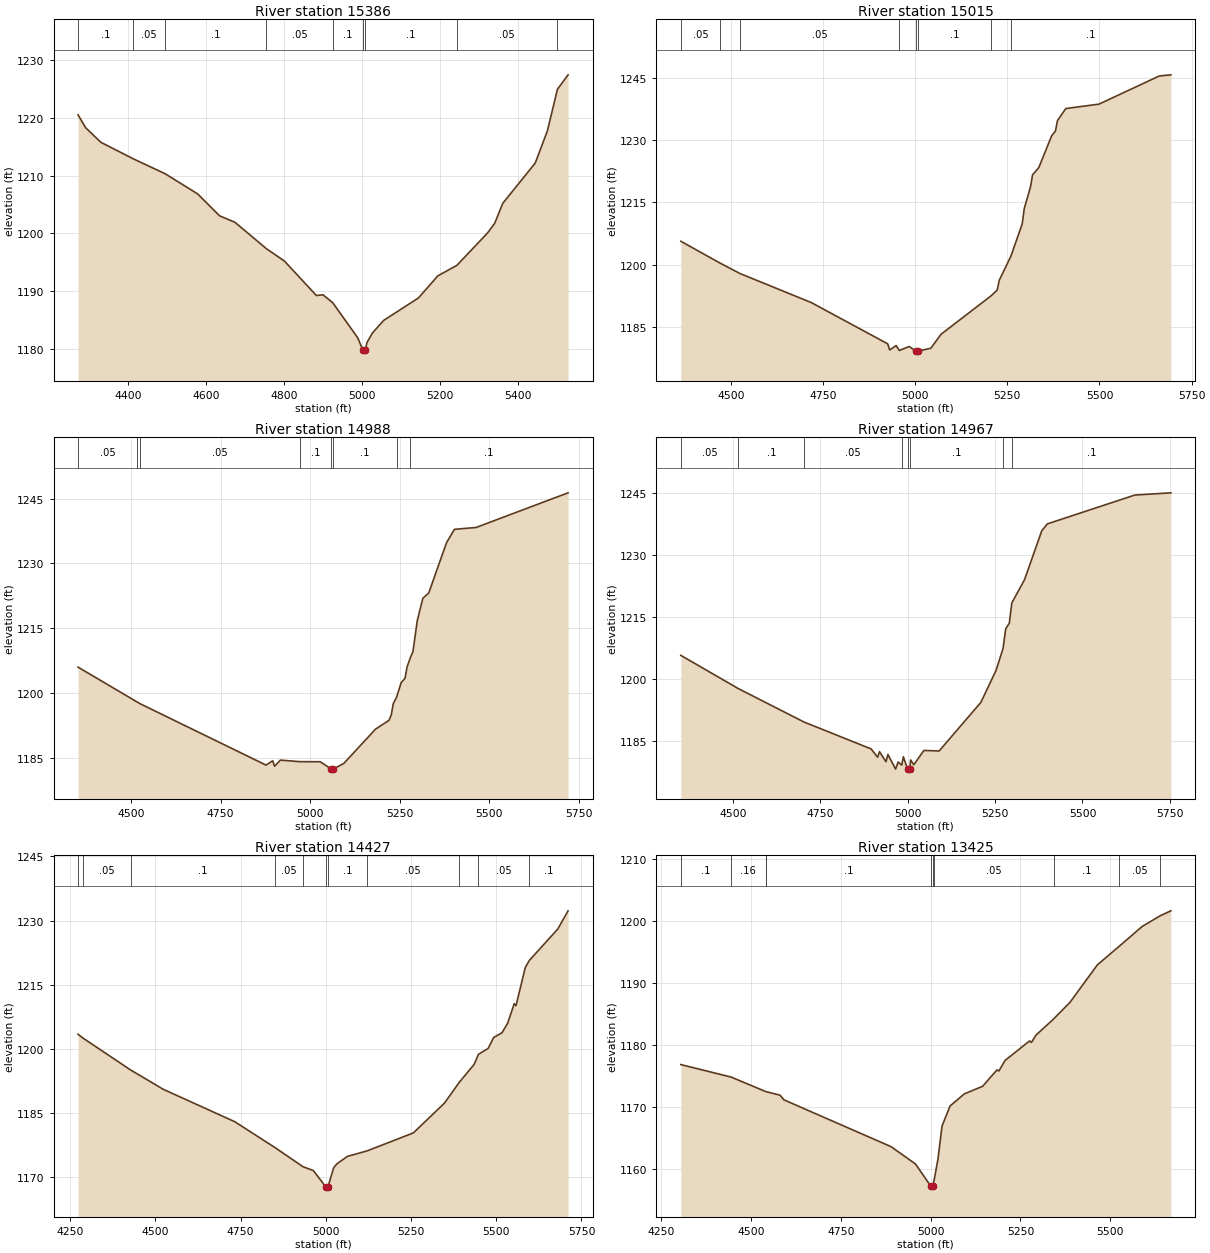
Type RM Length L Ch R = 1,15386,371,371,371
BEGIN DESCRIPTION:
UNT 1015 IN LATR 29.0
END DESCRIPTION:
XS GIS Cut Line= 4
      2933051.08     10105454.35      2933655.27     10105162.67
      2933699.54     10105055.90      2933832.36     10104602.76
#Sta/Elev= 30
  4270.9 1220.50  4290.2 1218.29  4329.4 1215.75  4412.8 1212.89  4494.8 1210.30
  4578.1 1206.82  4634.4 1203.03  4674.1 1201.90  4754.2 1197.37  4801.0 1195.20
  4883.1 1189.24  4900.1 1189.36  4925.3 1187.98  4989.3 1181.92  5002.6 1179.77
  5005.4 1179.27  5008.6 1179.77  5013.2 1181.12  5027.3 1182.77  5055.9 1184.93
  5145.3 1188.82  5195.1 1192.64  5244.0 1194.46  5322.8 1200.06  5341.0 1201.72
  5361.9 1205.19  5445.2 1212.15  5476.5 1217.74  5502.2 1224.91  5529.6 1227.42
#Mann=9,-1,0
  4270.9     0.1       0  4412.8    0.05       0  4494.8     0.1       0
  4754.2    0.05       0  4925.3     0.1       0  5002.6    0.07       0
  5008.6     0.1       0  5244.0    0.05       0  5502.2     0.1       0
Bank Sta=5002.6,5008.6
Exp/Cntr=0.3,0.1

Type RM Length L Ch R = 1,15015,27,27,27
BEGIN DESCRIPTION:
Mapping XS 8889e44e
END DESCRIPTION:
XS GIS Cut Line= 4
      2933405.19     10105542.88      2933941.69     10105321.51
      2934004.19     10105277.24      2934298.46     10104673.06
#Sta/Elev= 30
  4364.6 1205.65  4471.4 1200.36  4525.1 1197.86  4718.0 1190.87  4925.6 1180.90
  4931.1 1179.41  4948.5 1180.47  4957.2 1179.29  4984.1 1180.25  5002.1 1179.15
  5004.8 1178.65  5008.1 1179.15  5042.5 1179.82  5070.6 1183.22  5206.4 1192.50
  5222.8 1193.89  5228.3 1196.24  5259.7 1202.02  5290.4 1209.81  5296.0 1213.53
  5312.9 1218.74  5318.5 1221.68  5335.5 1223.42  5370.3 1231.10  5380.6 1232.24
  5386.1 1234.77  5408.7 1237.67  5498.8 1238.74  5662.2 1245.53  5693.6 1245.81
#Mann=8,-1,0
  4364.6    0.05       0  4471.4     0.1       0  4525.1    0.05       0
  4957.2     0.1       0  5002.1    0.07       0  5008.1     0.1       0
  5206.4    0.05       0  5259.7     0.1       0
Bank Sta=5002.1,5008.1
Exp/Cntr=0.3,0.1

Type RM Length L Ch R = 1,14988,21,21,21
BEGIN DESCRIPTION:
Mapping XS e3bee7a9
END DESCRIPTION:
XS GIS Cut Line= 4
      2933405.23     10105566.30      2933959.92     10105339.74
      2934017.21     10105300.67      2934342.73     10104680.87
#Sta/Elev= 30
  4351.8 1205.98  4515.5 1197.98  4525.5 1197.50  4876.7 1183.31  4895.4 1184.30
  4900.8 1183.04  4917.0 1184.46  4971.2 1184.10  5028.1 1184.08  5059.0 1182.41
  5061.8 1181.91  5065.0 1182.41  5094.3 1183.71  5182.5 1191.62  5220.2 1193.67
  5226.6 1194.91  5232.2 1197.53  5241.2 1198.98  5254.3 1202.39  5265.0 1203.41
  5270.7 1206.01  5279.9 1208.17  5287.1 1209.57  5299.2 1216.73  5314.8 1221.92
  5331.2 1223.13  5380.9 1234.78  5403.0 1237.88  5463.5 1238.31  5720.4 1246.33
#Mann=8,-1,0
  4351.8    0.05       0  4515.5     0.1       0  4525.5    0.05       0
  4971.2     0.1       0  5059.0    0.07       0  5065.0     0.1       0
  5241.2    0.05       0  5279.9     0.1       0
Bank Sta=5059,5065
Exp/Cntr=0.3,0.1

Type RM Length L Ch R = 1,14967,540,540,540
BEGIN DESCRIPTION:
Mapping XS 8f1f9419
END DESCRIPTION:
XS GIS Cut Line= 4
      2933415.67     10105584.52      2933983.35     10105350.15
      2934032.83     10105316.30      2934383.83     10104679.31
#Sta/Elev= 30
  4351.3 1205.72  4516.2 1197.64  4703.8 1189.55  4895.6 1183.03  4914.1 1181.03
  4919.5 1182.37  4938.0 1179.93  4943.5 1181.69  4965.5 1178.15  4972.8 1179.86
  4983.1 1179.11  4987.8 1181.14  4999.7 1178.15  5002.4 1177.65  5005.7 1178.15
  5008.7 1180.36  5017.6 1179.20  5046.5 1182.67  5090.0 1182.53  5209.3 1194.31
  5252.8 1202.08  5272.8 1207.40  5280.3 1212.13  5290.7 1213.52  5297.9 1218.44
  5334.2 1224.06  5383.5 1235.92  5399.6 1237.60  5649.5 1244.59  5752.7 1245.13
#Mann=8,-1,0
  4351.3    0.05       0  4516.2     0.1       0  4703.8    0.05       0
  4983.1     0.1       0  4999.7    0.07       0  5005.7     0.1       0
  5272.8    0.05       0  5297.9     0.1       0
Bank Sta=4999.7,5005.7
Exp/Cntr=0.3,0.1

Type RM Length L Ch R = 1,14427,1002,1002,1002
BEGIN DESCRIPTION:
UNT 1015 IN LATR 28.0
END DESCRIPTION:
XS GIS Cut Line= 4
      2933488.56     10105772.04      2934306.31     10105795.48
      2934449.54     10105712.15      2934561.51     10105272.07
#Sta/Elev= 30
  4272.8 1203.43  4286.2 1202.59  4426.8 1195.08  4522.8 1190.55  4732.9 1182.96
  4850.1 1176.95  4933.3 1172.42  4963.0 1171.56  5000.0 1167.70  5002.8 1167.20
  5006.0 1167.70  5023.0 1172.24  5033.0 1173.15  5063.0 1174.85  5120.4 1176.13
  5256.6 1180.34  5347.8 1187.30  5391.7 1192.21  5435.1 1196.38  5447.7 1198.74
  5476.1 1200.10  5492.3 1202.66  5517.0 1203.80  5533.6 1206.03  5552.7 1210.58
  5557.9 1210.11  5585.2 1219.04  5596.7 1220.66  5680.6 1228.05  5710.7 1232.29
#Mann=11,-1,0
  4272.8     0.1       0  4286.2    0.05       0  4426.8     0.1       0
  4850.1    0.05       0  4933.3     0.1       0  5000.0    0.07       0
  5006.0     0.1       0  5120.4    0.05       0  5391.7     0.1       0
  5447.7    0.05       0  5596.7     0.1       0
Bank Sta=5000,5006
Exp/Cntr=0.3,0.1

Type RM Length L Ch R = 1,13425,786,786,786
BEGIN DESCRIPTION:
UNT 1015 IN LATR 25.0
END DESCRIPTION:
XS GIS Cut Line= 4
      2934385.27     10106374.46      2934806.27     10106305.01
      2935049.33     10105797.20      2935014.60     10105423.89
#Sta/Elev= 30
  4304.2 1176.85  4444.4 1174.84  4540.2 1172.52  4541.1 1172.50  4580.6 1171.93
  4591.2 1171.18  4889.8 1163.64  4957.8 1160.85  5000.1 1157.31  5002.9 1156.81
  5006.1 1157.31  5009.7 1158.30  5020.3 1161.63  5031.6 1166.96  5054.0 1170.19
  5093.8 1172.14  5144.7 1173.36  5184.5 1175.99  5190.0 1175.82  5207.2 1177.52
  5275.2 1180.65  5280.7 1180.42  5293.0 1181.58  5342.3 1184.19  5387.7 1186.85
  5464.1 1192.89  5525.3 1195.90  5588.6 1199.06  5639.7 1200.81  5668.8 1201.59
#Mann=10,-1,0
  4304.2     0.1       0  4444.4    0.16       0  4540.2    0.05       0
  4541.1     0.1       0  5000.1    0.07       0  5006.1     0.1       0
  5009.7    0.05       0  5342.3     0.1       0  5525.3    0.05       0
  5639.7     0.1       0
Bank Sta=5000.1,5006.1
Exp/Cntr=0.3,0.1

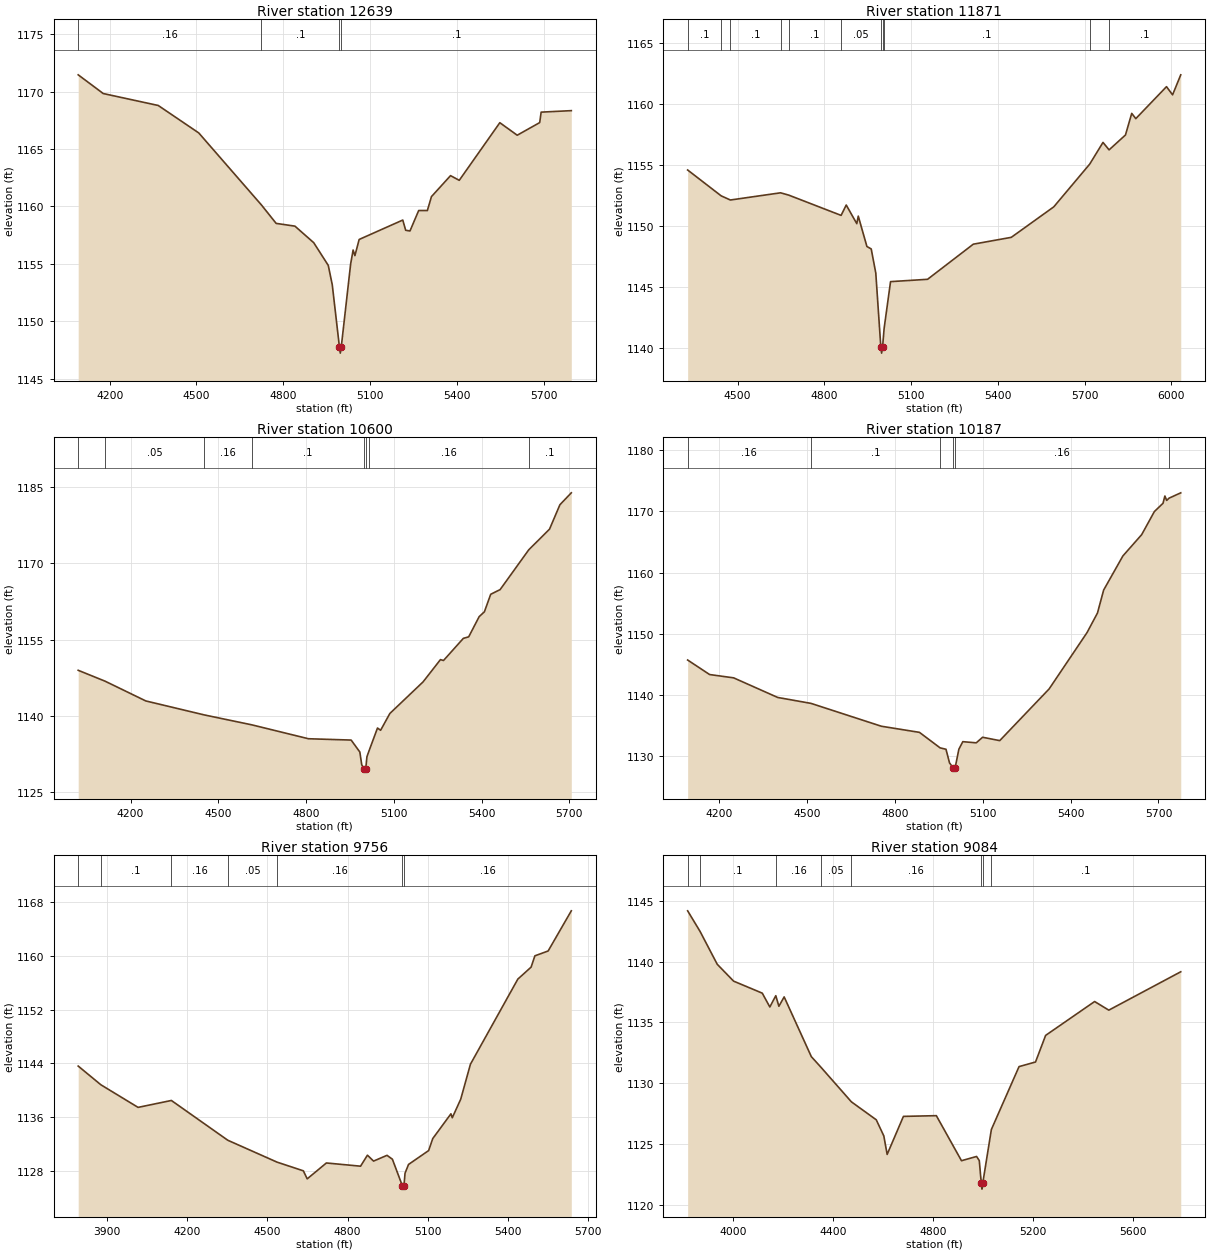
Type RM Length L Ch R = 1,12639,768,768,768
BEGIN DESCRIPTION:
UNT 1015 IN LATR 24.0
END DESCRIPTION:
XS GIS Cut Line= 4
      2934801.88     10106582.79      2935483.35     10106582.79
      2935748.11     10106218.21      2935717.82     10105647.06
#Sta/Elev= 30
  4091.3 1171.46  4177.9 1169.83  4367.9 1168.79  4507.9 1166.40  4724.7 1160.12
  4775.4 1158.52  4840.3 1158.28  4905.2 1156.84  4955.5 1154.86  4969.3 1153.17
  4994.2 1147.72  4997.0 1147.22  5000.2 1147.72  5032.8 1154.99  5041.3 1156.20
  5047.5 1155.71  5062.2 1157.12  5212.9 1158.81  5223.0 1157.92  5237.8 1157.86
  5267.9 1159.64  5297.9 1159.64  5312.0 1160.85  5378.0 1162.68  5408.1 1162.27
  5548.3 1167.29  5608.4 1166.20  5686.1 1167.30  5691.1 1168.21  5795.3 1168.34
#Mann=4,-1,0
  4091.3    0.16       0  4724.7     0.1       0  4994.2    0.07       0
  5000.2     0.1       0
Bank Sta=4994.2,5000.2
Exp/Cntr=0.3,0.1

Type RM Length L Ch R = 1,11871,1271,1271,1271
BEGIN DESCRIPTION:
UNT 1015 IN LATR 23.0
END DESCRIPTION:
XS GIS Cut Line= 4
      2936077.99     10107181.72      2936373.11     10106791.12
      2936216.86     10106044.60      2935884.31     10105737.96
#Sta/Elev= 30
  4327.6 1154.63  4443.5 1152.51  4475.3 1152.17  4648.8 1152.76  4677.2 1152.57
  4858.0 1150.91  4875.8 1151.76  4912.3 1150.23  4917.4 1150.85  4947.3 1148.36
  4962.2 1148.16  4978.0 1146.18  4995.4 1140.12  4998.1 1139.62  5001.4 1140.12
  5006.8 1141.65  5029.0 1145.48  5156.9 1145.67  5315.1 1148.55  5446.4 1149.11
  5593.3 1151.61  5717.4 1155.11  5763.4 1156.89  5784.5 1156.28  5841.1 1157.50
  5862.7 1159.27  5876.8 1158.84  5982.9 1161.46  6003.9 1160.79  6032.2 1162.43
#Mann=11,-1,0
  4327.6     0.1       0  4443.5    0.16       0  4475.3     0.1       0
  4648.8    0.05       0  4677.2     0.1       0  4858.0    0.05       0
  4995.4   0.035       0  5001.4    0.05       0  5006.8     0.1       0
  5717.4    0.05       0  5784.5     0.1       0
Bank Sta=4995.4,5001.4
Exp/Cntr=0.3,0.1

Type RM Length L Ch R = 1,10600,413,413,413
BEGIN DESCRIPTION:
UNT 1015 IN LATR 22.0
END DESCRIPTION:
XS GIS Cut Line= 3
      2936472.90     10106825.86      2937210.78     10106539.39
      2937540.10     10105707.43
#Sta/Elev= 30
  4020.8 1148.95  4112.9 1146.80  4252.0 1142.91  4451.7 1140.16  4615.3 1138.19
  4808.4 1135.46  4954.2 1135.20  4983.9 1132.85  4990.5 1130.31  4998.3 1129.58
  5001.0 1129.08  5004.3 1129.58  5008.2 1131.92  5015.1 1133.03  5044.3 1137.57
  5055.0 1137.13  5086.6 1140.44  5200.1 1146.66  5259.6 1151.05  5270.1 1150.88
  5337.9 1155.24  5356.2 1155.54  5392.0 1159.52  5409.9 1160.48  5431.5 1163.93
  5463.7 1164.85  5561.6 1172.69  5632.6 1176.76  5668.1 1181.57  5707.1 1183.92
#Mann=8,-1,0
  4020.8     0.1       0  4112.9    0.05       0  4451.7    0.16       0
  4615.3     0.1       0  4998.3    0.07       0  5004.3     0.1       0
  5015.1    0.16       0  5561.6     0.1       0
Bank Sta=4998.3,5004.3
Exp/Cntr=0.3,0.1

Type RM Length L Ch R = 1,10187,431,431,431
BEGIN DESCRIPTION:
UNT 1015 IN LATR 21.0
END DESCRIPTION:
XS GIS Cut Line= 4
      2936663.94     10106899.63      2937293.25     10106812.83
      2937827.10     10106513.35      2938073.99     10106153.84
#Sta/Elev= 30
  4092.5 1145.72  4167.5 1143.35  4249.5 1142.81  4399.9 1139.61  4513.7 1138.64
  4753.8 1134.91  4883.9 1133.91  4954.3 1131.38  4974.5 1131.15  4986.6 1128.92
  4999.5 1128.08  5002.3 1127.58  5005.5 1128.08  5018.5 1131.16  5031.9 1132.39
  5077.7 1132.20  5099.5 1133.11  5158.0 1132.56  5326.6 1141.00  5455.9 1150.19
  5491.7 1153.40  5512.7 1157.14  5578.4 1162.71  5642.7 1166.20  5685.9 1169.96
  5715.5 1171.32  5721.8 1172.50  5727.9 1171.78  5736.1 1172.15  5776.0 1173.02
#Mann=6,-1,0
  4092.5    0.16       0  4513.7     0.1       0  4954.3    0.16       0
  4999.5    0.07       0  5005.5    0.16       0  5736.1     0.1       0
Bank Sta=4999.5,5005.5
Exp/Cntr=0.3,0.1

Type RM Length L Ch R = 1,9756,672,672,672
BEGIN DESCRIPTION:
UNT 1015 IN LATR 20.0
END DESCRIPTION:
XS GIS Cut Line= 4
      2937067.59     10107598.39      2937909.57     10106912.65
      2937870.51     10106578.45      2938139.59     10106252.94
#Sta/Elev= 30
  3792.2 1143.60  3877.1 1140.81  4016.2 1137.44  4140.8 1138.47  4351.8 1132.54
  4536.4 1129.27  4634.5 1127.98  4648.9 1126.78  4720.7 1129.15  4848.5 1128.67
  4874.2 1130.31  4897.1 1129.43  4947.5 1130.29  4967.6 1129.71  5004.9 1125.75
  5007.6 1125.25  5010.9 1125.75  5014.9 1127.62  5028.0 1128.93  5103.2 1131.00
  5118.6 1132.79  5186.6 1136.48  5191.6 1135.89  5223.2 1138.66  5259.6 1143.88
  5436.9 1156.57  5486.4 1158.35  5500.7 1160.04  5550.2 1160.76  5636.9 1166.75
#Mann=7,-1,0
  3792.2    0.16       0  3877.1     0.1       0  4140.8    0.16       0
  4351.8    0.05       0  4536.4    0.16       0  5004.9    0.07       0
  5010.9    0.16       0
Bank Sta=5004.9,5010.9
Exp/Cntr=0.3,0.1

Type RM Length L Ch R = 1,9084,725,725,725
BEGIN DESCRIPTION:
UNT 1015 IN LATR 19.0
END DESCRIPTION:
XS GIS Cut Line= 4
      2937089.24     10107628.81      2937857.48     10107129.67
      2938261.13     10107298.94      2938873.13     10107207.79
#Sta/Elev= 30
  3819.7 1144.19  3869.5 1142.49  3938.0 1139.79  4003.5 1138.40  4118.2 1137.41
  4148.5 1136.27  4172.3 1137.20  4184.7 1136.33  4205.8 1137.10  4314.5 1132.18
  4353.7 1131.29  4474.7 1128.46  4574.2 1126.98  4604.5 1125.65  4617.8 1124.13
  4682.9 1127.26  4814.6 1127.32  4915.1 1123.61  4975.5 1123.96  4986.3 1123.62
  4994.3 1121.77  4997.1 1121.27  5000.3 1121.77  5034.7 1126.18  5145.4 1131.36
  5211.3 1131.74  5251.7 1133.93  5447.7 1136.72  5504.5 1136.01  5792.3 1139.17
#Mann=8,-1,0
  3819.7    0.16       0  3869.5     0.1       0  4172.3    0.16       0
  4353.7    0.05       0  4474.7    0.16       0  4994.3    0.07       0
  5000.3    0.16       0  5034.7     0.1       0
Bank Sta=4994.3,5000.3
Exp/Cntr=0.3,0.1

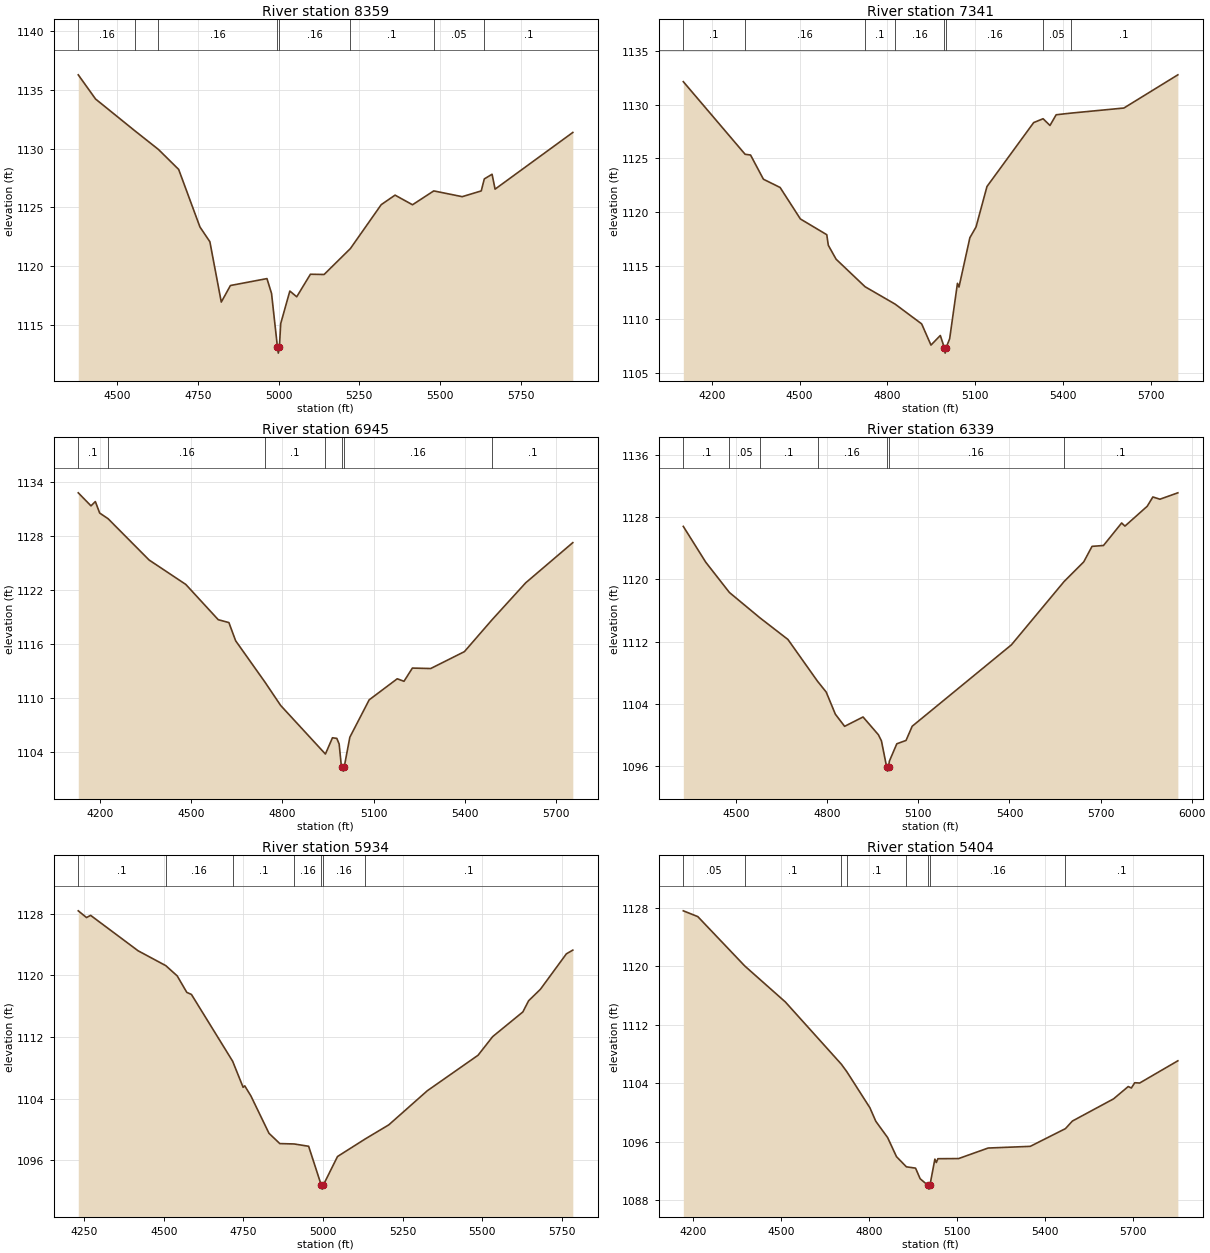
Type RM Length L Ch R = 1,8359,1018,1018,1018
BEGIN DESCRIPTION:
UNT 1015 IN LATR 17.0
END DESCRIPTION:
XS GIS Cut Line= 4
      2937445.19     10108140.94      2937801.06     10107980.36
      2938161.30     10107628.80      2938782.01     10107485.56
#Sta/Elev= 30
  4379.9 1136.28  4433.4 1134.22  4554.7 1131.52  4628.2 1129.92  4690.7 1128.22
  4756.5 1123.32  4787.3 1122.06  4822.6 1116.92  4850.9 1118.33  4964.0 1118.92
  4978.2 1117.65  4996.5 1113.07  4999.2 1112.57  5002.5 1113.07  5006.5 1115.08
  5034.8 1117.86  5056.1 1117.37  5098.5 1119.29  5140.9 1119.27  5222.3 1121.48
  5317.7 1125.22  5360.5 1126.03  5414.5 1125.21  5480.3 1126.39  5568.4 1125.90
  5627.3 1126.39  5636.7 1127.41  5660.8 1127.81  5670.1 1126.54  5910.7 1131.37
#Mann=8,-1,0
  4379.9    0.16       0  4554.7     0.1       0  4628.2    0.16       0
  4996.5    0.07       0  5002.5    0.16       0  5222.3     0.1       0
  5480.3    0.05       0  5636.7     0.1       0
Bank Sta=4996.5,5002.5
Exp/Cntr=0.3,0.1

Type RM Length L Ch R = 1,7341,396,396,396
BEGIN DESCRIPTION:
UNT 1015 IN LATR 15.0
END DESCRIPTION:
XS GIS Cut Line= 2
      2937488.56     10108336.26      2939093.42     10108861.10
#Sta/Elev= 30
  4103.1 1132.17  4314.1 1125.39  4332.7 1125.32  4376.6 1123.06  4433.6 1122.29
  4502.8 1119.35  4592.9 1117.88  4598.2 1116.89  4624.8 1115.59  4723.7 1113.02
  4826.1 1111.40  4916.9 1109.55  4948.7 1107.57  4980.6 1108.47  4994.3 1107.32
  4997.1 1106.82  5000.3 1107.32  5012.5 1108.17  5039.1 1113.34  5044.3 1112.99
  5081.5 1117.60  5102.5 1118.60  5139.9 1122.38  5299.3 1128.35  5331.5 1128.71
  5355.0 1128.08  5376.1 1129.08  5425.2 1129.23  5607.5 1129.71  5791.6 1132.81
#Mann=8,-1,0
  4103.1     0.1       0  4314.1    0.16       0  4723.7     0.1       0
  4826.1    0.16       0  4994.3    0.07       0  5000.3    0.16       0
  5331.5    0.05       0  5425.2     0.1       0
Bank Sta=4994.3,5000.3
Exp/Cntr=0.3,0.1

Type RM Length L Ch R = 1,6945,606,606,606
BEGIN DESCRIPTION:
UNT 1015 IN LATR 14.0
END DESCRIPTION:
XS GIS Cut Line= 3
      2937440.80     10108362.29      2938261.13     10109052.41
      2938812.37     10109121.86
#Sta/Elev= 30
  4128.3 1132.80  4170.2 1131.35  4184.5 1131.83  4198.8 1130.55  4226.5 1129.92
  4361.4 1125.33  4482.3 1122.61  4589.0 1118.69  4624.1 1118.37  4646.2 1116.35
  4742.5 1111.76  4794.5 1109.15  4941.7 1103.75  4964.9 1105.56  4979.2 1105.49
  4986.9 1104.87  4993.5 1102.63  4997.8 1102.35  5000.6 1101.85  5003.8 1102.35
  5022.1 1105.62  5085.8 1109.78  5178.1 1112.12  5200.3 1111.84  5227.9 1113.31
  5288.3 1113.26  5399.2 1115.14  5489.5 1118.66  5600.8 1122.79  5755.9 1127.26
#Mann=7,-1,0
  4128.3     0.1       0  4226.5    0.16       0  4742.5     0.1       0
  4941.7    0.16       0  4997.8    0.07       0  5003.8    0.16       0
  5489.5     0.1       0
Bank Sta=4997.8,5003.8
Exp/Cntr=0.3,0.1

Type RM Length L Ch R = 1,6339,405,405,405
BEGIN DESCRIPTION:
UNT 1015 IN LATR 13.0
END DESCRIPTION:
XS GIS Cut Line= 3
      2937293.24     10109560.22      2938356.62     10109399.63
      2938884.75     10109235.13
#Sta/Elev= 30
  4326.0 1126.79  4400.0 1122.19  4477.8 1118.31  4578.2 1115.06  4670.5 1112.28
  4768.1 1106.91  4796.5 1105.53  4826.8 1102.68  4857.2 1101.13  4917.9 1102.33
  4968.4 1100.05  4978.5 1099.26  4995.8 1095.88  4998.5 1095.38  5001.8 1095.88
  5004.7 1096.67  5029.1 1098.89  5059.5 1099.32  5079.7 1101.14  5406.5 1111.59
  5580.3 1119.73  5644.7 1122.24  5672.0 1124.23  5709.7 1124.34  5769.5 1127.23
  5780.4 1126.83  5853.8 1129.38  5872.3 1130.57  5895.6 1130.28  5954.6 1131.10
#Mann=7,-1,0
  4326.0     0.1       0  4477.8    0.05       0  4578.2     0.1       0
  4768.1    0.16       0  4995.8    0.07       0  5001.8    0.16       0
  5580.3     0.1       0
Bank Sta=4995.8,5001.8
Exp/Cntr=0.3,0.1

Type RM Length L Ch R = 1,5934,530,530,530
BEGIN DESCRIPTION:
UNT 1015 IN LATR 12.0
END DESCRIPTION:
XS GIS Cut Line= 3
      2937249.88     10109942.16      2938447.76     10109794.60
      2938777.64     10109686.09
#Sta/Elev= 30
  4230.8 1128.38  4256.7 1127.51  4269.7 1127.79  4419.1 1123.19  4505.8 1121.27
  4541.7 1119.94  4571.9 1117.80  4586.5 1117.53  4715.9 1108.87  4748.9 1105.48
  4754.0 1105.67  4773.5 1104.35  4830.1 1099.52  4864.1 1098.18  4909.1 1098.13
  4954.8 1097.83  4994.6 1092.77  4997.3 1092.27  5000.6 1092.77  5045.5 1096.50
  5132.2 1098.77  5206.7 1100.61  5327.6 1105.03  5487.2 1109.64  5533.2 1112.06
  5628.0 1115.26  5646.1 1116.71  5683.2 1118.20  5764.8 1122.80  5785.0 1123.28
#Mann=7,-1,0
  4230.8     0.1       0  4505.8    0.16       0  4715.9     0.1       0
  4909.1    0.16       0  4994.6    0.07       0  5000.6    0.16       0
  5132.2     0.1       0
Bank Sta=4994.6,5000.6
Exp/Cntr=0.3,0.1

Type RM Length L Ch R = 1,5404,620,620,620
BEGIN DESCRIPTION:
UNT 1015 IN LATR 11.0
END DESCRIPTION:
XS GIS Cut Line= 4
      2937228.17     10110024.64      2937718.60     10110328.45
      2938209.05     10110397.90      2938760.26     10110120.12
#Sta/Elev= 30
  4165.4 1127.57  4214.9 1126.78  4375.3 1120.03  4513.9 1115.11  4705.6 1106.58
  4724.0 1105.57  4802.8 1100.64  4823.0 1098.79  4863.4 1096.56  4893.7 1093.95
  4927.5 1092.56  4958.8 1092.38  4974.5 1090.93  5001.8 1090.01  5004.5 1089.51
  5007.8 1090.01  5024.8 1093.61  5029.8 1093.15  5035.1 1093.67  5105.9 1093.69
  5206.8 1095.13  5350.7 1095.36  5470.8 1097.78  5494.6 1098.82  5635.1 1101.85
  5685.4 1103.54  5696.1 1103.34  5707.7 1104.06  5724.4 1104.02  5854.9 1107.06
#Mann=8,-1,0
  4165.4    0.05       0  4375.3     0.1       0  4705.6    0.16       0
  4724.0     0.1       0  4927.5    0.16       0  5001.8    0.07       0
  5007.8    0.16       0  5470.8     0.1       0
Bank Sta=5001.8,5007.8
Exp/Cntr=0.3,0.1

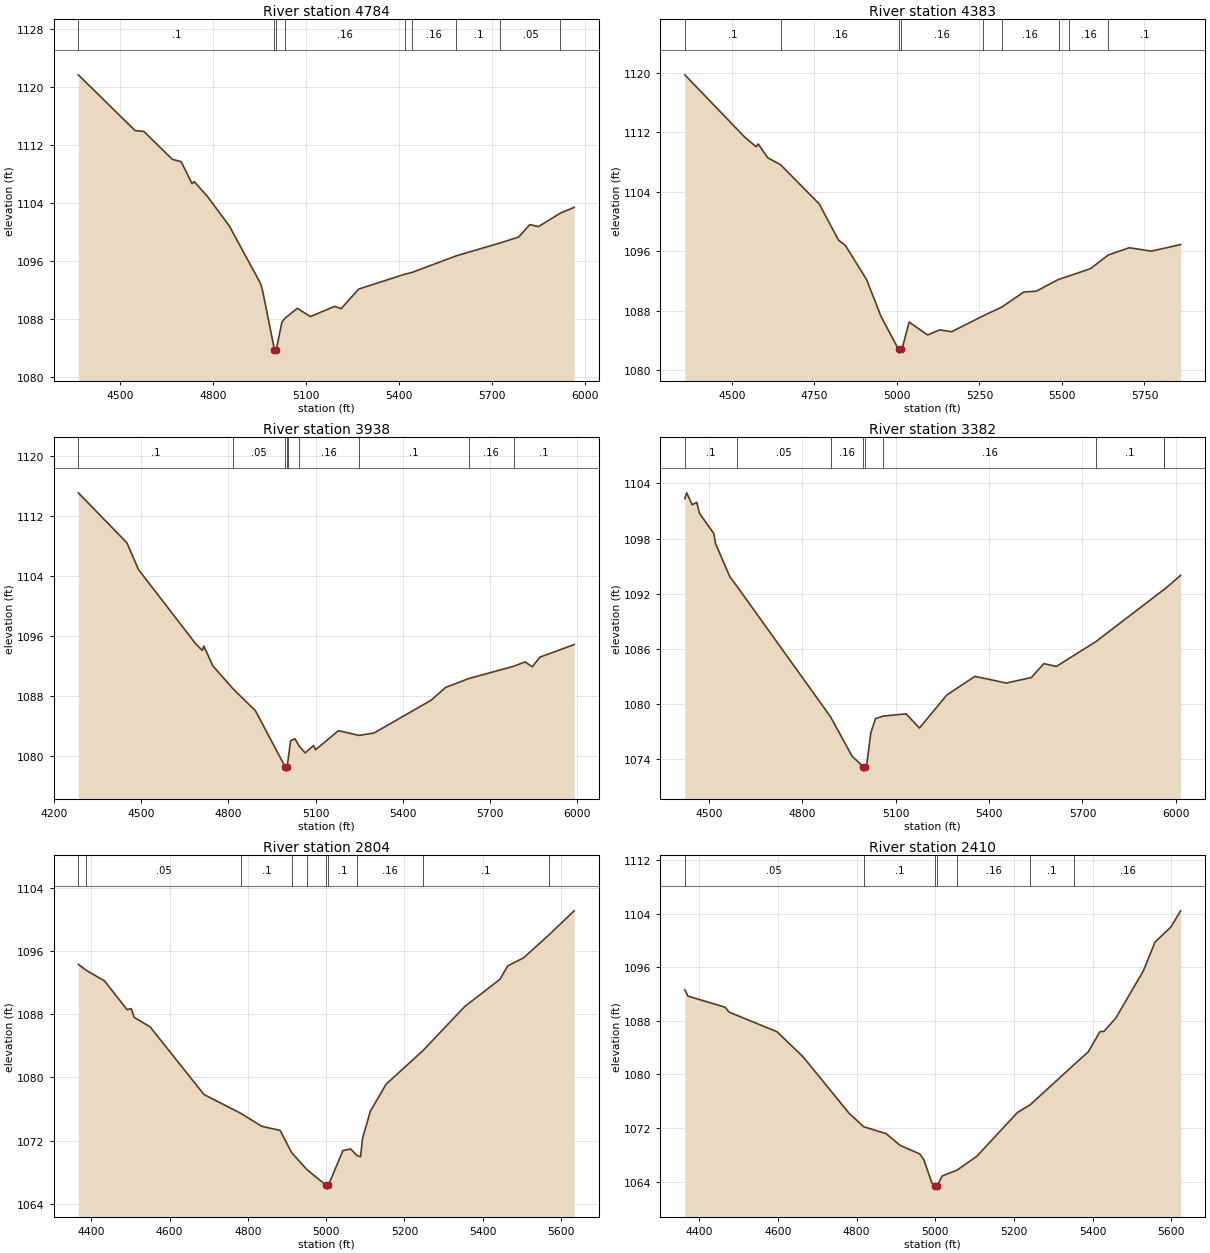
Type RM Length L Ch R = 1,4784,401,401,401
BEGIN DESCRIPTION:
UNT 1015 IN LATR 9.0
END DESCRIPTION:
XS GIS Cut Line= 3
      2937649.15     10111383.14      2938295.85     10110727.76
      2938768.97     10110241.62
#Sta/Elev= 30
  4365.3 1121.67  4548.2 1113.99  4576.5 1113.87  4668.5 1110.02  4696.8 1109.70
  4732.1 1106.66  4739.2 1106.94  4781.6 1104.91  4852.3 1100.83  4951.3 1093.04
  4958.4 1092.17  4997.8 1083.80  5000.5 1083.30  5003.8 1083.80  5022.1 1087.60
  5031.3 1088.08  5071.5 1089.48  5113.9 1088.34  5191.8 1089.75  5212.9 1089.43
  5269.5 1092.13  5417.5 1094.17  5441.8 1094.43  5583.9 1096.71  5726.5 1098.50
  5785.7 1099.31  5821.2 1101.02  5849.5 1100.75  5919.8 1102.60  5964.4 1103.40
#Mann=9,-1,0
  4365.3     0.1       0  4997.8    0.07       0  5003.8     0.1       0
  5031.3    0.16       0  5417.5     0.1       0  5441.8    0.16       0
  5583.9     0.1       0  5726.5    0.05       0  5919.8     0.1       0
Bank Sta=4997.8,5003.8
Exp/Cntr=0.3,0.1

Type RM Length L Ch R = 1,4383,445,445,445
BEGIN DESCRIPTION:
UNT 1015 IN LATR 8.0
END DESCRIPTION:
XS GIS Cut Line= 3
      2937844.47     10111621.85      2938573.63     10111066.30
      2938833.75     10110541.73
#Sta/Elev= 30
  4357.4 1119.71  4538.1 1111.37  4573.5 1110.04  4579.7 1110.41  4608.8 1108.55
  4647.6 1107.62  4764.8 1102.34  4822.9 1097.49  4843.7 1096.78  4908.2 1092.17
  4951.8 1087.22  5005.0 1082.78  5007.7 1082.28  5011.0 1082.78  5016.2 1082.95
  5037.0 1086.46  5093.2 1084.72  5129.3 1085.41  5165.9 1085.16  5259.6 1087.26
  5317.3 1088.46  5384.6 1090.50  5422.1 1090.61  5489.7 1092.19  5522.3 1092.67
  5586.4 1093.64  5640.5 1095.48  5704.0 1096.45  5771.3 1096.00  5859.6 1096.88
#Mann=9,-1,0
  4357.4     0.1       0  4647.6    0.16       0  5005.0    0.07       0
  5011.0    0.16       0  5259.6     0.1       0  5317.3    0.16       0
  5489.7     0.1       0  5522.3    0.16       0  5640.5     0.1       0
Bank Sta=5005,5011
Exp/Cntr=0.3,0.1

Type RM Length L Ch R = 1,3938,556,556,556
BEGIN DESCRIPTION:
UNT 1015 IN LATR 7.0
END DESCRIPTION:
XS GIS Cut Line= 4
      2938065.81     10111934.36      2938530.23     10111726.02
      2938790.64     10111374.46      2938942.47     10110628.36
#Sta/Elev= 30
  4282.9 1115.13  4450.2 1108.46  4490.3 1104.88  4686.7 1095.00  4709.9 1094.10
  4715.4 1094.66  4746.1 1092.04  4815.1 1089.00  4893.1 1086.03  4996.5 1078.48
  4999.3 1077.98  5002.5 1078.48  5004.8 1079.30  5014.1 1082.04  5028.8 1082.30
  5044.6 1081.28  5064.2 1080.41  5093.4 1081.40  5099.7 1080.83  5179.0 1083.38
  5249.7 1082.75  5301.6 1083.07  5497.4 1087.43  5548.0 1089.15  5627.9 1090.34
  5782.8 1091.98  5822.0 1092.56  5846.5 1091.91  5873.1 1093.20  5990.8 1094.87
#Mann=9,-1,0
  4282.9     0.1       0  4815.1    0.05       0  4996.5   0.035       0
  5002.5    0.05       0  5004.8     0.1       0  5044.6    0.16       0
  5249.7     0.1       0  5627.9    0.16       0  5782.8     0.1       0
Bank Sta=4996.5,5002.5
Exp/Cntr=0.3,0.1

Type RM Length L Ch R = 1,3382,578,578,578
BEGIN DESCRIPTION:
UNT 1015 IN LATR 6.0
END DESCRIPTION:
XS GIS Cut Line= 3
      2939393.94     10112168.72      2939085.78     10111482.96
      2938994.82     10110647.01
#Sta/Elev= 30
  4422.6 1102.33  4428.6 1102.97  4446.3 1101.68  4461.0 1101.94  4469.5 1100.75
  4515.8 1098.54  4521.3 1097.45  4567.6 1093.82  4589.6 1092.83  4890.7 1078.61
  4960.1 1074.32  4995.2 1073.20  4997.9 1072.70  5001.2 1073.20  5006.5 1073.28
  5020.1 1076.85  5035.1 1078.42  5060.5 1078.69  5133.2 1078.93  5176.5 1077.39
  5264.2 1080.98  5354.7 1083.01  5455.3 1082.28  5535.8 1082.88  5576.0 1084.39
  5616.2 1084.09  5742.8 1086.78  5960.9 1092.43  5962.5 1092.45  6015.3 1094.00
#Mann=9,-1,0
  4422.6     0.1       0  4589.6    0.05       0  4890.7    0.16       0
  4995.2    0.07       0  5001.2    0.16       0  5060.5    0.16       0
  5742.8     0.1       0  5960.9    0.05       0  5962.5     0.1       0
Bank Sta=4995.2,5001.2
Exp/Cntr=0.3,0.1

Type RM Length L Ch R = 1,2804,394,394,394
BEGIN DESCRIPTION:
UNT 1015 IN LATR 5.0
END DESCRIPTION:
XS GIS Cut Line= 3
      2939537.18     10112064.52      2939654.36     10111608.83
      2939715.12     10110814.57
#Sta/Elev= 30
  4366.6 1094.32  4386.7 1093.56  4433.3 1092.22  4491.3 1088.57  4501.6 1088.71
  4509.5 1087.60  4550.3 1086.39  4687.5 1077.85  4782.2 1075.45  4835.3 1073.82
  4882.3 1073.30  4911.8 1070.48  4950.8 1068.34  4999.7 1066.37  5002.4 1065.87
  5005.7 1066.37  5042.8 1070.75  5062.9 1070.95  5078.3 1070.14  5087.8 1069.96
  5093.0 1072.31  5113.0 1075.74  5153.1 1079.14  5247.2 1083.39  5354.3 1088.98
  5444.0 1092.41  5464.0 1094.12  5504.2 1095.12  5569.7 1098.05  5633.7 1101.08
#Mann=10,-1,0
  4366.6     0.1       0  4386.7    0.05       0  4782.2     0.1       0
  4911.8    0.05       0  4950.8     0.1       0  4999.7    0.07       0
  5005.7     0.1       0  5078.3    0.16       0  5247.2     0.1       0
  5569.7    0.05       0
Bank Sta=4999.7,5005.7
Exp/Cntr=0.3,0.1

Type RM Length L Ch R = 1,2410,369,369,369
BEGIN DESCRIPTION:
UNT 1015 IN LATR 4.0
END DESCRIPTION:
XS GIS Cut Line= 4
      2939732.51     10112090.57      2940010.26     10111634.87
      2940088.39     10111361.44      2940092.73     10110918.71
#Sta/Elev= 30
  4363.2 1092.64  4371.2 1091.69  4465.9 1090.03  4475.5 1089.31  4597.6 1086.37
  4664.0 1082.63  4781.1 1074.19  4818.2 1072.19  4874.8 1071.17  4911.1 1069.40
  4960.5 1068.14  4970.9 1067.29  4991.7 1063.78  4999.1 1063.38  5001.8 1062.88
  5005.1 1063.38  5017.7 1064.85  5055.0 1065.70  5106.1 1067.80  5209.0 1074.32
  5241.5 1075.47  5353.3 1081.48  5389.0 1083.36  5419.0 1086.39  5429.0 1086.43
  5459.0 1088.39  5529.0 1095.44  5559.0 1099.76  5599.0 1101.99  5624.0 1104.42
#Mann=7,-1,0
  4363.2    0.05       0  4818.2     0.1       0  4999.1    0.07       0
  5005.1     0.1       0  5055.0    0.16       0  5241.5     0.1       0
  5353.3    0.16       0
Bank Sta=4999.1,5005.1
Exp/Cntr=0.3,0.1

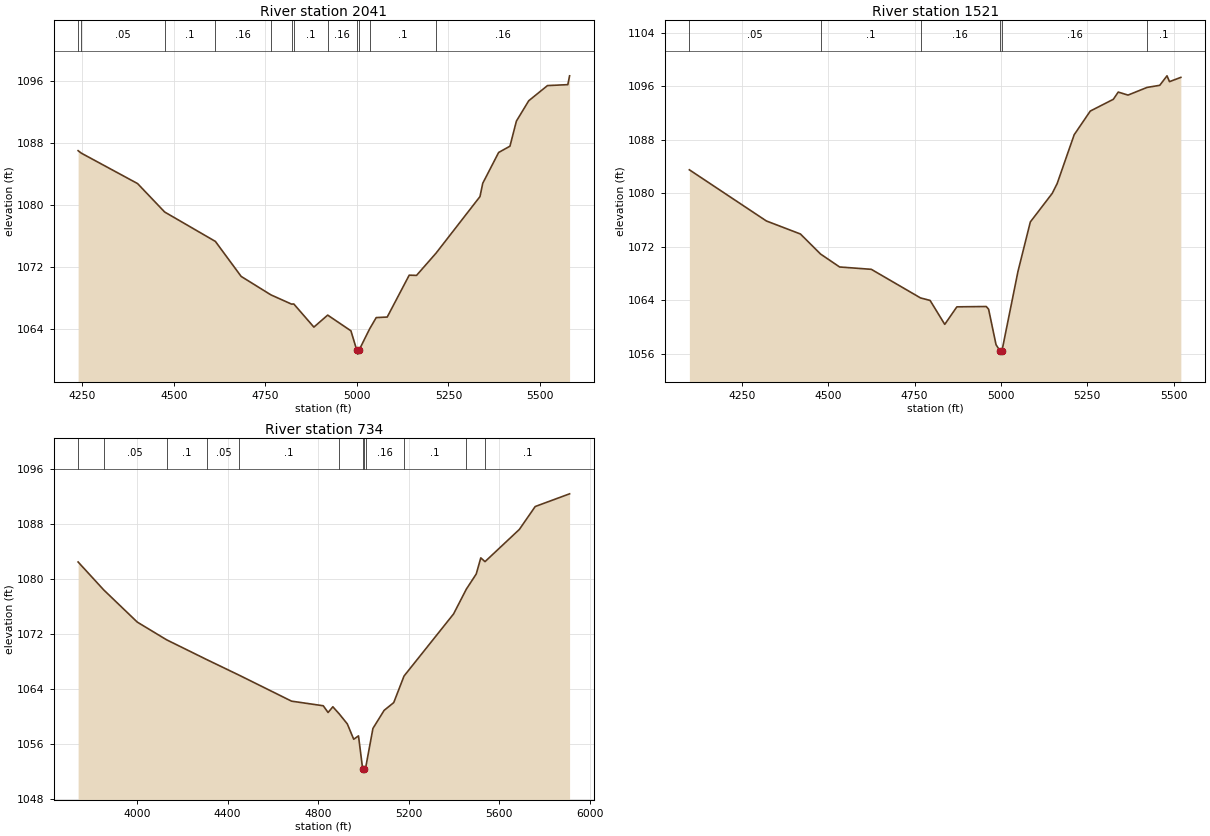
Type RM Length L Ch R = 1,2041,520,520,520
BEGIN DESCRIPTION:
UNT 1015 IN LATR 3.0
END DESCRIPTION:
XS GIS Cut Line= 4
      2940049.31     10112134.02      2940413.91     10111743.38
      2940392.21     10111313.69      2940474.67     10110944.78
#Sta/Elev= 30
  4238.5 1087.05  4247.7 1086.72  4401.0 1082.80  4474.9 1079.13  4613.5 1075.33
  4683.9 1070.81  4765.0 1068.43  4821.6 1067.23  4827.7 1067.25  4882.6 1064.26
  4920.3 1065.81  4983.8 1063.78  4999.8 1061.27  5002.5 1060.77  5005.8 1061.27
  5035.2 1064.06  5052.9 1065.49  5082.9 1065.56  5143.0 1070.97  5163.0 1070.94
  5216.4 1073.82  5336.3 1081.12  5343.9 1082.84  5387.3 1086.82  5418.2 1087.63
  5435.8 1090.87  5469.5 1093.50  5520.7 1095.46  5576.3 1095.58  5581.1 1096.72
#Mann=12,-1,0
  4238.5     0.1       0  4247.7    0.05       0  4474.9     0.1       0
  4613.5    0.16       0  4765.0     0.1       0  4821.6    0.16       0
  4827.7     0.1       0  4920.3    0.16       0  4999.8    0.07       0
  5005.8    0.16       0  5035.2     0.1       0  5216.4    0.16       0
Bank Sta=4999.8,5005.8
Exp/Cntr=0.3,0.1

Type RM Length L Ch R = 1,1521,787,787,787
BEGIN DESCRIPTION:
UNT 1015 IN LATR 2.0
END DESCRIPTION:
XS GIS Cut Line= 3
      2940222.92     10112173.09      2941077.97     10111383.14
      2941254.67     10111193.51
#Sta/Elev= 30
  4097.7 1083.52  4320.7 1075.87  4419.4 1073.92  4477.5 1070.93  4532.8 1068.99
  4624.6 1068.64  4767.2 1064.36  4794.8 1063.99  4837.3 1060.41  4872.4 1063.03
  4957.5 1063.08  4964.3 1062.67  4985.8 1057.38  4997.0 1056.46  4999.8 1055.96
  5003.0 1056.46  5049.4 1068.34  5085.1 1075.72  5148.6 1080.00  5162.8 1081.46
  5212.1 1088.76  5258.7 1092.30  5325.5 1094.06  5339.7 1095.14  5368.0 1094.69
  5423.4 1095.84  5459.9 1096.15  5480.9 1097.57  5488.2 1096.70  5521.0 1097.34
#Mann=6,-1,0
  4097.7    0.05       0  4477.5     0.1       0  4767.2    0.16       0
  4997.0    0.07       0  5003.0    0.16       0  5423.4     0.1       0
Bank Sta=4997,5003
Exp/Cntr=0.3,0.1

Type RM Length L Ch R = 1,734,0,0,0
BEGIN DESCRIPTION:
UNT 1015 IN LATR 1.0
END DESCRIPTION:
XS GIS Cut Line= 4
      2940257.65     10112251.19      2941308.01     10112186.09
      2941598.80     10111903.97      2941637.87     10111192.18
#Sta/Elev= 30
  3739.5 1082.50  3852.9 1078.42  4000.8 1073.74  4130.3 1071.16  4309.9 1068.24
  4451.6 1065.99  4682.1 1062.22  4822.1 1061.55  4843.4 1060.57  4864.5 1061.40
  4892.0 1060.39  4928.3 1058.91  4956.6 1056.67  4977.7 1057.16  4996.0 1052.38
  4998.8 1051.88  5002.0 1052.38  5009.9 1052.62  5041.5 1058.25  5090.9 1060.88
  5133.3 1062.01  5178.8 1065.88  5397.6 1074.93  5454.1 1078.55  5497.7 1080.75
  5517.8 1083.10  5536.4 1082.55  5688.0 1087.24  5758.1 1090.58  5909.9 1092.43
#Mann=12,-1,0
  3739.5     0.1       0  3852.9    0.05       0  4130.3     0.1       0
  4309.9    0.05       0  4451.6     0.1       0  4892.0    0.05       0
  4996.0   0.035       0  5002.0    0.05       0  5009.9    0.16       0
  5178.8     0.1       0  5454.1    0.16       0  5536.4     0.1       0
Bank Sta=4996,5002
Exp/Cntr=0.3,0.1

Chan Stop Cuts=-1