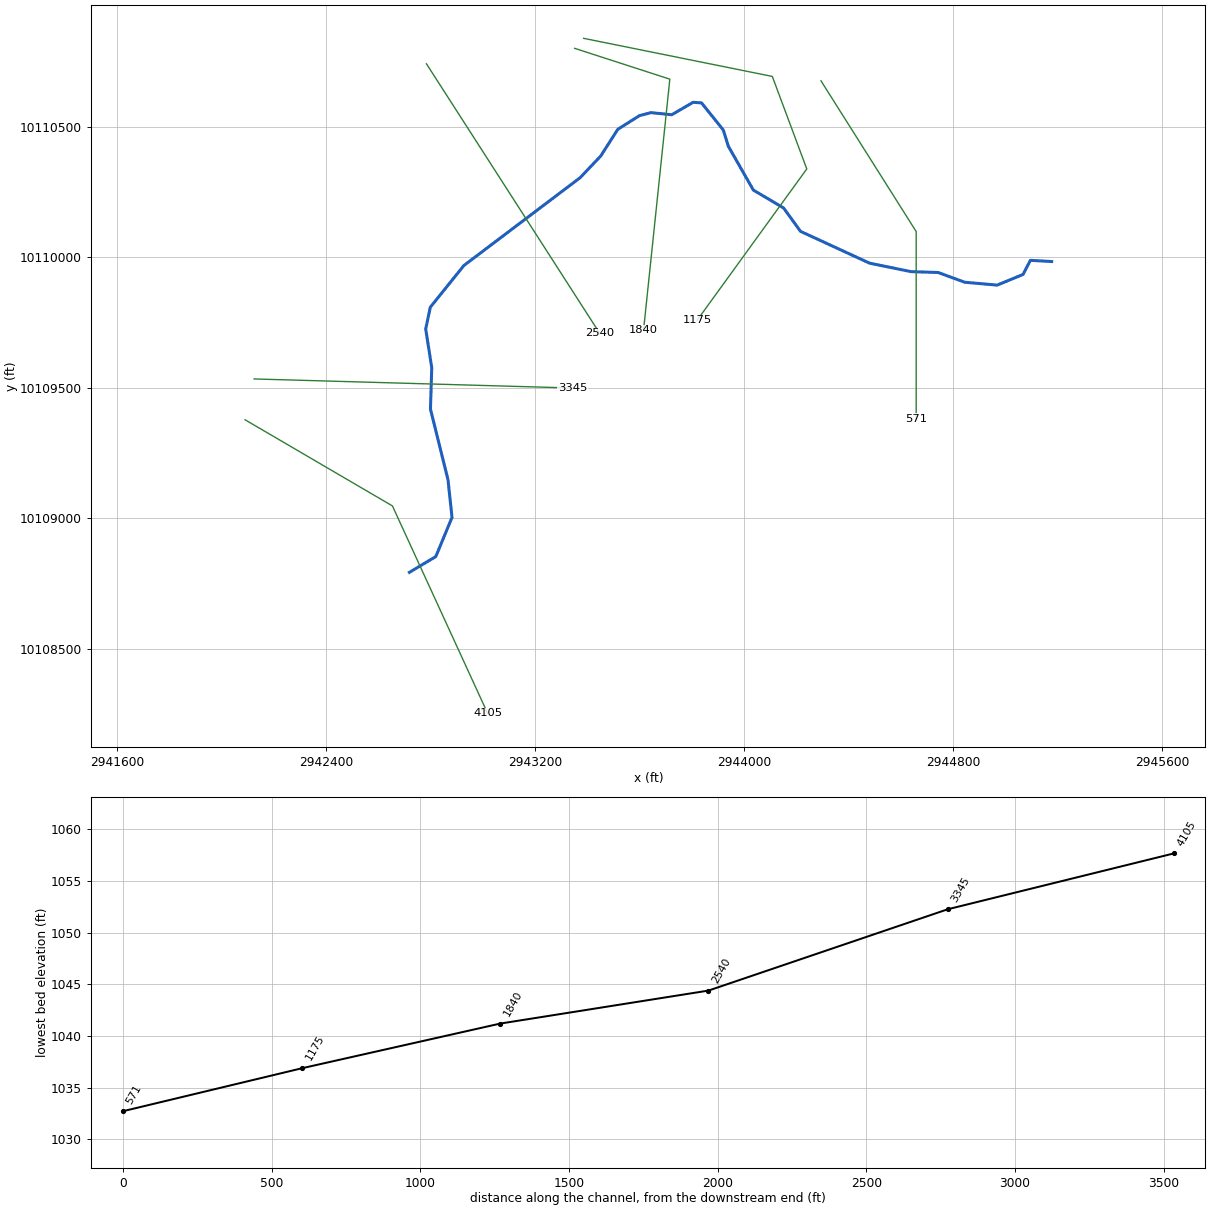
--- UNT 0016 IN LATR.prj (project) ---

Proj Title=UNT 1016 IN LATR Base Level Engineering
Current Plan=p01
Default Exp/Contr=0.3,0.1
English Units
Geom File=g01
Flow File=f01
Plan File=p01
BEGIN DESCRIPTION:
UNT 1016 IN LATR
END DESCRIPTION:

--- UNT 0016 IN LATR.p01 (plan) ---

Plan Title=Multiple Run
Short Identifier=Multiple
Geom File=g01
Flow File=f01
Subcritical Flow
K Sum by GR= 0
Std Step Tol= 0.01
Critical Tol= 0.01
Num of Std Step Trials= 20
Max Error Tol= 0.3
Flow Tol Ratio= 0.001
Split Flow NTrial= 30
Split Flow Tol= 0.02
Split Flow Ratio= 0.02
Log Output Level= 0
Friction Slope Method= 1
Unsteady Friction Slope Method= 2
Unsteady Bridges Friction Slope Method= 1
Parabolic Critical Depth
Global Vel Dist=  1 , 1 , 1
Global Log Level= 0
CheckData=True
Encroach Param= -1, 0, 0, 0
BEGIN DESCRIPTION:
Multiple Run
END DESCRIPTION:

--- UNT 0016 IN LATR.f01 (steady flow) ---

Flow Title=Multiple
Number of Profiles=7
Profile Names=10-year,25-year,50-year,1pct_min,100-year,1pct_plu,500-year
River Rch & RM= UNT 1016 IN LATR,Reach-1,4105
     867    1249    1578    1459    1973    2668    3095
Boundary for River Rch & Prof#=UNT 1016 IN LATR,Reach-1,1
Up Type=0
Dn Type=3
Dn Slope=0.005
Boundary for River Rch & Prof#=UNT 1016 IN LATR,Reach-1,2
Up Type=0
Dn Type=3
Dn Slope=0.005
Boundary for River Rch & Prof#=UNT 1016 IN LATR,Reach-1,3
Up Type=0
Dn Type=3
Dn Slope=0.005
Boundary for River Rch & Prof#=UNT 1016 IN LATR,Reach-1,4
Up Type=0
Dn Type=3
Dn Slope=0.005
Boundary for River Rch & Prof#=UNT 1016 IN LATR,Reach-1,5
Up Type=0
Dn Type=3
Dn Slope=0.005
Boundary for River Rch & Prof#=UNT 1016 IN LATR,Reach-1,6
Up Type=0
Dn Type=3
Dn Slope=0.005
Boundary for River Rch & Prof#=UNT 1016 IN LATR,Reach-1,7
Up Type=0
Dn Type=3
Dn Slope=0.005

--- UNT 0016 IN LATR.g01 (geometry) ---

Geom Title=Existing Conditions

River Reach=UNT 1016 IN LATR,Reach-1
Reach XY= 30
      2942718.47     10108793.73      2942819.57     10108854.20
      2942881.65     10109004.10      2942866.30     10109147.83
      2942799.09     10109419.00      2942804.05     10109577.13
      2942780.88     10109725.57      2942798.54     10109808.73
      2942926.94     10109968.34      2943371.87     10110304.44
      2943450.76     10110387.43      2943516.21     10110489.73
      2943599.16     10110542.15      2943643.47     10110553.81
      2943722.68     10110545.59      2943804.90     10110593.35
      2943836.94     10110591.01      2943920.27     10110487.10
      2943939.54     10110424.86      2944035.26     10110257.29
      2944150.99     10110188.80      2944215.87     10110099.23
      2944480.04     10109977.52      2944638.61     10109945.04
      2944742.82     10109941.70      2944844.53     10109904.43
      2944968.51     10109893.41      2945067.59     10109934.12
      2945095.95     10109988.27      2945177.36     10109983.71

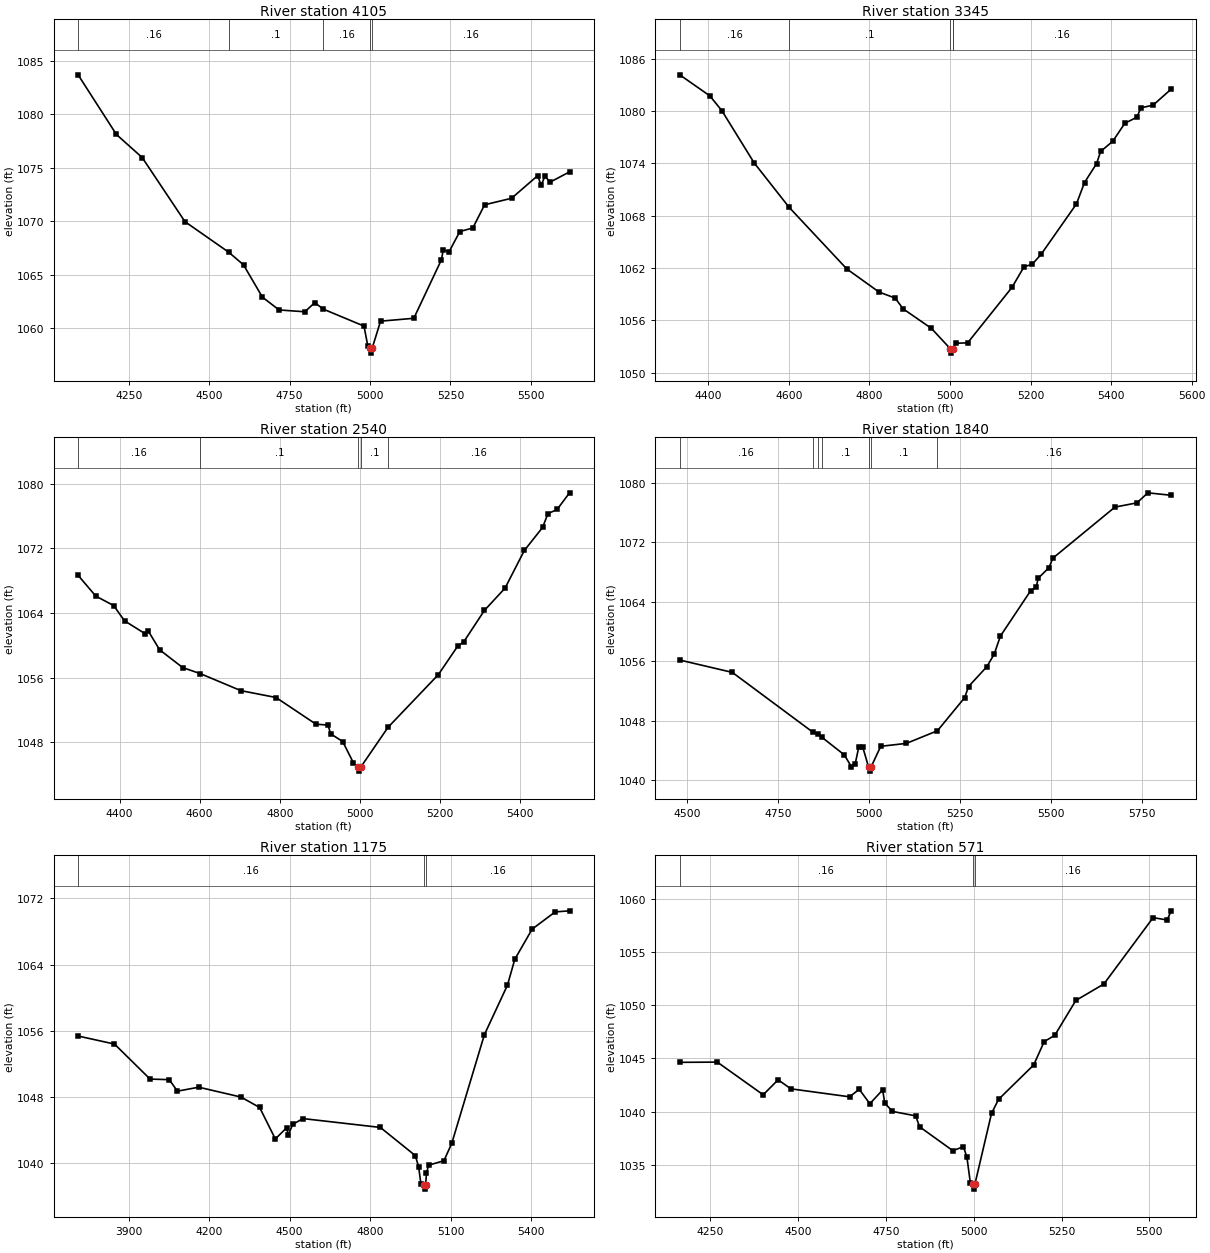
Type RM Length L Ch R = 1,4105,760,760,760
BEGIN DESCRIPTION:
UNT 1016 IN LATR 5.0
END DESCRIPTION:
XS GIS Cut Line= 3
      2942089.24     10109377.94      2942653.49     10109048.07
      2943018.05     10108253.84
#Sta/Elev= 30
  4092.7 1083.70  4211.7 1078.12  4291.9 1075.96  4424.9 1069.96  4560.9 1067.10
  4606.8 1065.92  4665.5 1062.90  4717.3 1061.70  4797.4 1061.53  4828.1 1062.38
  4855.4 1061.77  4981.3 1060.19  4993.1 1058.35  5001.1 1058.16  5003.9 1057.66
  5007.1 1058.16  5032.8 1060.65  5136.2 1060.92  5222.2 1066.41  5227.7 1067.34
  5245.2 1067.11  5279.2 1069.04  5319.6 1069.37  5356.2 1071.54  5440.1 1072.15
  5521.3 1074.27  5532.0 1073.35  5543.3 1074.20  5560.5 1073.67  5620.2 1074.62
#Mann=5,-1,0
  4092.7    0.16       0  4560.9     0.1       0  4855.4    0.16       0
  5001.1    0.07       0  5007.1    0.16       0
Bank Sta=5001.1,5007.1
Exp/Cntr=0.3,0.1

Type RM Length L Ch R = 1,3345,805,805,805
BEGIN DESCRIPTION:
UNT 1016 IN LATR 4.0
END DESCRIPTION:
XS GIS Cut Line= 2
      2942123.98     10109534.18      2943343.48     10109499.46
#Sta/Elev= 30
  4329.1 1084.15  4403.6 1081.75  4433.6 1080.05  4513.7 1074.07  4600.6 1068.97
  4743.8 1061.91  4823.8 1059.26  4863.8 1058.57  4883.8 1057.33  4953.8 1055.10
  5000.9 1052.76  5003.6 1052.26  5006.9 1052.76  5007.0 1052.77  5013.9 1053.39
  5043.9 1053.44  5153.9 1059.79  5183.9 1062.16  5203.9 1062.43  5226.1 1063.57
  5314.0 1069.36  5334.0 1071.81  5364.0 1073.98  5374.0 1075.37  5404.0 1076.53
  5434.0 1078.59  5464.0 1079.30  5474.1 1080.37  5504.1 1080.67  5549.1 1082.51
#Mann=5,-1,0
  4329.1    0.16       0  4600.6     0.1       0  5000.9    0.07       0
  5006.9     0.1       0  5007.0    0.16       0
Bank Sta=5000.9,5006.9
Exp/Cntr=0.3,0.1

Type RM Length L Ch R = 1,2540,700,700,700
BEGIN DESCRIPTION:
UNT 1016 IN LATR 3.0
END DESCRIPTION:
XS GIS Cut Line= 2
      2942783.71     10110740.76      2943447.44     10109708.29
#Sta/Elev= 30
  4296.4 1068.67  4340.4 1066.10  4385.2 1064.92  4412.3 1063.03  4463.8 1061.43
  4471.2 1061.80  4500.1 1059.43  4557.6 1057.23  4601.6 1056.48  4702.9 1054.37
  4790.7 1053.52  4890.5 1050.21  4920.8 1050.10  4926.8 1049.03  4957.2 1048.06
  4984.2 1045.40  4996.4 1044.89  4999.2 1044.39  5002.4 1044.89  5070.4 1049.82
  5196.2 1056.36  5244.5 1059.89  5259.6 1060.42  5311.2 1064.32  5362.7 1067.08
  5410.9 1071.75  5456.5 1074.61  5469.8 1076.31  5492.8 1076.84  5523.8 1078.90
#Mann=5,-1,0
  4296.4    0.16       0  4601.6     0.1       0  4996.4    0.07       0
  5002.4     0.1       0  5070.4    0.16       0
Bank Sta=4996.4,5002.4
Exp/Cntr=0.3,0.1

Type RM Length L Ch R = 1,1840,665,665,665
BEGIN DESCRIPTION:
UNT 1016 IN LATR 2.0
END DESCRIPTION:
XS GIS Cut Line= 3
      2943350.97     10110799.99      2943715.54     10110681.94
      2943614.84     10109720.10
#Sta/Elev= 30
  4479.1 1056.14  4623.6 1054.48  4844.0 1046.47  4858.0 1046.21  4870.1 1045.74
  4930.9 1043.40  4951.0 1041.79  4961.0 1042.13  4971.1 1044.45  4982.2 1044.39
  4998.3 1041.70  5001.0 1041.20  5004.3 1041.70  5031.4 1044.54  5101.8 1044.93
  5187.2 1046.63  5262.0 1051.08  5272.7 1052.58  5323.0 1055.25  5343.1 1056.93
  5360.3 1059.37  5443.7 1065.49  5458.6 1065.91  5463.8 1067.13  5493.9 1068.58
  5504.0 1069.83  5674.9 1076.71  5735.3 1077.28  5765.4 1078.63  5829.4 1078.30
#Mann=7,-1,0
  4479.1    0.16       0  4844.0     0.1       0  4858.0    0.16       0
  4870.1     0.1       0  4998.3    0.07       0  5004.3     0.1       0
  5187.2    0.16       0
Bank Sta=4998.3,5004.3
Exp/Cntr=0.3,0.1

Type RM Length L Ch R = 1,1175,604,604,604
BEGIN DESCRIPTION:
Mapping XS dea84633
END DESCRIPTION:
XS GIS Cut Line= 4
      2943385.66     10110838.20      2944107.90     10110692.36
      2944239.84     10110338.19      2943819.84     10109758.52
#Sta/Elev= 30
  3712.3 1055.38  3847.8 1054.41  3980.4 1050.18  4051.8 1050.11  4082.4 1048.72
  4161.6 1049.20  4319.0 1048.01  4388.5 1046.75  4446.9 1042.95  4489.4 1044.31
  4494.7 1043.40  4511.7 1044.71  4550.0 1045.41  4838.3 1044.34  4968.3 1040.94
  4980.8 1039.59  4989.1 1037.55  5000.8 1037.39  5003.6 1036.89  5006.8 1037.39
  5010.0 1038.80  5017.8 1039.78  5075.0 1040.32  5104.2 1042.42  5225.7 1055.54
  5311.6 1061.52  5338.9 1064.64  5403.6 1068.29  5489.4 1070.37  5542.9 1070.50
#Mann=3,-1,0
  3712.3    0.16       0  5000.8    0.07       0  5006.8    0.16       0
Bank Sta=5000.8,5006.8
Exp/Cntr=0.3,0.1

Type RM Length L Ch R = 1,571,0,0,0
BEGIN DESCRIPTION:
UNT 1016 IN LATR 1.0
END DESCRIPTION:
XS GIS Cut Line= 3
      2944294.10     10110675.70      2944658.70     10110098.42
      2944658.70     10109382.29
#Sta/Elev= 30
  4163.2 1044.63  4270.2 1044.65  4400.8 1041.58  4443.2 1042.99  4479.7 1042.14
  4646.7 1041.39  4674.1 1042.10  4704.4 1040.74  4740.8 1042.04  4746.8 1040.80
  4768.7 1040.02  4835.0 1039.60  4845.8 1038.58  4940.7 1036.33  4970.7 1036.71
  4980.7 1035.72  4990.7 1033.25  4997.7 1033.22  5000.4 1032.72  5003.7 1033.22
  5050.7 1039.83  5070.7 1041.15  5170.7 1044.38  5200.7 1046.58  5230.7 1047.16
  5290.7 1050.44  5370.7 1051.99  5510.7 1058.22  5550.7 1058.00  5562.1 1058.86
#Mann=3,-1,0
  4163.2    0.16       0  4997.7    0.07       0  5003.7    0.16       0
Bank Sta=4997.7,5003.7
Exp/Cntr=0.3,0.1

Chan Stop Cuts=-1