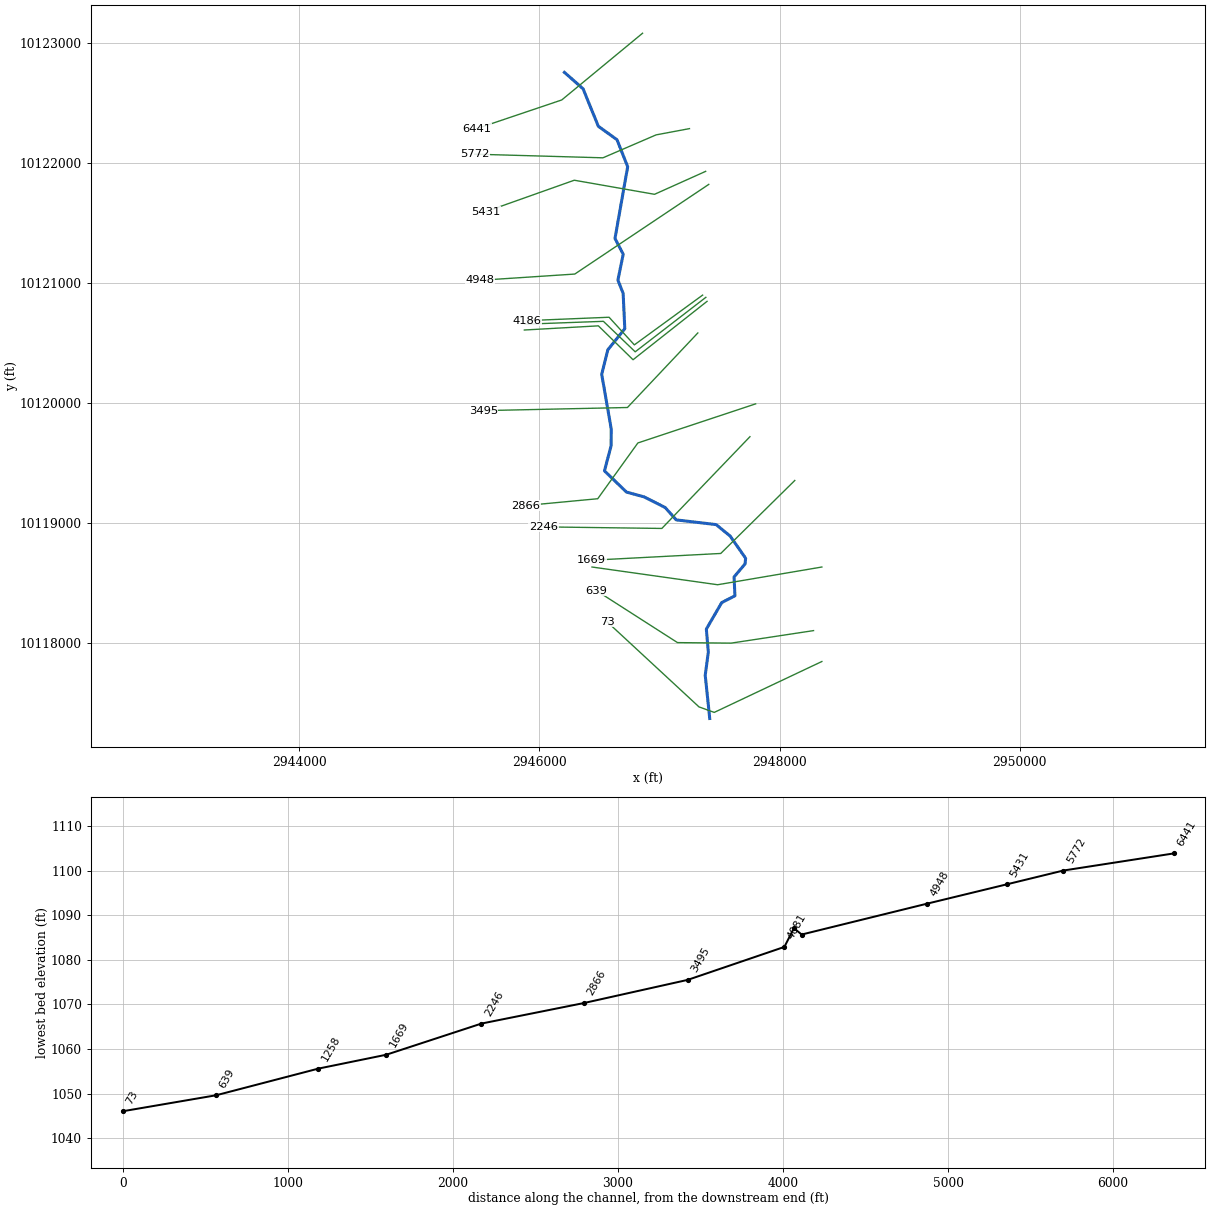
--- UNT 0017 IN LATR.prj (project) ---

Proj Title=UNT 1017 IN LATR Base Level Engineering
Current Plan=p01
Default Exp/Contr=0.3,0.1
English Units
Geom File=g01
Flow File=f01
Plan File=p01
Y Axis Title=Elevation
X Axis Title(PF)=Main Channel Distance
X Axis Title(XS)=Station
BEGIN DESCRIPTION:
UNT 1017 IN LATR
END DESCRIPTION:
DSS Export Rating Curves= 0
DSS Export Rating Curve Sorted= 0
DSS Export Volume Flow Curves= 0
DXF OffsetX= 0
DXF OffsetY= 0
DXF ScaleX= 1
DXF ScaleY= 10

--- UNT 0017 IN LATR.p01 (plan) ---

Plan Title=Multiple Run
Short Identifier=Multiple
Geom File=g01
Flow File=f01
Subcritical Flow
K Sum by GR= 0
Std Step Tol= 0.01
Critical Tol= 0.01
Num of Std Step Trials= 20
Max Error Tol= 0.3
Flow Tol Ratio= 0.001
Split Flow NTrial= 30
Split Flow Tol= 0.02
Split Flow Ratio= 0.02
Log Output Level= 0
Friction Slope Method= 1
Unsteady Friction Slope Method= 2
Unsteady Bridges Friction Slope Method= 1
Parabolic Critical Depth
Global Vel Dist=  1 , 1 , 1
Global Log Level= 0
CheckData=True
Encroach Param= -1, 0, 0, 0
BEGIN DESCRIPTION:
Multiple Run
END DESCRIPTION:

--- UNT 0017 IN LATR.f01 (steady flow) ---

Flow Title=Multiple
Program Version=4.10
Number of Profiles= 7
Profile Names=10-year,25-year,50-year,1pct_min,100-year,1pct_plu,500-year
River Rch & RM=UNT 1017 IN LATR,Reach-1         ,6441
    1153    1695    2172    2035    2752    3722    4438
Boundary for River Rch & Prof#=UNT 1017 IN LATR,Reach-1         , 1
Up Type= 0
Dn Type= 3
Dn Slope=0.006
Boundary for River Rch & Prof#=UNT 1017 IN LATR,Reach-1         , 2
Up Type= 0
Dn Type= 3
Dn Slope=0.006
Boundary for River Rch & Prof#=UNT 1017 IN LATR,Reach-1         , 3
Up Type= 0
Dn Type= 3
Dn Slope=0.006
Boundary for River Rch & Prof#=UNT 1017 IN LATR,Reach-1         , 4
Up Type= 0
Dn Type= 3
Dn Slope=0.006
Boundary for River Rch & Prof#=UNT 1017 IN LATR,Reach-1         , 5
Up Type= 0
Dn Type= 3
Dn Slope=0.006
Boundary for River Rch & Prof#=UNT 1017 IN LATR,Reach-1         , 6
Up Type= 0
Dn Type= 3
Dn Slope=0.006
Boundary for River Rch & Prof#=UNT 1017 IN LATR,Reach-1         , 7
Up Type= 0
Dn Type= 3
Dn Slope=0.006
DSS Import GetInterval= 0
DSS Import GetPeak= 0
DSS Import FillOption= 0

--- UNT 0017 IN LATR.g01 (geometry) ---

Geom Title=Existing Conditions
Program Version=4.10

River Reach=UNT 1017 IN LATR,Reach-1
Reach XY= 30
      2946208.47     10122753.73      2946363.93     10122616.57
      2946490.87     10122304.66      2946646.25     10122192.89
      2946735.33       10121968.      2946629.69     10121370.67
      2946698.06     10121239.22      2946653.98     10121023.67
      2946697.48     10120913.54      2946711.29     10120619.02
      2946570.04     10120443.37      2946519.12      10120239.5
      2946598.48     10119783.73      2946597.33      10119644.2
      2946541.96     10119435.21      2946725.57     10119258.82
       2946871.3      10119219.2      2947047.23     10119130.46
      2947139.76      10119027.2      2947470.99      10118988.2
      2947587.83     10118893.57      2947717.35     10118707.87
      2947713.15     10118661.24      2947621.13     10118552.51
       2947628.3     10118395.02      2947518.42     10118338.93
      2947390.28      10118118.2      2947406.81     10117926.66
      2947380.96     10117733.77      2947418.47     10117373.73

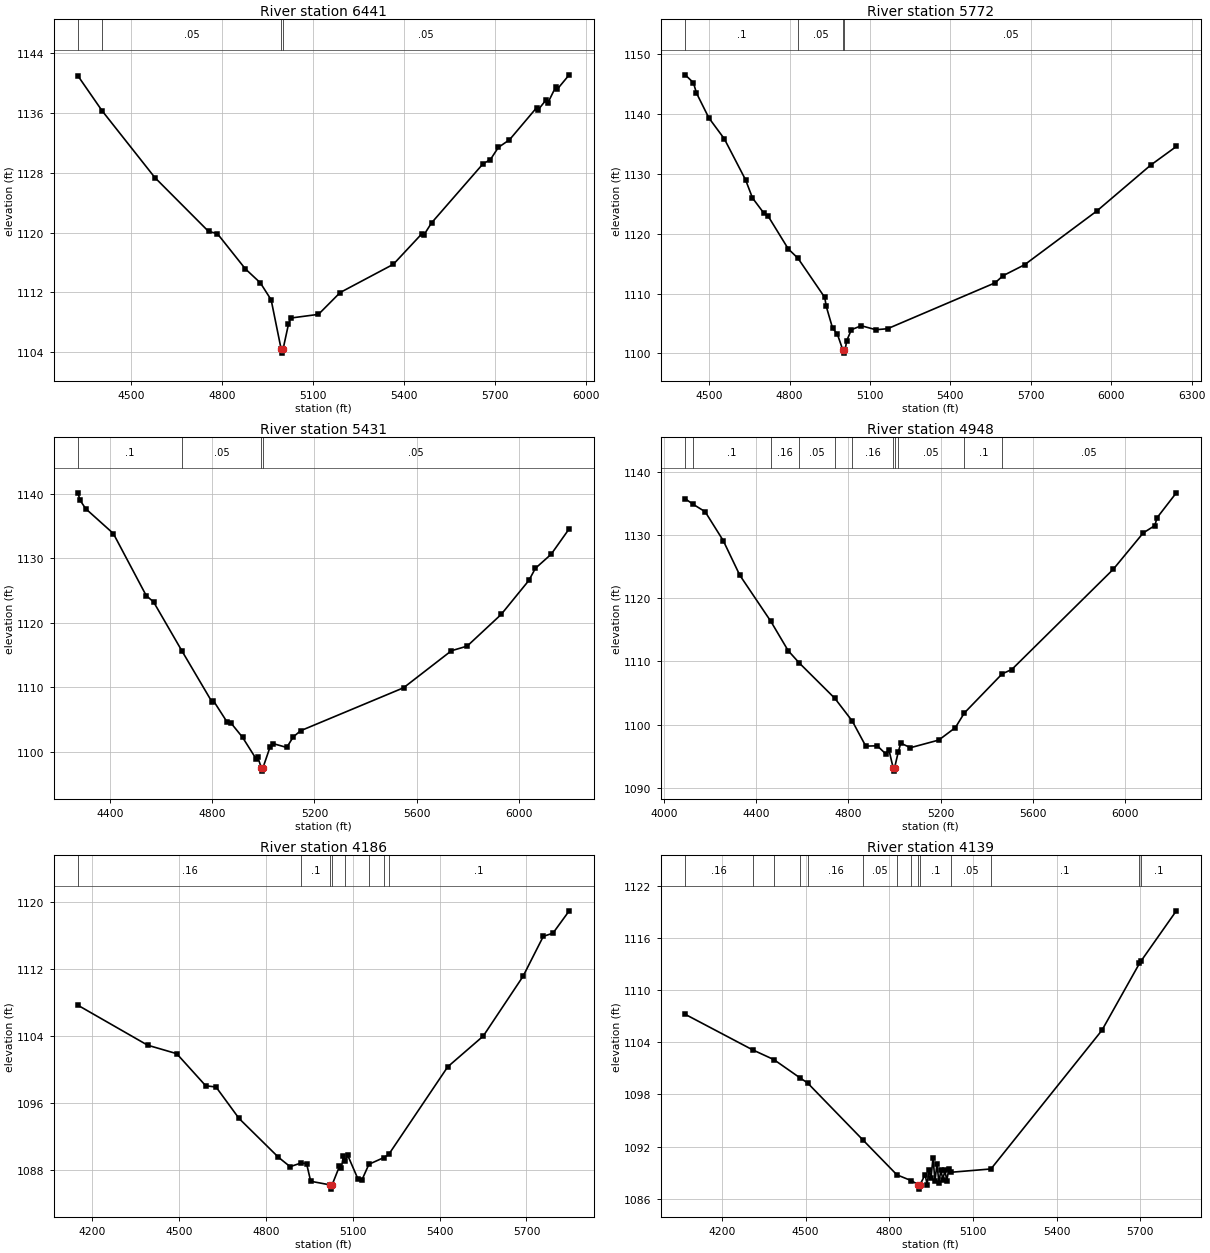
Type RM Length L Ch R = 1 ,6441    ,669,669,669
BEGIN DESCRIPTION:
UNT 1017 IN LATR 14.0
END DESCRIPTION:
XS GIS Cut Line= 3
      2946859.24     10123079.35      2946186.48     10122523.78
      2945478.97     10122285.05
#Sta/Elev= 30
  4326.1 1140.91  4405.3 1136.27  4579.2 1127.35  4756.3 1120.15    4785 1119.87
  4877.5 1115.15    4927 1113.28  4962.6 1111.01  4995.7 1104.39  4998.4 1103.89
  5001.7 1104.39  5019.5 1107.72  5027.4 1108.58  5118.5 1109.07  5190.2 1111.99
  5365.4 1115.76  5459.9 1119.86  5465.1 1119.61  5491.3 1121.29  5660.9 1129.18
  5685.4 1129.75  5711.6 1131.38  5748.4  1132.4  5837.5 1136.67  5842.8 1136.41
    5869 1137.72  5874.2 1137.28  5900.4 1139.43  5905.7 1139.15  5945.3 1141.08
#Mann= 4 ,-1 , 0
  4326.1      .1       0  4405.3     .05       0  4995.7    .035       0
  5001.7     .05       0
Bank Sta=4995.7,5001.7
XS Rating Curve= 0 ,0
Exp/Cntr=0.3,0.1

Type RM Length L Ch R = 1 ,5772    ,341,341,341
BEGIN DESCRIPTION:
UNT 1017 IN LATR 13.0
END DESCRIPTION:
XS GIS Cut Line= 4
      2947249.83     10122285.06      2946972.07     10122232.98
      2946529.36     10122042.01      2945462.53     10122072.37
#Sta/Elev= 30
  4410.9 1146.58  4441.5 1145.26    4453 1143.53  4499.1 1139.38  4556.8 1135.88
  4636.1 1129.02  4661.9 1125.99  4703.5  1123.5  4719.2 1123.03  4795.4 1117.47
  4831.4 1115.92  4931.5 1109.36    4937 1107.87  4960.5 1104.25  4978.5 1103.22
  4999.1 1100.55  5001.8 1100.05  5005.1 1100.55  5007.5  1100.6  5013.3 1102.13
    5031 1103.97  5067.7 1104.63  5122.2 1103.96  5165.7 1104.13  5566.7  1111.8
  5596.7    1113  5676.7 1114.82  5946.8 1123.83  6146.9 1131.47  6242.9  1134.6
#Mann= 4 ,-1 , 0
  4410.9      .1       0  4831.4     .05       0  4999.1    .035       0
  5005.1     .05       0
Bank Sta=4999.1,5005.1
XS Rating Curve= 0 ,0
Exp/Cntr=0.3,0.1

Type RM Length L Ch R = 1 ,5431    ,483,483,483
BEGIN DESCRIPTION:
UNT 1017 IN LATR 12.0
END DESCRIPTION:
XS GIS Cut Line= 4
       2947384.4     10121929.16      2946959.05     10121738.19
      2946290.64     10121855.38      2945557.15     10121594.97
#Sta/Elev= 30
  4274.7 1140.11  4281.2 1139.03  4304.4 1137.65  4412.7  1133.8  4541.6 1124.17
  4570.2  1123.2  4680.9 1115.63  4799.7 1107.65  4804.8 1107.87  4859.1 1104.52
  4873.5 1104.42  4918.5 1102.22  4972.8 1098.81  4977.9 1099.17  4992.4 1097.47
  4995.1 1096.97  4998.4 1097.47  5025.8 1100.64  5037.3 1101.25  5091.7 1100.64
  5117.2 1102.27    5146 1103.23  5549.2 1109.89  5736.6 1115.63  5798.3 1116.35
  5931.2 1121.25  6039.9 1126.53  6065.5 1128.41  6127.2 1130.59  6197.9 1134.54
#Mann= 4 ,-1 , 0
  4274.7      .1       0  4680.9     .05       0  4992.4    .035       0
  4998.4     .05       0
Bank Sta=4992.4,4998.4
XS Rating Curve= 0 ,0
Exp/Cntr=0.3,0.1

Type RM Length L Ch R = 1 ,4948    ,762,762,762
BEGIN DESCRIPTION:
UNT 1017 IN LATR 11.0
END DESCRIPTION:
XS GIS Cut Line= 3
      2947410.43     10121820.65      2946294.98     10121074.13
      2945505.01     10121022.04
#Sta/Elev= 30
  4090.6 1135.76  4123.9 1134.91  4177.2 1133.71  4255.6 1129.15  4327.7 1123.66
  4462.8 1116.34  4537.9 1111.71  4585.8 1109.77  4740.7 1104.16  4816.7 1100.55
  4875.1 1096.59  4925.2 1096.64  4961.2 1095.38  4976.2 1095.93  4994.2 1093.13
    4997 1092.63  5000.2 1093.13    5016 1095.61  5027.2 1097.06  5069.3 1096.34
  5192.4 1097.55  5264.4 1099.52  5303.7 1101.85  5467.9 1108.04  5509.5 1108.72
  5950.4 1124.59  6080.7 1130.35  6130.8 1131.51  6140.9 1132.76  6224.5  1136.7
#Mann= 11 ,-1 , 0
  4090.6     .05       0  4123.9      .1       0  4462.8     .16       0
  4585.8     .05       0  4740.7      .1       0  4816.7     .16       0
  4994.2     .07       0  5000.2     .16       0    5016     .05       0
  5303.7      .1       0  5467.9     .05       0
Bank Sta=4994.2,5000.2
XS Rating Curve= 0 ,0
Exp/Cntr=0.3,0.1

Type RM Length L Ch R = 1 ,4186    ,47,47,47
BEGIN DESCRIPTION:
UNT 1017 IN LATR 9.0
END DESCRIPTION:
XS GIS Cut Line= 4
      2947359.46     10120899.02      2946790.87     10120484.52
      2946580.37     10120714.55      2945898.91     10120686.34
#Sta/Elev= 30
  4150.3 1107.63  4390.7 1102.87  4491.1 1101.86  4591.5 1098.02    4627 1097.88
  4706.6 1094.12  4842.6 1089.49  4883.2 1088.36  4920.6  1088.8    4940 1088.73
  4954.2 1086.62  5022.1 1086.18  5024.8 1085.68  5028.1 1086.18  5053.5 1088.39
  5060.2 1088.22  5067.6 1089.69    5074 1089.06  5081.8 1089.75    5117 1086.94
  5131.1 1086.76  5155.5 1088.65  5206.7 1089.44  5223.9 1089.82  5427.9 1100.29
  5550.6 1103.96  5688.1 1111.09  5758.2 1115.87  5791.6 1116.25  5847.8 1118.92
#Mann= 8 ,-1 , 0
  4150.3     .16       0  4920.6      .1       0  5022.1     .07       0
  5028.1      .1       0    5074     .05       0  5155.5      .1       0
  5206.7     .05       0  5223.9      .1       0
Bank Sta=5022.1,5028.1
XS Rating Curve= 0 ,0
Exp/Cntr=0.3,0.1

Type RM Length L Ch R = 1 ,4139    ,58,58,58
BEGIN DESCRIPTION:
Mapping XS 13764826
END DESCRIPTION:
XS GIS Cut Line= 4
       2947386.1     10120880.23      2946797.99     10120426.67
      2946533.23     10120680.58      2945881.79     10120656.77
#Sta/Elev= 30
  4068.2  1107.2  4309.7 1103.12  4386.4 1101.99  4480.1 1099.89    4507 1099.31
  4707.2  1092.7  4827.6 1088.74  4879.6 1088.07  4904.3  1087.6  4907.1  1087.1
  4910.3  1087.6  4928.7 1088.77  4935.7 1087.63  4942.9  1089.3  4949.8 1088.35
    4957 1090.73    4964 1088.02  4971.2 1090.02  4978.1 1087.84  4985.3 1089.32
  4992.3 1088.15  4999.5 1089.28  5006.4 1088.09  5013.6 1089.37  5022.2 1089.04
  5164.8 1089.42  5562.7 1105.36  5697.3 1113.05  5703.1 1113.33  5829.6  1119.1
#Mann= 14 ,-1 , 0
  4068.2     .16       0  4309.7      .1       0  4386.4     .16       0
  4480.1      .1       0    4507     .16       0  4707.2     .05       0
  4827.6     .16       0  4879.6      .1       0  4904.3     .07       0
  4910.3      .1       0  5022.2     .05       0  5164.8      .1       0
  5697.3     .16       0  5703.1      .1       0
Bank Sta=4904.3,4910.3
XS Rating Curve= 0 ,0
Exp/Cntr=0.3,0.1

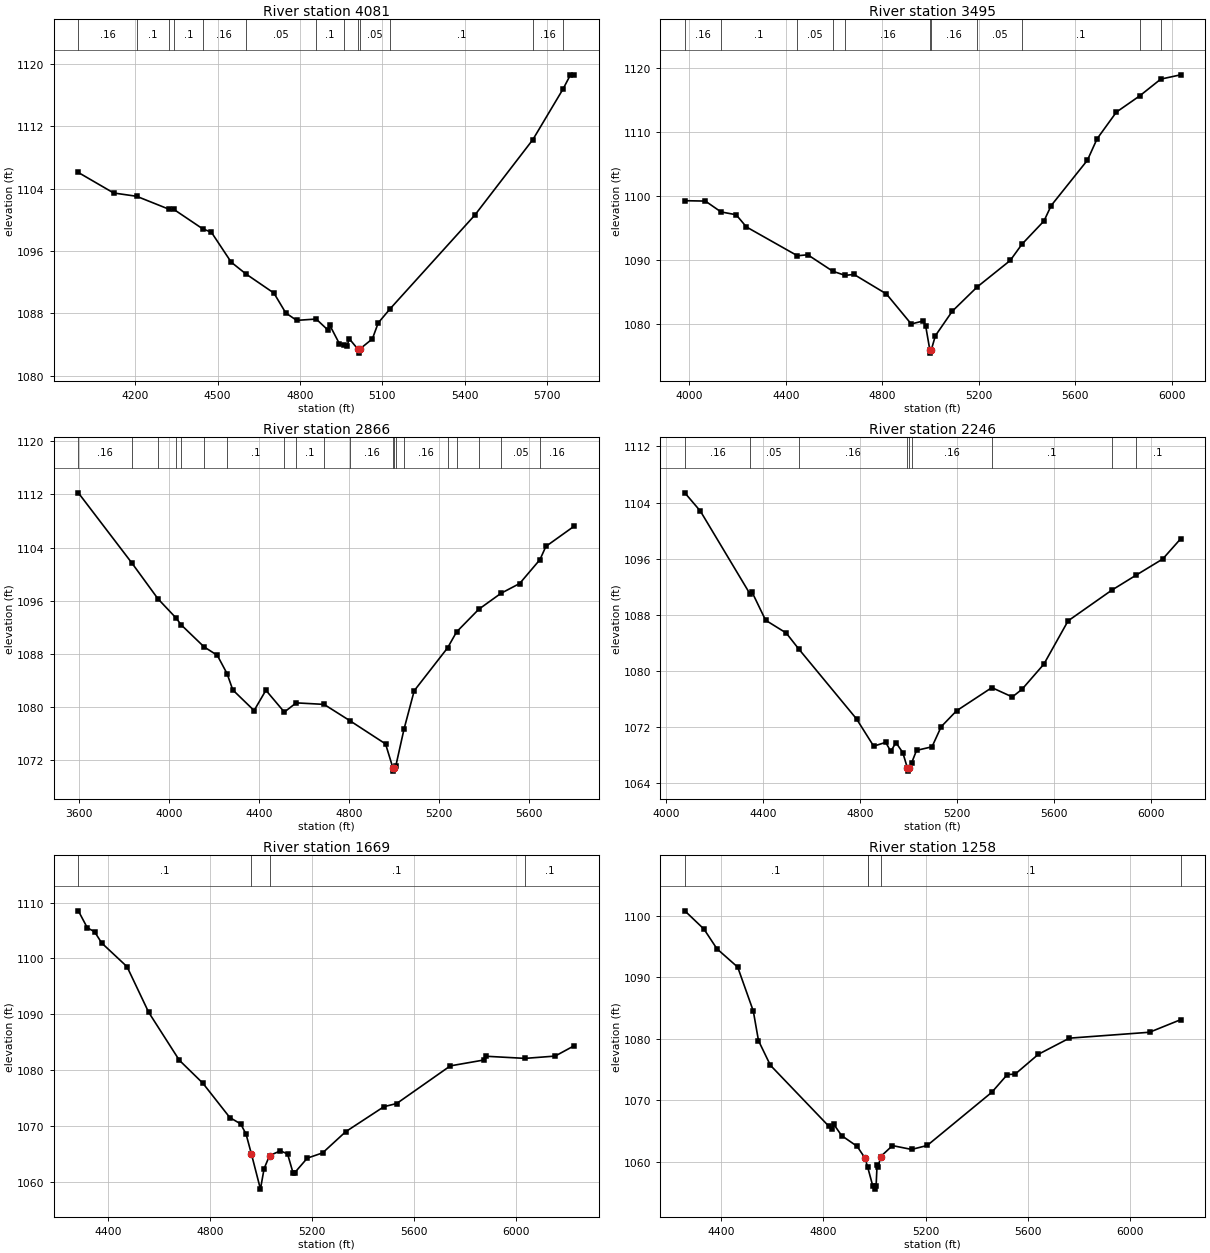
Type RM Length L Ch R = 1 ,4081    ,586,586,586
BEGIN DESCRIPTION:
Mapping XS 88ed9927
END DESCRIPTION:
XS GIS Cut Line= 4
      2947396.35     10120846.94      2946780.02     10120360.82
      2946491.39     10120642.94      2945875.04     10120608.21
#Sta/Elev= 30
  3992.8 1106.06  4121.5 1103.43    4205 1103.01  4324.3 1101.33  4340.9 1101.32
    4446 1098.83  4477.4  1098.4  4549.6 1094.56  4602.9 1093.06  4705.1  1090.6
  4748.4 1088.05    4788  1087.1  4859.2 1087.27  4901.2 1085.88  4908.2 1086.51
  4943.6 1084.11  4960.9 1083.95  4971.9 1083.79  4978.9 1084.77  5011.3  1083.4
  5014.1  1082.9  5017.3  1083.4  5063.8 1084.73  5085.1 1086.78  5128.8  1088.6
  5436.8 1100.59  5648.4 1110.28  5758.2 1116.76  5784.9 1118.56  5798.7 1118.58
#Mann= 13 ,-1 , 0
  3992.8     .16       0    4205      .1       0  4324.3     .16       0
  4340.9      .1       0    4446     .16       0  4602.9     .05       0
  4859.2      .1       0  4960.9     .05       0  5011.3    .035       0
  5017.3     .05       0  5128.8      .1       0  5648.4     .16       0
  5758.2      .1       0
Bank Sta=5011.3,5017.3
XS Rating Curve= 0 ,0
Exp/Cntr=0.3,0.1

Type RM Length L Ch R = 1 ,3495    ,629,629,629
BEGIN DESCRIPTION:
UNT 1017 IN LATR 8.0
END DESCRIPTION:
XS GIS Cut Line= 3
      2947319.31     10120583.69      2946733.35     10119963.02
       2945532.3       10119937.
#Sta/Elev= 30
  3981.2 1099.26  4066.5  1099.2  4131.3 1097.51    4194 1097.07  4236.5 1095.17
  4447.9 1090.68  4490.9 1090.83  4594.6 1088.26  4645.9 1087.62  4682.3 1087.77
  4816.6 1084.73  4919.7 1080.04  4969.7 1080.52  4979.7 1079.69  4996.7    1076
  4999.4  1075.5  5002.7    1076  5019.7 1078.21  5089.7 1082.03  5192.5  1085.8
  5329.8 1089.94  5378.8 1092.49  5469.8  1096.1  5499.8 1098.51  5649.8 1105.57
  5689.9 1108.91  5769.9 1113.07  5866.2 1115.59  5953.8 1118.21  6036.1 1118.88
#Mann= 11 ,-1 , 0
  3981.2     .16       0  4131.3      .1       0  4447.9     .05       0
  4594.6      .1       0  4645.9     .16       0  4996.7     .07       0
  5002.7     .16       0  5192.5     .05       0  5378.8      .1       0
  5866.2     .16       0  5953.8      .1       0
Bank Sta=4996.7,5002.7
XS Rating Curve= 0 ,0
Exp/Cntr=0.3,0.1

Type RM Length L Ch R = 1 ,2866    ,620,620,620
BEGIN DESCRIPTION:
UNT 1017 IN LATR 7.0
END DESCRIPTION:
XS GIS Cut Line= 4
      2947801.04     10119993.39      2946820.16     10119667.88
      2946485.96     10119203.47      2945886.95     10119147.04
#Sta/Elev= 30
  3595.2 1112.25  3832.9  1101.7  3949.8 1096.27  4031.4 1093.34  4052.4 1092.37
  4154.9 1089.03  4213.8 1087.76  4257.4 1084.99  4282.8 1082.54  4377.6 1079.43
  4430.2 1082.49  4512.2  1079.2  4565.1 1080.59  4689.2 1080.36  4806.8 1077.84
  4962.9  1074.4  4995.5  1070.8  4998.2  1070.3  5001.5  1070.8  5008.3 1071.04
  5044.8 1076.59  5090.5 1082.42    5239 1088.88  5279.2 1091.29  5377.9  1094.7
  5476.6  1097.1  5559.9 1098.58  5650.2 1102.18  5676.6 1104.17  5802.5 1107.22
#Mann= 20 ,-1 , 0
  3595.2     .16       0  3832.9     .05       0  3949.8     .16       0
  4031.4     .05       0  4052.4     .16       0  4154.9     .05       0
  4257.4      .1       0  4512.2     .16       0  4565.1      .1       0
  4689.2     .16       0  4806.8     .16       0  4995.5     .07       0
  5001.5     .16       0  5008.3      .1       0  5044.8     .16       0
    5239      .1       0  5279.2     .05       0  5377.9     .16       0
  5476.6     .05       0  5650.2     .16       0
Bank Sta=4995.5,5001.5
XS Rating Curve= 0 ,0
Exp/Cntr=0.3,0.1

Type RM Length L Ch R = 1 ,2246    ,577,577,577
BEGIN DESCRIPTION:
UNT 1017 IN LATR 5.0
END DESCRIPTION:
XS GIS Cut Line= 3
      2947753.33     10119719.97      2947019.81     10118956.07
      2946034.55     10118969.09
#Sta/Elev= 30
  4076.9 1105.39  4141.2 1102.78  4346.1 1090.95  4353.5 1091.28  4410.1 1087.22
    4495  1085.4  4545.8 1083.16  4784.9 1073.15  4855.7 1069.26  4905.1  1069.8
  4926.4 1068.52  4947.5 1069.77  4975.8 1068.34  4994.2  1066.2  4996.9  1065.7
  5000.2  1066.2  5012.6 1066.91  5032.4 1068.66  5096.2 1069.17  5134.1 1072.04
  5197.3  1074.3  5342.9 1077.61  5427.3 1076.28  5467.3 1077.37  5557.3 1080.95
  5657.3 1087.13  5836.7 1091.49  5935.5  1093.6  6047.4 1095.95  6121.3 1098.83
#Mann= 9 ,-1 , 0
  4076.9     .16       0  4346.1     .05       0  4545.8     .16       0
  4994.2     .07       0  5000.2     .16       0  5012.6     .16       0
  5342.9      .1       0  5836.7     .05       0  5935.5      .1       0
Bank Sta=4994.2,5000.2
XS Rating Curve= 0 ,0
Exp/Cntr=0.3,0.1

Type RM Length L Ch R = 1 ,1669    ,411,411,411
BEGIN DESCRIPTION:
UNT 1017 IN LATR 4.0
END DESCRIPTION:
XS GIS Cut Line= 3
      2948126.61     10119355.41      2947510.26     10118747.74
      2946433.87     10118691.32
#Sta/Elev= 30
  4284.9 1108.53  4320.1 1105.49  4348.4 1104.79  4376.7 1102.76  4475.7 1098.53
  4560.6 1090.36  4680.7 1081.78  4772.7 1077.68  4878.8 1071.51  4921.2 1070.38
  4942.3 1068.55  4963.6 1064.94  4998.7  1058.7  5013.1 1062.38  5034.3  1064.7
  5076.8 1065.56    5105    1065  5126.2 1061.65  5133.3 1061.66  5182.3 1064.25
  5242.4 1065.19  5332.5 1068.97  5482.7 1073.46  5532.8 1074.03    5743 1080.77
  5873.2 1081.81  5883.2 1082.49  6035.5 1082.11  6153.6 1082.52  6228.3 1084.37
#Mann= 4 ,-1 , 0
  4284.9      .1       0  4963.6     .05       0  5034.3      .1       0
  6035.5      .1       0
Bank Sta=4963.6,5034.3
XS Rating Curve= 0 ,0
Exp/Cntr=0.3,0.1

Type RM Length L Ch R = 1 ,1258    ,619,619,619
BEGIN DESCRIPTION:
UNT 1017 IN LATR 3.0
END DESCRIPTION:
XS GIS Cut Line= 3
      2948352.26     10118634.89      2947484.22     10118487.32
      2946438.17      10118634.9
#Sta/Elev= 30
  4259.2 1100.81  4334.1 1097.84  4384.8 1094.64  4465.9 1091.66  4526.8 1084.52
  4547.1 1079.71  4593.5 1075.72  4820.9 1065.85  4834.6 1065.37  4841.2 1066.13
  4871.7 1064.29  4932.5 1062.54  4962.9 1060.65  4973.1 1059.24  4993.4 1056.12
  5003.3 1055.59  5006.5 1056.09  5010.3 1059.51  5015.3 1059.23  5023.8 1060.86
  5070.5 1062.66  5145.1 1062.04  5206.1 1062.68  5458.6 1071.33  5519.2 1074.21
  5549.5 1074.27  5640.4  1077.5  5761.5 1080.12  6074.6 1081.08  6196.1 1083.12
#Mann= 5 ,-1 , 0
  4259.2      .1       0  4973.1     .16       0  4973.1     .05       0
  5023.8      .1       0  6196.1      .1       0
Bank Sta=4962.9,5023.8
XS Rating Curve= 0 ,0
Exp/Cntr=0.3,0.1

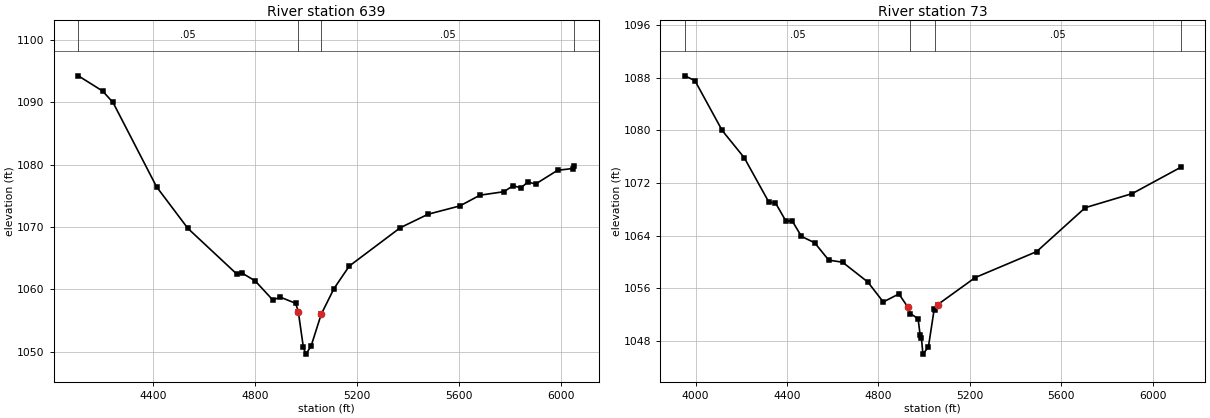
Type RM Length L Ch R = 1 ,639     ,566,566,566
BEGIN DESCRIPTION:
UNT 1017 IN LATR 2.0
END DESCRIPTION:
XS GIS Cut Line= 4
      2948282.88     10118105.39      2947597.07     10118001.21
      2947150.02     10118005.55      2946473.86     10118438.99
#Sta/Elev= 30
  4107.2 1094.28  4202.7 1091.83  4243.2    1090    4414 1076.46  4536.5  1069.8
  4728.7 1062.45  4747.3 1062.67  4800.9 1061.35  4869.5  1058.3  4899.5 1058.75
  4959.5 1057.76  4969.5 1056.45  4989.5 1050.68  4999.2 1049.61  5019.5 1050.87
  5059.5 1056.02  5109.5 1060.13  5169.5 1063.75  5369.8 1069.91  5478.8 1072.07
  5603.1  1073.4  5681.7 1075.12  5775.5 1075.68  5811.9 1076.65  5842.3 1076.28
  5869.4 1077.24  5899.8 1076.91  5986.2 1079.12  6045.2  1079.4  6051.1 1079.88
#Mann= 4 ,-1 , 0
  4107.2     .05       0  4969.5    .035       0  5059.5     .05       0
  6051.1      .1       0
Bank Sta=4969.5,5059.5
XS Rating Curve= 0 ,0
Exp/Cntr=0.3,0.1

Type RM Length L Ch R = 1 ,73      ,0,0,0
BEGIN DESCRIPTION:
UNT 1017 IN LATR 1.0
END DESCRIPTION:
XS GIS Cut Line= 4
      2948352.39     10117848.21      2947456.07     10117424.35
      2947329.18     10117470.25      2946563.79     10118179.04
#Sta/Elev= 30
    3953 1088.28  3997.3 1087.55  4116.6 1079.98  4213.2 1075.84  4321.4 1069.06
  4349.7 1068.99  4395.3 1066.23  4423.5 1066.22  4463.5  1063.9  4521.5 1062.92
  4582.8 1060.29  4643.2 1059.98  4753.8 1056.97  4821.5 1053.94  4889.8 1055.16
  4929.7 1053.12  4940.4 1052.18  4973.8  1051.4    4983 1048.87  4988.3 1048.52
  4994.9 1046.02  5018.9  1047.1  5044.3 1052.84  5049.6 1052.67  5058.9 1053.52
  5223.9 1057.65  5492.7 1061.59  5705.3 1068.26  5910.5 1070.39  6122.6 1074.38
#Mann= 4 ,-1 , 0
    3953     .05       0  4940.4    .035       0  5049.6     .05       0
  6122.6      .1       0
Bank Sta=4929.7,5058.9
XS Rating Curve= 0 ,0
Exp/Cntr=0.3,0.1

Chan Stop Cuts=-1
Use User Specified Reach Order=0
Composite Channel Slope=5