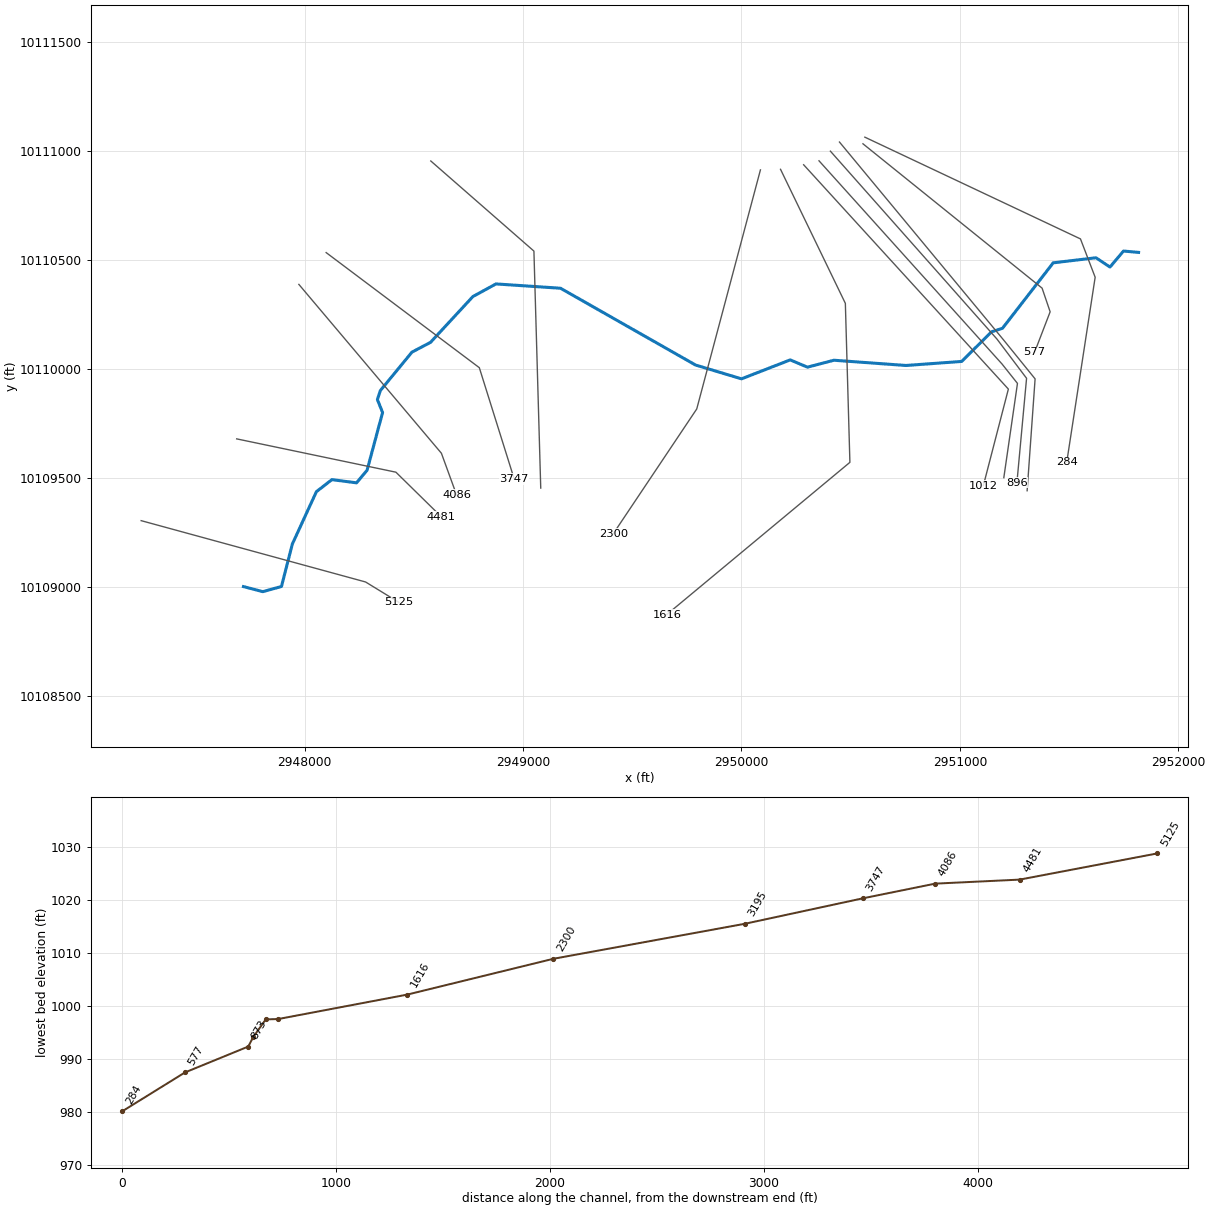
--- UNT 0019 IN LATR.prj (project) ---

Proj Title=UNT 1019 IN LATR Base Level Engineering
Current Plan=p01
Default Exp/Contr=0.3,0.1
English Units
Geom File=g01
Flow File=f01
Plan File=p01
BEGIN DESCRIPTION:
UNT 1019 IN LATR
END DESCRIPTION:

--- UNT 0019 IN LATR.p01 (plan) ---

Plan Title=Multiple Run
Short Identifier=Multiple
Geom File=g01
Flow File=f01
Subcritical Flow
K Sum by GR= 0
Std Step Tol= 0.01
Critical Tol= 0.01
Num of Std Step Trials= 20
Max Error Tol= 0.3
Flow Tol Ratio= 0.001
Split Flow NTrial= 30
Split Flow Tol= 0.02
Split Flow Ratio= 0.02
Log Output Level= 0
Friction Slope Method= 1
Unsteady Friction Slope Method= 2
Unsteady Bridges Friction Slope Method= 1
Parabolic Critical Depth
Global Vel Dist=  1 , 1 , 1
Global Log Level= 0
CheckData=True
Encroach Param= -1, 0, 0, 0
BEGIN DESCRIPTION:
Multiple Run
END DESCRIPTION:

--- UNT 0019 IN LATR.f01 (steady flow) ---

Flow Title=Multiple
Number of Profiles=7
Profile Names=10-year,25-year,50-year,1pct_min,100-year,1pct_plu,500-year
River Rch & RM= UNT 1019 IN LATR,Reach-1,5125
     844    1209    1522    1402    1897    2565    2954
Boundary for River Rch & Prof#=UNT 1019 IN LATR,Reach-1,1
Up Type=0
Dn Type=3
Dn Slope=0.005
Boundary for River Rch & Prof#=UNT 1019 IN LATR,Reach-1,2
Up Type=0
Dn Type=3
Dn Slope=0.005
Boundary for River Rch & Prof#=UNT 1019 IN LATR,Reach-1,3
Up Type=0
Dn Type=3
Dn Slope=0.005
Boundary for River Rch & Prof#=UNT 1019 IN LATR,Reach-1,4
Up Type=0
Dn Type=3
Dn Slope=0.005
Boundary for River Rch & Prof#=UNT 1019 IN LATR,Reach-1,5
Up Type=0
Dn Type=3
Dn Slope=0.005
Boundary for River Rch & Prof#=UNT 1019 IN LATR,Reach-1,6
Up Type=0
Dn Type=3
Dn Slope=0.005
Boundary for River Rch & Prof#=UNT 1019 IN LATR,Reach-1,7
Up Type=0
Dn Type=3
Dn Slope=0.005

--- UNT 0019 IN LATR.g01 (geometry) ---

Geom Title=Existing Conditions

River Reach=UNT 1019 IN LATR,Reach-1
Reach XY= 30
      2947719.38     10109001.24      2947807.90     10108978.00
      2947893.36     10109001.69      2947943.22     10109196.48
      2948053.28     10109436.36      2948124.39     10109491.72
      2948237.12     10109477.01      2948285.42     10109534.83
      2948356.49     10109799.57      2948332.63     10109859.09
      2948346.31     10109900.21      2948490.99     10110076.42
      2948575.79     10110121.08      2948770.00     10110331.27
      2948875.70     10110389.14      2949171.28     10110369.38
      2949789.81     10110017.18      2950000.11     10109953.87
      2950223.29     10110040.80      2950301.97     10110007.42
      2950423.25     10110039.20      2950753.47     10110015.17
      2951008.47     10110033.73      2951144.75     10110169.32
      2951195.49     10110186.02      2951427.58     10110485.91
      2951623.40     10110509.14      2951687.49     10110466.46
      2951749.47     10110539.94      2951818.47     10110533.73

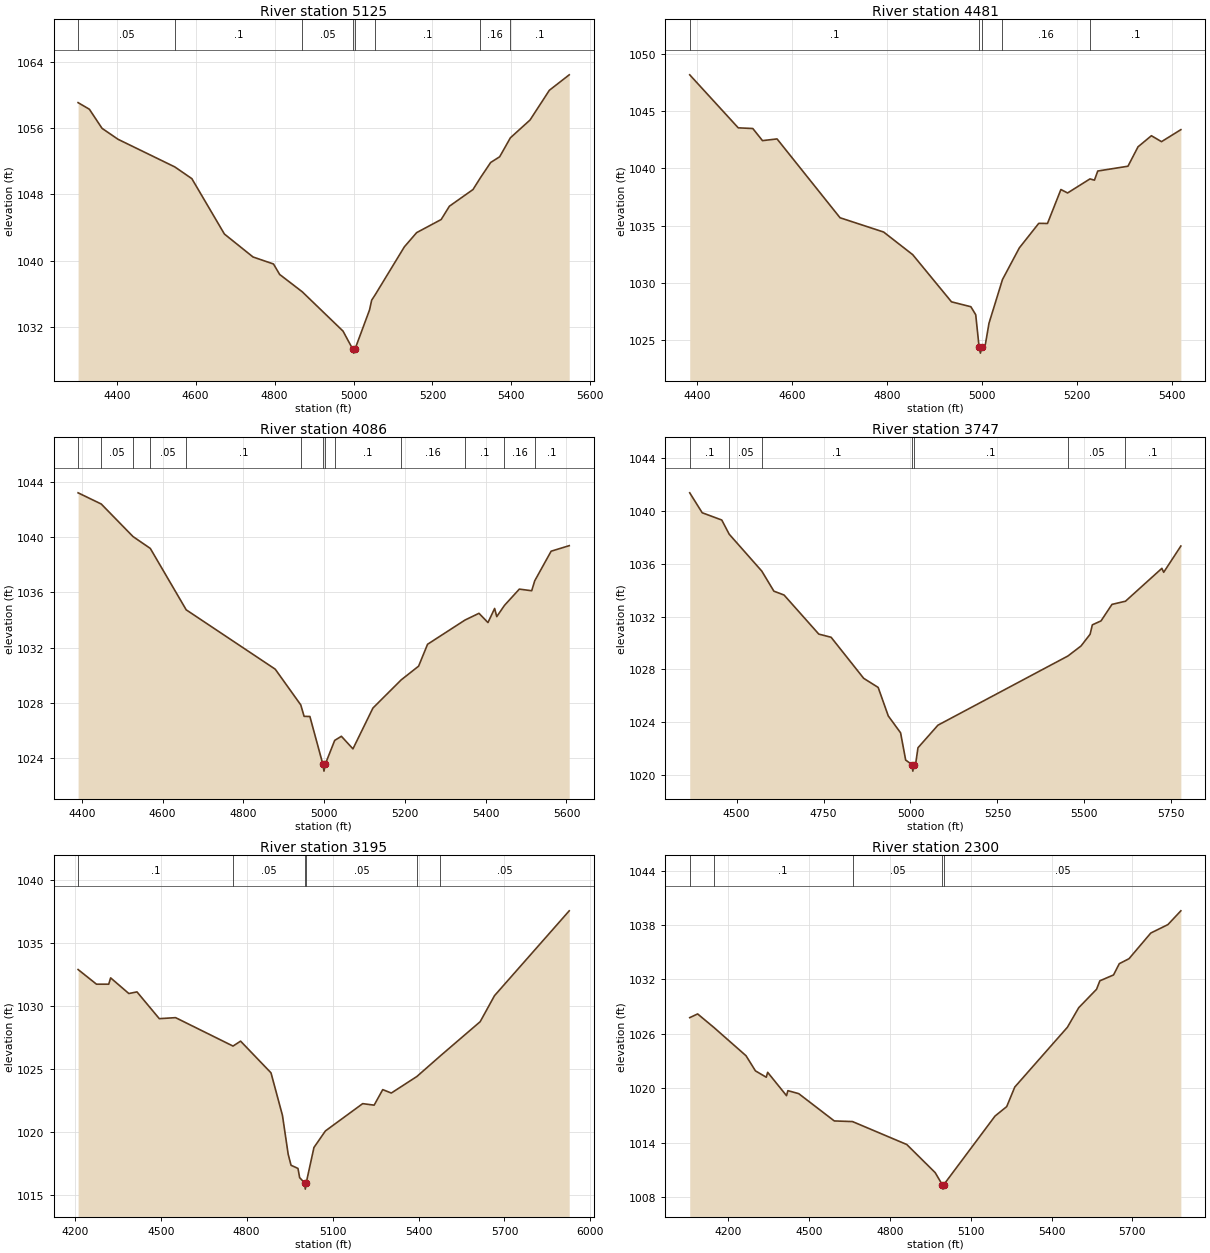
Type RM Length L Ch R = 1,5125,644,644,644
BEGIN DESCRIPTION:
UNT 1019 IN LATR 10.0
END DESCRIPTION:
XS GIS Cut Line= 3
      2947250.86     10109303.61      2948278.63     10109022.37
      2948431.32     10108928.67
#Sta/Elev= 30
  4302.0 1059.13  4330.6 1058.33  4362.6 1056.02  4403.2 1054.69  4547.2 1051.34
  4590.3 1049.92  4672.8 1043.21  4745.3 1040.43  4797.2 1039.58  4812.9 1038.31
  4869.9 1036.22  4973.4 1031.45  4997.9 1029.28  5000.6 1028.78  5003.9 1029.28
  5040.6 1034.01  5046.0 1035.19  5055.3 1035.88  5128.9 1041.66  5160.0 1043.38
  5222.2 1044.97  5243.0 1046.58  5302.8 1048.60  5321.1 1049.99  5347.6 1051.88
  5370.4 1052.57  5397.6 1054.87  5447.3 1057.02  5496.4 1060.63  5546.7 1062.50
#Mann=8,-1,0
  4302.0    0.05       0  4547.2     0.1       0  4869.9    0.05       0
  4997.9   0.035       0  5003.9    0.05       0  5055.3     0.1       0
  5321.1    0.16       0  5397.6     0.1       0
Bank Sta=4997.9,5003.9
Exp/Cntr=0.3,0.1

Type RM Length L Ch R = 1,4481,395,395,395
BEGIN DESCRIPTION:
UNT 1019 IN LATR 9.0
END DESCRIPTION:
XS GIS Cut Line= 3
      2947688.31     10109678.62      2948417.52     10109525.84
      2948624.62     10109322.18
#Sta/Elev= 30
  4383.9 1048.19  4486.2 1043.55  4516.9 1043.49  4537.3 1042.43  4568.0 1042.58
  4700.8 1035.68  4792.7 1034.43  4854.0 1032.45  4935.8 1028.32  4976.7 1027.89
  4986.9 1027.19  4994.1 1024.33  4996.8 1023.83  5000.1 1024.33  5007.3 1024.61
  5014.9 1026.45  5043.3 1030.27  5078.8 1033.04  5119.8 1035.19  5138.2 1035.18
  5166.5 1038.15  5180.6 1037.85  5227.8 1039.08  5237.2 1038.97  5244.2 1039.77
  5307.9 1040.19  5329.1 1041.89  5357.3 1042.86  5378.6 1042.34  5419.4 1043.39
#Mann=5,-1,0
  4383.9     0.1       0  4994.1    0.07       0  5000.1     0.1       0
  5043.3    0.16       0  5227.8     0.1       0
Bank Sta=4994.1,5000.1
Exp/Cntr=0.3,0.1

Type RM Length L Ch R = 1,4086,339,339,339
BEGIN DESCRIPTION:
UNT 1019 IN LATR 8.0
END DESCRIPTION:
XS GIS Cut Line= 3
      2947973.08     10110386.94      2948625.85     10109612.64
      2948695.31     10109421.63
#Sta/Elev= 30
  4390.8 1043.19  4448.2 1042.38  4526.7 1040.03  4569.6 1039.17  4658.5 1034.73
  4878.9 1030.44  4942.1 1027.86  4950.4 1027.03  4964.7 1027.02  4996.8 1023.57
  4999.6 1023.07  5002.8 1023.57  5026.1 1025.29  5042.7 1025.59  5071.3 1024.68
  5120.8 1027.63  5190.5 1029.66  5233.9 1030.66  5256.0 1032.24  5348.6 1033.99
  5383.4 1034.48  5405.6 1033.81  5422.1 1034.83  5427.4 1034.24  5446.4 1035.05
  5483.3 1036.23  5513.9 1036.11  5521.4 1036.83  5562.0 1038.97  5606.8 1039.37
#Mann=13,-1,0
  4390.8     0.1       0  4448.2    0.05       0  4526.7     0.1       0
  4569.6    0.05       0  4658.5     0.1       0  4942.1    0.05       0
  4996.8   0.035       0  5002.8    0.05       0  5026.1     0.1       0
  5190.5    0.16       0  5348.6     0.1       0  5446.4    0.16       0
  5521.4     0.1       0
Bank Sta=4996.8,5002.8
Exp/Cntr=0.3,0.1

Type RM Length L Ch R = 1,3747,552,552,552
BEGIN DESCRIPTION:
UNT 1019 IN LATR 7.0
END DESCRIPTION:
XS GIS Cut Line= 3
      2948098.03     10110532.81      2948799.46     10110005.00
      2948959.17     10109494.64
#Sta/Elev= 30
  4365.1 1041.37  4401.0 1039.86  4457.3 1039.31  4478.5 1038.24  4572.4 1035.44
  4607.2 1033.92  4636.4 1033.63  4736.3 1030.67  4771.7 1030.43  4865.4 1027.32
  4907.1 1026.63  4936.2 1024.47  4971.6 1023.19  4986.2 1021.13  5004.0 1020.79
  5006.8 1020.29  5010.0 1020.79  5015.3 1020.92  5021.6 1022.06  5079.0 1023.77
  5452.8 1029.01  5490.6 1029.77  5516.7 1030.66  5523.1 1031.37  5548.1 1031.67
  5579.6 1032.92  5618.4 1033.16  5723.1 1035.65  5728.3 1035.35  5777.7 1037.34
#Mann=7,-1,0
  4365.1     0.1       0  4478.5    0.05       0  4572.4     0.1       0
  5004.0    0.07       0  5010.0     0.1       0  5452.8    0.05       0
  5618.4     0.1       0
Bank Sta=5004,5010
Exp/Cntr=0.3,0.1

Type RM Length L Ch R = 1,3195,895,895,895
BEGIN DESCRIPTION:
UNT 1019 IN LATR 6.0
END DESCRIPTION:
XS GIS Cut Line= 3
      2948577.27     10110952.90      2949049.46     10110539.73
      2949080.71     10109452.91
#Sta/Elev= 30
  4211.5 1032.87  4275.7 1031.71  4318.4 1031.71  4325.1 1032.21  4388.7 1030.97
  4417.1 1031.10  4495.0 1028.98  4551.9 1029.06  4752.4 1026.81  4778.8 1027.20
  4885.0 1024.69  4925.0 1021.32  4945.0 1018.24  4955.0 1017.37  4979.2 1017.12
  4985.0 1016.39  5002.0 1015.98  5004.8 1015.48  5008.0 1015.98  5035.0 1018.78
  5075.0 1020.09  5205.1 1022.25  5245.1 1022.13  5275.1 1023.36  5305.1 1023.09
  5394.3 1024.40  5476.6 1026.04  5615.3 1028.74  5665.3 1030.80  5926.2 1037.52
#Mann=6,-1,0
  4211.5     0.1       0  4752.4    0.05       0  5002.0   0.035       0
  5008.0    0.05       0  5394.3     0.1       0  5476.6    0.05       0
Bank Sta=5002,5008
Exp/Cntr=0.3,0.1

Type RM Length L Ch R = 1,2300,684,684,684
BEGIN DESCRIPTION:
UNT 1019 IN LATR 5.0
END DESCRIPTION:
XS GIS Cut Line= 3
      2950086.78     10110912.08      2949795.12     10109815.77
      2949412.91     10109243.76
#Sta/Elev= 30
  4057.4 1027.78  4086.7 1028.19  4147.0 1026.70  4266.3 1023.58  4301.3 1021.91
  4341.4 1021.21  4346.6 1021.75  4416.5 1019.18  4421.7 1019.73  4461.8 1019.40
  4593.8 1016.39  4661.5 1016.32  4862.8 1013.79  4968.2 1010.69  4994.3 1009.37
  4997.1 1008.87  5000.3 1009.37  5190.3 1016.93  5233.6 1017.97  5263.6 1020.13
  5458.8 1026.72  5500.9 1028.88  5567.0 1030.91  5579.2 1031.84  5630.0 1032.49
  5651.3 1033.73  5687.4 1034.28  5768.2 1037.11  5831.7 1038.04  5879.8 1039.56
#Mann=5,-1,0
  4057.4    0.16       0  4147.0     0.1       0  4661.5    0.05       0
  4994.3   0.035       0  5000.3    0.05       0
Bank Sta=4994.3,5000.3
Exp/Cntr=0.3,0.1

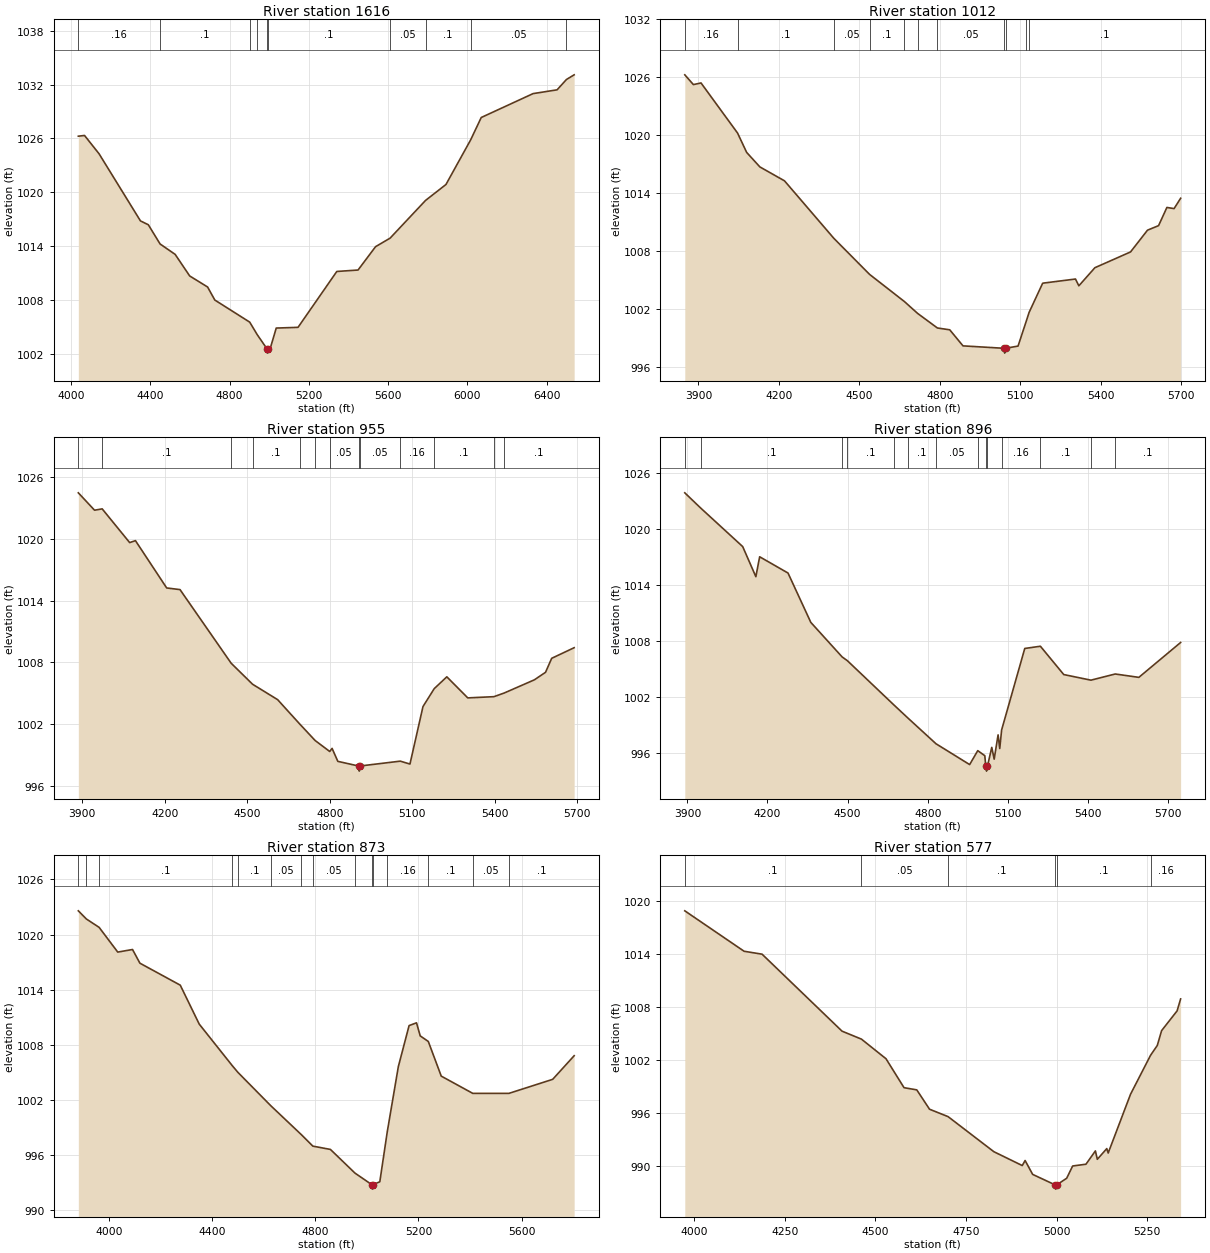
Type RM Length L Ch R = 1,1616,604,604,604
BEGIN DESCRIPTION:
Mapping XS 26f587e3
END DESCRIPTION:
XS GIS Cut Line= 4
      2950178.80     10110914.73      2950475.68     10110300.14
      2950496.51     10109570.98      2949657.96     10108873.05
#Sta/Elev= 30
  4036.6 1026.25  4067.9 1026.33  4141.3 1024.29  4350.2 1016.82  4389.9 1016.39
  4449.4 1014.25  4525.5 1013.09  4598.8 1010.69  4689.2 1009.46  4725.6 1008.01
  4901.8 1005.55  4939.9 1004.15  4988.3 1002.60  4991.0 1002.10  4994.3 1002.60
  5005.7 1002.65  5035.7 1004.89  5145.7 1004.97  5341.4 1011.19  5448.6 1011.35
  5537.1 1013.95  5610.5 1014.90  5789.5 1019.10  5892.4 1020.87  6016.9 1025.83
  6070.6 1028.33  6332.4 1030.99  6453.5 1031.41  6500.7 1032.56  6539.6 1033.08
#Mann=10,-1,0
  4036.6    0.16       0  4449.4     0.1       0  4901.8    0.05       0
  4939.9     0.1       0  4988.3    0.07       0  4994.3     0.1       0
  5610.5    0.05       0  5789.5     0.1       0  6016.9    0.05       0
  6500.7     0.1       0
Bank Sta=4988.3,4994.3
Exp/Cntr=0.3,0.1

Type RM Length L Ch R = 1,1012,57,57,57
BEGIN DESCRIPTION:
UNT 1019 IN LATR 4.0
END DESCRIPTION:
XS GIS Cut Line= 3
      2950284.69     10110935.57      2951222.20     10109906.91
      2951107.61     10109464.18
#Sta/Elev= 30
  3849.1 1026.25  3881.2 1025.24  3909.6 1025.41  4045.9 1020.23  4079.8 1018.23
  4129.1 1016.73  4221.0 1015.29  4405.2 1009.34  4538.2 1005.62  4668.2 1002.81
  4717.2 1001.59  4791.1 1000.08  4837.2  999.89  4886.6  998.23  5039.2  997.98
  5042.0  997.48  5045.2  997.98  5091.9  998.21  5121.7 1000.71  5133.1 1001.69
  5183.8 1004.71  5306.1 1005.14  5318.7 1004.44  5378.5 1006.31  5511.4 1007.94
  5574.7 1010.19  5616.0 1010.66  5647.0 1012.54  5673.8 1012.42  5698.2 1013.49
#Mann=11,-1,0
  3849.1    0.16       0  4045.9     0.1       0  4405.2    0.05       0
  4538.2     0.1       0  4668.2    0.05       0  4717.2     0.1       0
  4791.1    0.05       0  5039.2   0.035       0  5045.2    0.05       0
  5121.7    0.16       0  5133.1     0.1       0
Bank Sta=5039.2,5045.2
Exp/Cntr=0.3,0.1

Type RM Length L Ch R = 1,955,59,59,59
BEGIN DESCRIPTION:
UNT 1019 IN LATR 3.0
END DESCRIPTION:
XS GIS Cut Line= 4
      2950355.03     10110953.77      2951193.56     10110021.50
      2951263.87     10109932.96      2951201.38     10109500.71
#Sta/Elev= 30
  3885.5 1024.49  3944.5 1022.80  3972.3 1022.93  4072.3 1019.65  4093.3 1019.84
  4206.9 1015.24  4255.4 1015.08  4441.5 1007.92  4519.3 1005.88  4610.5 1004.38
  4690.6 1002.02  4746.8 1000.41  4800.0  999.34  4808.6  999.64  4829.5  998.38
  4904.7  997.93  4907.5  997.43  4910.7  997.93  5056.6  998.40  5091.9  998.12
  5139.3 1003.71  5180.2 1005.45  5226.0 1006.60  5302.2 1004.55  5397.3 1004.67
  5434.3 1005.02  5544.7 1006.31  5585.1 1007.04  5607.5 1008.40  5689.2 1009.43
#Mann=13,-1,0
  3885.5    0.16       0  3972.3     0.1       0  4441.5    0.05       0
  4519.3     0.1       0  4690.6    0.05       0  4746.8     0.1       0
  4800.0    0.05       0  4904.7   0.035       0  4910.7    0.05       0
  5056.6    0.16       0  5180.2     0.1       0  5397.3    0.05       0
  5434.3     0.1       0
Bank Sta=4904.7,4910.7
Exp/Cntr=0.3,0.1

Type RM Length L Ch R = 1,896,23,23,23
BEGIN DESCRIPTION:
UNT 1019 IN LATR 2.0
END DESCRIPTION:
XS GIS Cut Line= 4
      2950407.13     10110998.02      2951170.12     10110136.08
      2951305.54     10109956.39      2951261.33     10109477.96
#Sta/Elev= 30
  3890.4 1023.85  3949.2 1022.24  4107.2 1018.10  4156.5 1014.88  4170.7 1017.01
  4276.9 1015.27  4362.3 1009.99  4479.4 1006.30  4499.3 1005.89  4674.5 1001.13
  4726.6  999.74  4830.9  997.01  4957.0  994.78  4987.4  996.27  5013.8  995.73
  5017.5  994.58  5020.3  994.08  5023.5  994.58  5039.8  996.62  5048.9  995.36
  5063.5  997.96  5069.7  996.50  5076.8  998.49  5163.4 1007.20  5221.9 1007.44
  5309.4 1004.41  5411.2 1003.81  5502.1 1004.47  5590.6 1004.11  5747.0 1007.84
#Mann=14,-1,0
  3890.4    0.16       0  3949.2     0.1       0  4479.4    0.05       0
  4499.3     0.1       0  4674.5    0.05       0  4726.6     0.1       0
  4830.9    0.05       0  4987.4     0.1       0  5017.5    0.07       0
  5023.5     0.1       0  5076.8    0.16       0  5221.9     0.1       0
  5411.2    0.05       0  5502.1     0.1       0
Bank Sta=5017.5,5023.5
Exp/Cntr=0.3,0.1

Type RM Length L Ch R = 1,873,296,296,296
BEGIN DESCRIPTION:
UNT 1019 IN LATR 1.0
END DESCRIPTION:
XS GIS Cut Line= 4
      2950448.77     10111039.72      2951201.37     10110130.87
      2951344.60     10109953.79      2951308.14     10109440.74
#Sta/Elev= 30
  3881.7 1022.58  3913.0 1021.69  3962.3 1020.78  4034.5 1018.09  4091.8 1018.37
  4120.5 1016.88  4276.8 1014.49  4350.4 1010.25  4478.7 1005.72  4499.9 1005.01
  4627.7 1001.37  4746.6  998.21  4790.8  996.97  4859.0  996.61  4953.9  994.04
  5018.7  992.79  5021.5  992.29  5024.7  992.79  5050.4  993.09  5079.3  998.53
  5122.3 1005.63  5163.9 1010.09  5192.7 1010.39  5207.0 1008.97  5238.4 1008.36
  5288.6 1004.59  5410.9 1002.71  5550.7 1002.71  5720.6 1004.24  5803.8 1006.81
#Mann=15,-1,0
  3881.7     0.1       0  3913.0    0.16       0  3962.3     0.1       0
  4478.7    0.05       0  4499.9     0.1       0  4627.7    0.05       0
  4746.6     0.1       0  4790.8    0.05       0  4953.9     0.1       0
  5018.7    0.07       0  5024.7     0.1       0  5079.3    0.16       0
  5238.4     0.1       0  5410.9    0.05       0  5550.7     0.1       0
Bank Sta=5018.7,5024.7
Exp/Cntr=0.3,0.1

Type RM Length L Ch R = 1,577,293,293,293
BEGIN DESCRIPTION:
Mapping XS 676b860c
END DESCRIPTION:
XS GIS Cut Line= 4
      2950556.32     10111031.71      2951376.60     10110369.85
      2951413.50     10110261.34      2951341.88     10110074.72
#Sta/Elev= 30
  3973.9 1018.92  4137.6 1014.34  4187.2 1014.01  4407.9 1005.29  4461.4 1004.39
  4529.2 1002.17  4579.0  998.89  4614.2  998.64  4649.4  996.45  4700.6  995.61
  4826.9  991.64  4905.3  990.07  4913.2  990.64  4934.0  989.07  4995.0  987.90
  4997.8  987.40  5001.0  987.90  5027.9  988.63  5044.4  990.02  5081.1  990.22
  5107.2  991.73  5112.5  990.78  5138.6  991.99  5142.5  991.49  5204.2  998.15
  5259.3 1002.55  5278.0 1003.67  5289.9 1005.35  5332.7 1007.59  5342.4 1008.94
#Mann=6,-1,0
  3973.9     0.1       0  4461.4    0.05       0  4700.6     0.1       0
  4995.0    0.07       0  5001.0     0.1       0  5259.3    0.16       0
Bank Sta=4995,5001
Exp/Cntr=0.3,0.1

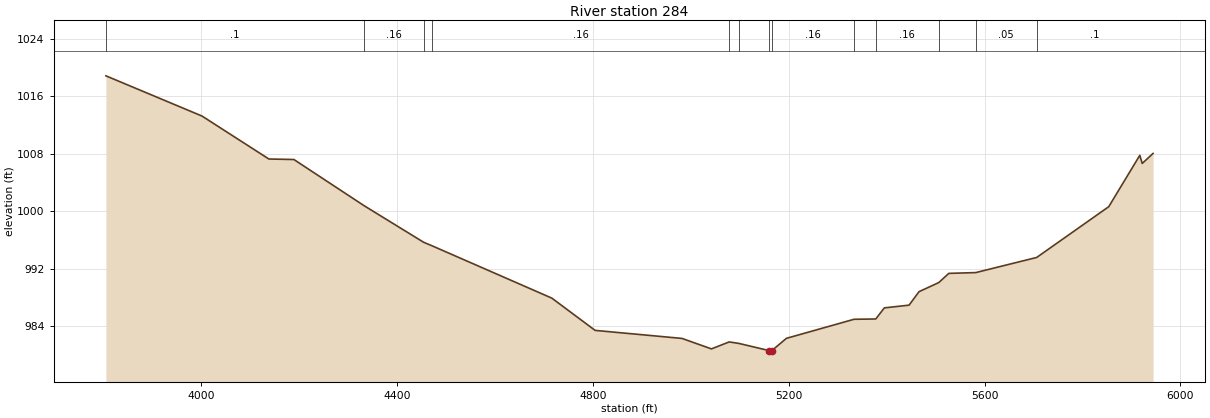
Type RM Length L Ch R = 1,284,0,0,0
BEGIN DESCRIPTION:
Mapping XS 7f201c91
END DESCRIPTION:
XS GIS Cut Line= 4
      2950564.94     10111062.13      2951552.38     10110595.54
      2951619.66     10110419.76      2951489.45     10109571.24
#Sta/Elev= 30
  3805.3 1018.88  4001.6 1013.27  4138.2 1007.28  4189.3 1007.21  4332.9 1000.76
  4454.0  995.68  4471.7  995.17  4716.1  987.88  4804.6  983.38  4982.0  982.26
  5042.1  980.80  5078.3  981.77  5097.7  981.57  5159.6  980.57  5162.3  980.07
  5165.6  980.57  5195.2  982.27  5333.4  984.93  5377.7  984.97  5395.3  986.52
  5445.8  986.90  5466.1  988.78  5506.5  990.05  5526.9  991.33  5581.9  991.44
  5706.4  993.55  5853.6 1000.63  5917.0 1007.79  5922.0 1006.66  5944.1 1008.06
#Mann=13,-1,0
  3805.3     0.1       0  4332.9    0.16       0  4454.0     0.1       0
  4471.7    0.16       0  5078.3    0.12       0  5097.7    0.16       0
  5159.6    0.07       0  5165.6    0.16       0  5333.4     0.1       0
  5377.7    0.16       0  5506.5     0.1       0  5581.9    0.05       0
  5706.4     0.1       0
Bank Sta=5159.6,5165.6
Exp/Cntr=0.3,0.1

Chan Stop Cuts=-1