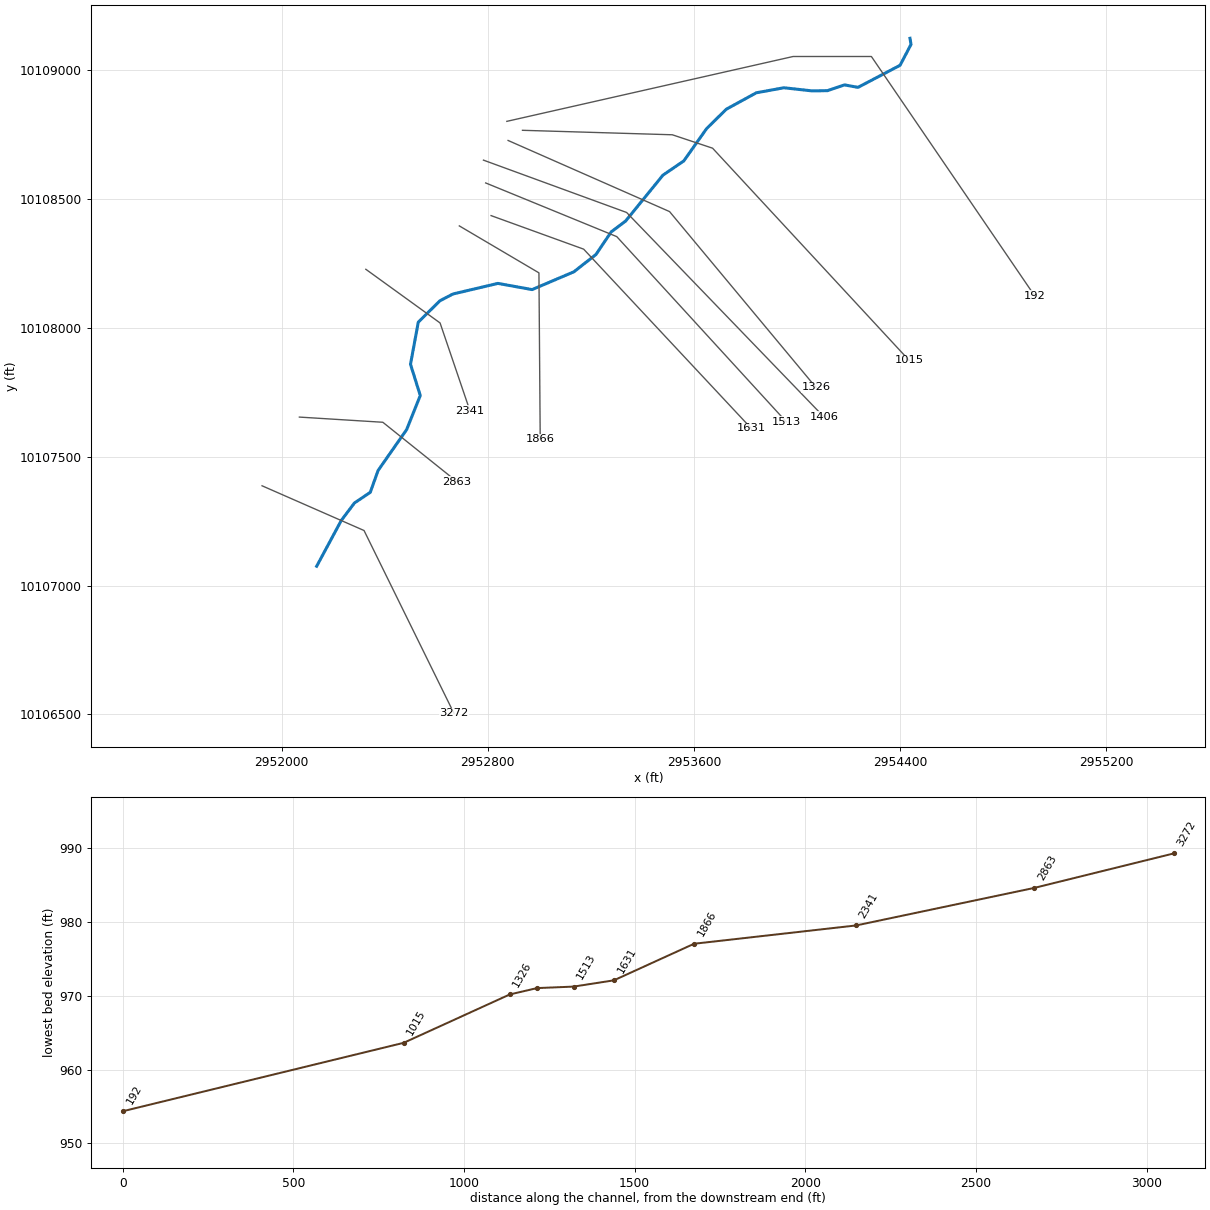
--- UNT 0020 IN LATR.prj (project) ---

Proj Title=UNT 1020 IN LATR Base Level Engineering
Current Plan=p01
Default Exp/Contr=0.3,0.1
English Units
Geom File=g01
Flow File=f01
Plan File=p01
BEGIN DESCRIPTION:
UNT 1020 IN LATR
END DESCRIPTION:

--- UNT 0020 IN LATR.p01 (plan) ---

Plan Title=Multiple Run
Short Identifier=Multiple
Geom File=g01
Flow File=f01
Subcritical Flow
K Sum by GR= 0
Std Step Tol= 0.01
Critical Tol= 0.01
Num of Std Step Trials= 20
Max Error Tol= 0.3
Flow Tol Ratio= 0.001
Split Flow NTrial= 30
Split Flow Tol= 0.02
Split Flow Ratio= 0.02
Log Output Level= 0
Friction Slope Method= 1
Unsteady Friction Slope Method= 2
Unsteady Bridges Friction Slope Method= 1
Parabolic Critical Depth
Global Vel Dist=  1 , 1 , 1
Global Log Level= 0
CheckData=True
Encroach Param= -1, 0, 0, 0
BEGIN DESCRIPTION:
Multiple Run
END DESCRIPTION:

--- UNT 0020 IN LATR.f01 (steady flow) ---

Flow Title=Multiple
Number of Profiles=7
Profile Names=10-year,25-year,50-year,1pct_min,100-year,1pct_plu,500-year
River Rch & RM= UNT 1020 IN LATR,Reach-1,3272
    1010    1471    1873    1746    2361    3193    3763
Boundary for River Rch & Prof#=UNT 1020 IN LATR,Reach-1,1
Up Type=0
Dn Type=3
Dn Slope=0.005
Boundary for River Rch & Prof#=UNT 1020 IN LATR,Reach-1,2
Up Type=0
Dn Type=3
Dn Slope=0.005
Boundary for River Rch & Prof#=UNT 1020 IN LATR,Reach-1,3
Up Type=0
Dn Type=3
Dn Slope=0.005
Boundary for River Rch & Prof#=UNT 1020 IN LATR,Reach-1,4
Up Type=0
Dn Type=3
Dn Slope=0.005
Boundary for River Rch & Prof#=UNT 1020 IN LATR,Reach-1,5
Up Type=0
Dn Type=3
Dn Slope=0.005
Boundary for River Rch & Prof#=UNT 1020 IN LATR,Reach-1,6
Up Type=0
Dn Type=3
Dn Slope=0.005
Boundary for River Rch & Prof#=UNT 1020 IN LATR,Reach-1,7
Up Type=0
Dn Type=3
Dn Slope=0.005

--- UNT 0020 IN LATR.g01 (geometry) ---

Geom Title=Existing Conditions

River Reach=UNT 1020 IN LATR,Reach-1
Reach XY= 30
      2952135.59     10107074.92      2952231.16     10107252.66
      2952282.21     10107320.39      2952343.57     10107361.53
      2952373.78     10107446.22      2952484.80     10107605.25
      2952537.68     10107737.48      2952499.71     10107858.65
      2952529.98     10108022.24      2952613.96     10108105.21
      2952664.37     10108131.39      2952838.94     10108172.59
      2952971.83     10108148.55      2953133.72     10108217.56
      2953219.22     10108284.40      2953278.68     10108372.51
      2953334.67     10108414.61      2953479.43     10108592.62
      2953560.52     10108647.99      2953649.12     10108773.54
      2953725.71     10108848.80      2953842.05     10108912.44
      2953948.88     10108931.90      2954058.57     10108919.75
      2954118.09     10108920.64      2954183.93     10108943.00
      2954236.55     10108933.46      2954399.81     10109019.03
      2954442.28     10109100.12      2954438.47     10109123.73

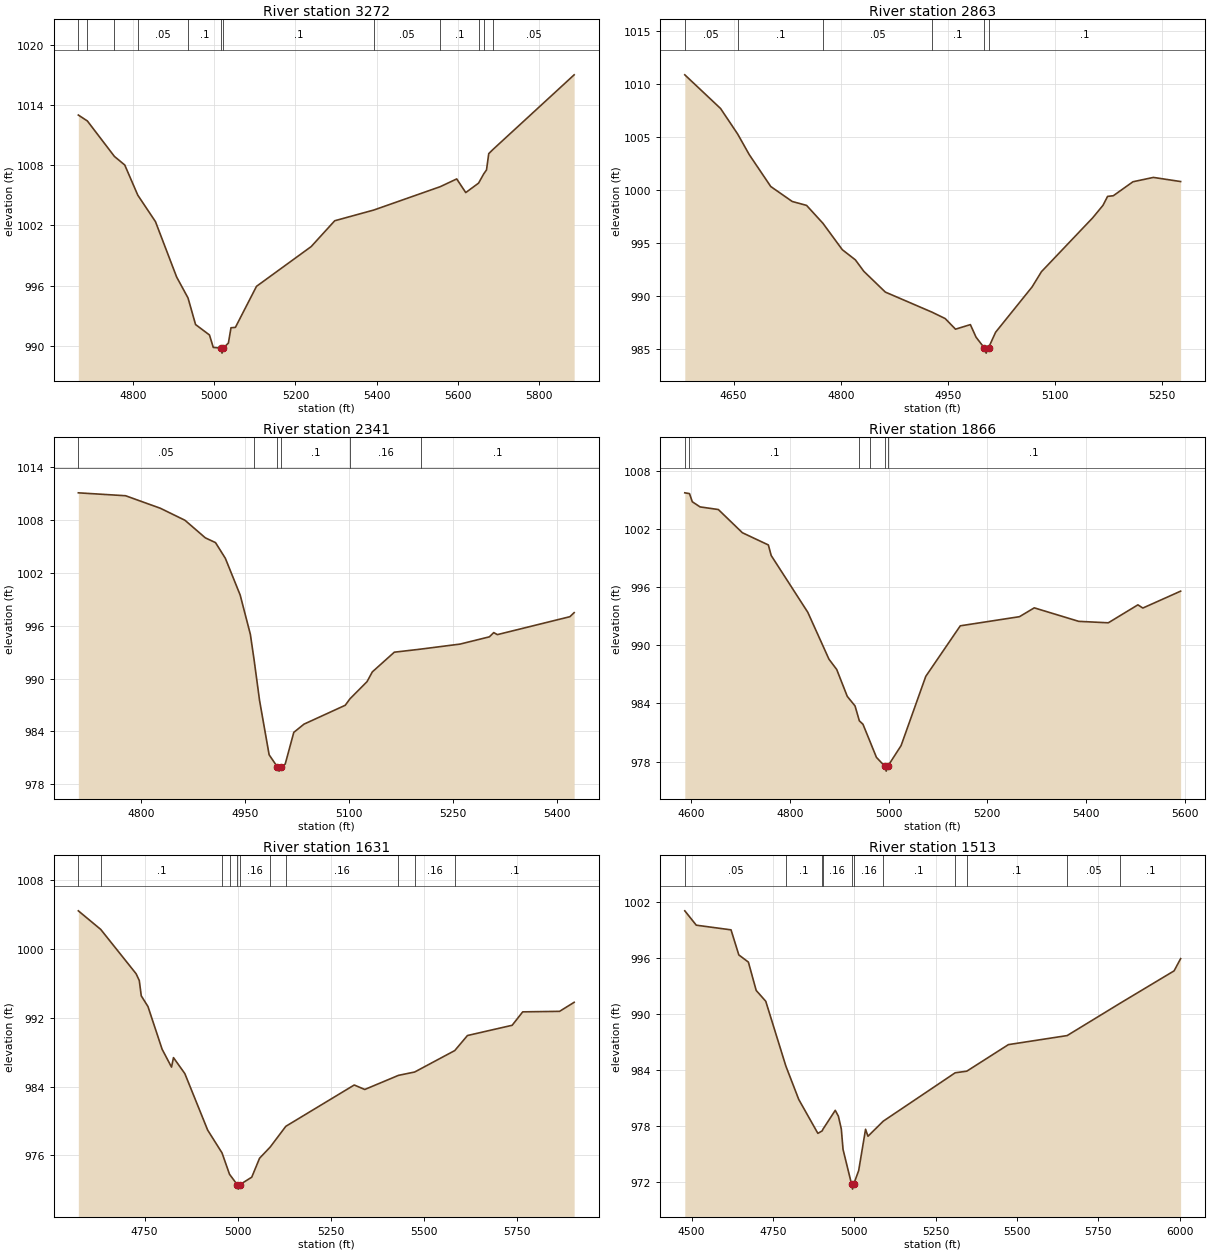
Type RM Length L Ch R = 1,3272,409,409,409
BEGIN DESCRIPTION:
UNT 1020 IN LATR 6.0
END DESCRIPTION:
XS GIS Cut Line= 3
      2951923.60     10107387.08      2952319.40     10107213.48
      2952668.45     10106503.77
#Sta/Elev= 30
  4664.4 1013.00  4686.7 1012.41  4753.5 1008.87  4778.9 1008.02  4811.1 1005.01
  4854.7 1002.37  4906.9  996.85  4935.0  994.76  4953.6  992.11  4987.9  991.07
  4997.3  989.83  5016.1  989.76  5018.9  989.26  5022.1  989.76  5034.6  990.27
  5041.0  991.79  5051.9  991.83  5103.9  995.92  5238.7  999.88  5296.9 1002.46
  5393.4 1003.53  5557.4 1005.86  5597.8 1006.63  5620.1 1005.27  5651.7 1006.21
  5664.7 1007.15  5671.3 1007.53  5676.8 1009.15  5687.3 1009.57  5887.5 1017.01
#Mann=12,-1,0
  4664.4     0.1       0  4686.7    0.05       0  4753.5     0.1       0
  4811.1    0.05       0  4935.0     0.1       0  5016.1    0.07       0
  5022.1     0.1       0  5393.4    0.05       0  5557.4     0.1       0
  5651.7    0.05       0  5664.7     0.1       0  5687.3    0.05       0
Bank Sta=5016.1,5022.1
Exp/Cntr=0.3,0.1

Type RM Length L Ch R = 1,2863,522,522,522
BEGIN DESCRIPTION:
UNT 1020 IN LATR 5.0
END DESCRIPTION:
XS GIS Cut Line= 3
      2952068.44     10107653.73      2952392.32     10107633.62
      2952680.52     10107402.71
#Sta/Elev= 30
  4581.8 1010.85  4631.9 1007.67  4655.9 1005.25  4672.0 1003.32  4702.1 1000.31
  4732.1  998.90  4752.2  998.53  4775.1  996.84  4802.2  994.35  4820.5  993.39
  4832.3  992.31  4862.4  990.35  4927.9  988.45  4946.2  987.85  4960.6  986.85
  4981.4  987.28  4989.4  986.09  5000.8  985.09  5003.5  984.59  5006.8  985.09
  5016.7  986.56  5067.8  990.84  5080.8  992.27  5152.6  997.36  5167.0  998.54
  5173.4  999.38  5181.4  999.44  5208.9 1000.76  5237.5 1001.17  5275.6 1000.78
#Mann=6,-1,0
  4581.8    0.05       0  4655.9     0.1       0  4775.1    0.05       0
  4927.9     0.1       0  5000.8    0.07       0  5006.8     0.1       0
Bank Sta=5000.8,5006.8
Exp/Cntr=0.3,0.1

Type RM Length L Ch R = 1,2341,475,475,475
BEGIN DESCRIPTION:
UNT 1020 IN LATR 4.0
END DESCRIPTION:
XS GIS Cut Line= 3
      2952326.38     10108227.34      2952614.54     10108019.03
      2952730.56     10107677.89
#Sta/Elev= 30
  4709.4 1011.03  4777.6 1010.70  4827.9 1009.28  4863.4 1007.92  4892.8 1005.93
  4907.5 1005.39  4921.7 1003.61  4943.1  999.45  4957.8  995.00  4963.2  992.10
  4971.1  987.50  4984.9  981.36  4996.6  980.01  4999.3  979.51  5002.6  980.01
  5008.1  980.31  5020.5  983.90  5035.2  984.83  5094.8  986.97  5101.6  987.70
  5126.2  989.64  5133.9  990.75  5165.6  992.98  5204.0  993.33  5260.7  993.90
  5302.9  994.72  5309.2  995.20  5314.4  994.97  5419.1  997.00  5425.3  997.46
#Mann=6,-1,0
  4709.4    0.05       0  4963.2     0.1       0  4996.6    0.07       0
  5002.6     0.1       0  5101.6    0.16       0  5204.0     0.1       0
Bank Sta=4996.6,5002.6
Exp/Cntr=0.3,0.1

Type RM Length L Ch R = 1,1866,235,235,235
BEGIN DESCRIPTION:
UNT 1020 IN LATR 3.0
END DESCRIPTION:
XS GIS Cut Line= 3
      2952689.19     10108395.77      2952998.22     10108213.48
      2953003.18     10107567.09
#Sta/Elev= 30
  4586.8 1005.70  4596.3 1005.62  4602.0 1004.78  4617.7 1004.25  4654.8 1003.98
  4703.5 1001.59  4756.2 1000.33  4762.0  999.24  4836.2  993.39  4879.1  988.56
  4894.8  987.50  4916.2  984.73  4931.9  983.75  4940.7  982.21  4948.0  981.86
  4962.3  980.08  4975.3  978.45  4992.3  977.53  4995.1  977.03  4998.3  977.53
  5025.3  979.66  5075.3  986.79  5145.3  992.00  5265.3  992.94  5295.3  993.85
  5385.4  992.46  5445.4  992.31  5505.4  994.16  5515.4  993.83  5592.0  995.57
#Mann=6,-1,0
  4586.8    0.05       0  4596.3     0.1       0  4940.7    0.05       0
  4962.3     0.1       0  4992.3    0.07       0  4998.3     0.1       0
Bank Sta=4992.3,4998.3
Exp/Cntr=0.3,0.1

Type RM Length L Ch R = 1,1631,118,118,118
BEGIN DESCRIPTION:
Mapping XS 92a0423e
END DESCRIPTION:
XS GIS Cut Line= 3
      2952812.48     10108435.69      2953171.83     10108305.49
      2953821.12     10107611.07
#Sta/Elev= 30
  4571.8 1004.42  4632.0 1002.26  4727.1  997.11  4735.7  996.32  4741.0  994.54
  4759.0  993.30  4797.0  988.34  4822.3  986.26  4827.6  987.36  4858.2  985.50
  4919.5  978.94  4958.1  976.29  4978.2  973.81  4999.3  972.58  5002.1  972.08
  5005.3  972.58  5038.0  973.47  5059.0  975.67  5087.6  976.97  5129.6  979.38
  5313.5  984.18  5341.8  983.66  5432.4  985.30  5476.0  985.69  5583.7  988.18
  5617.9  989.93  5738.0  991.12  5766.4  992.68  5865.5  992.74  5904.7  993.79
#Mann=11,-1,0
  4571.8    0.05       0  4632.0     0.1       0  4958.1    0.05       0
  4978.2    0.16       0  4999.3    0.07       0  5005.3    0.16       0
  5087.6     0.1       0  5129.6    0.16       0  5432.4     0.1       0
  5476.0    0.16       0  5583.7     0.1       0
Bank Sta=4999.3,5005.3
Exp/Cntr=0.3,0.1

Type RM Length L Ch R = 1,1513,107,107,107
BEGIN DESCRIPTION:
Mapping XS ed606447
END DESCRIPTION:
XS GIS Cut Line= 3
      2952791.60     10108562.45      2953300.31     10108354.10
      2953958.31     10107635.33
#Sta/Elev= 30
  4479.1 1001.08  4514.4  999.54  4621.2  999.04  4645.2  996.35  4674.6  995.58
  4698.6  992.54  4728.0  991.38  4789.7  984.44  4829.4  980.85  4888.2  977.21
  4901.5  977.48  4903.7  977.65  4941.6  979.68  4951.2  979.06  4960.2  977.69
  4965.6  975.48  4992.0  971.73  4994.8  971.23  4998.0  971.73  5013.6  973.22
  5034.8  977.65  5042.2  976.90  5089.2  978.52  5310.4  983.71  5345.9  983.88
  5473.9  986.73  5654.5  987.70  5817.9  991.18  5983.2  994.64  6003.3  995.95
#Mann=11,-1,0
  4479.1    0.05       0  4789.7     0.1       0  4901.5    0.05       0
  4903.7    0.16       0  4992.0    0.07       0  4998.0    0.16       0
  5089.2     0.1       0  5310.4    0.16       0  5345.9     0.1       0
  5654.5    0.05       0  5817.9     0.1       0
Bank Sta=4992,4998
Exp/Cntr=0.3,0.1

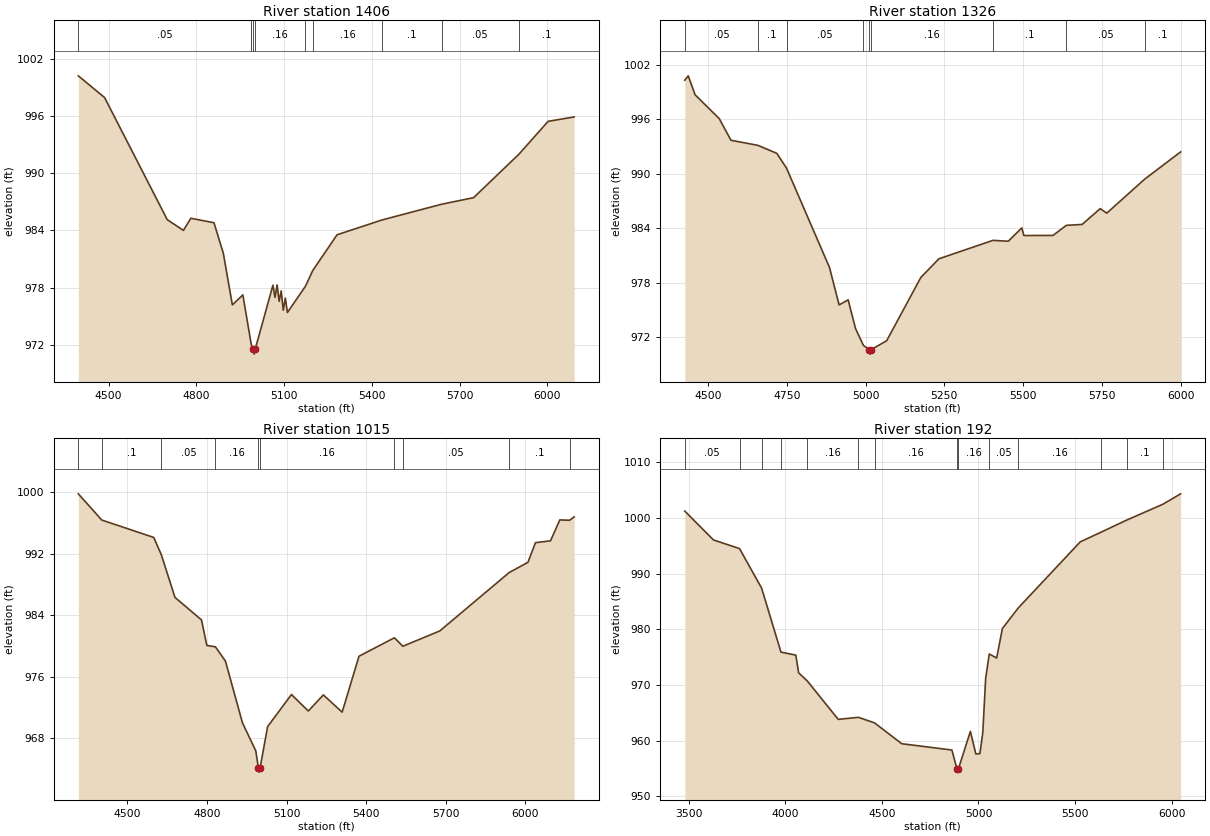
Type RM Length L Ch R = 1,1406,80,80,80
BEGIN DESCRIPTION:
UNT 1020 IN LATR 2.0
END DESCRIPTION:
XS GIS Cut Line= 3
      2952782.93     10108650.98      2953338.50     10108447.85
      2954104.64     10107653.98
#Sta/Elev= 30
  4396.5 1000.20  4486.3  997.92  4700.5  985.12  4755.8  984.00  4781.0  985.27
  4860.2  984.80  4892.2  981.59  4923.0  976.19  4958.9  977.24  4987.9  971.99
  4994.9  971.53  4997.7  971.03  5000.9  971.53  5061.7  978.26  5068.7  976.98
  5075.9  978.29  5082.8  976.56  5090.0  977.66  5097.0  975.63  5104.2  976.90
  5111.1  975.39  5172.8  978.14  5197.6  979.78  5280.9  983.54  5435.4  985.10
  5638.1  986.74  5747.6  987.43  5902.4  991.98  6002.3  995.43  6091.3  995.89
#Mann=9,-1,0
  4396.5    0.05       0  4987.9    0.16       0  4994.9    0.07       0
  5000.9    0.16       0  5172.8     0.1       0  5197.6    0.16       0
  5435.4     0.1       0  5638.1    0.05       0  5902.4     0.1       0
Bank Sta=4994.9,5000.9
Exp/Cntr=0.3,0.1

Type RM Length L Ch R = 1,1326,311,311,311
BEGIN DESCRIPTION:
Mapping XS 1eb989b0
END DESCRIPTION:
XS GIS Cut Line= 3
      2952878.46     10108727.35      2953505.17     10108451.32
      2954073.44     10107768.71
#Sta/Elev= 30
  4426.7 1000.30  4437.6 1000.79  4459.5  998.70  4536.0  996.08  4573.2  993.70
  4658.7  993.14  4718.6  992.26  4749.5  990.63  4885.6  979.72  4916.2  975.59
  4945.0  976.14  4968.3  972.99  4993.3  971.13  5012.0  970.67  5014.7  970.17
  5018.0  970.67  5067.1  971.64  5175.6  978.61  5232.9  980.66  5404.5  982.69
  5452.9  982.59  5495.9  984.06  5502.4  983.22  5594.8  983.23  5637.2  984.34
  5687.3  984.44  5744.6  986.18  5765.4  985.68  5886.3  989.44  5999.7  992.42
#Mann=9,-1,0
  4426.7    0.05       0  4658.7     0.1       0  4749.5    0.05       0
  4993.3    0.16       0  5012.0    0.07       0  5018.0    0.16       0
  5404.5     0.1       0  5637.2    0.05       0  5886.3     0.1       0
Bank Sta=5012,5018
Exp/Cntr=0.3,0.1

Type RM Length L Ch R = 1,1015,823,823,823
BEGIN DESCRIPTION:
Mapping XS c9b190e5
END DESCRIPTION:
XS GIS Cut Line= 4
      2952934.35     10108766.79      2953515.94     10108749.43
      2953672.19     10108697.35      2954434.76     10107874.12
#Sta/Elev= 30
  4315.3  999.81  4403.7  996.40  4599.5  994.14  4628.0  991.90  4679.6  986.34
  4779.6  983.41  4799.6  980.09  4831.9  979.92  4869.7  978.06  4933.8  970.04
  4984.1  966.39  4994.1  964.12  4996.8  963.62  5000.1  964.12  5028.7  969.54
  5118.5  973.71  5182.1  971.57  5238.7  973.66  5309.6  971.42  5373.1  978.69
  5506.5  981.09  5538.5  979.99  5677.6  981.98  5939.0  989.57  6009.8  990.90
  6038.2  993.46  6094.9  993.70  6130.0  996.42  6166.6  996.37  6184.0  996.81
#Mann=10,-1,0
  4315.3    0.05       0  4403.7     0.1       0  4628.0    0.05       0
  4831.9    0.16       0  4994.1    0.07       0  5000.1    0.16       0
  5506.5     0.1       0  5538.5    0.05       0  5939.0     0.1       0
  6166.6    0.05       0
Bank Sta=4994.1,5000.1
Exp/Cntr=0.3,0.1

Type RM Length L Ch R = 1,192,0,0,0
BEGIN DESCRIPTION:
UNT 1020 IN LATR 1.0
END DESCRIPTION:
XS GIS Cut Line= 4
      2952873.61     10108801.52      2953984.69     10109053.25
      2954288.51     10109053.25      2954922.16     10108124.47
#Sta/Elev= 30
  3479.5 1001.22  3628.0  996.04  3762.9  994.49  3877.2  987.40  3977.4  975.91
  4054.4  975.36  4068.9  972.19  4112.7  970.77  4274.0  963.83  4378.3  964.20
  4462.0  963.20  4602.8  959.46  4862.5  958.33  4889.5  954.86  4892.3  954.36
  4895.5  954.86  4958.3  961.67  4986.6  957.62  5007.5  957.68  5022.5  961.43
  5037.4  971.20  5056.2  975.57  5094.3  974.84  5124.1  980.14  5206.9  983.86
  5527.2  995.70  5634.7  997.43  5767.2  999.60  5953.9 1002.43  6046.9 1004.32
#Mann=14,-1,0
  3479.5    0.05       0  3762.9     0.1       0  3877.2    0.16       0
  3977.4    0.05       0  4112.7    0.16       0  4378.3    0.12       0
  4462.0    0.16       0  4889.5    0.07       0  4895.5    0.16       0
  5056.2    0.05       0  5206.9    0.16       0  5634.7    0.05       0
  5767.2     0.1       0  5953.9    0.05       0
Bank Sta=4889.5,4895.5
Exp/Cntr=0.3,0.1

Chan Stop Cuts=-1