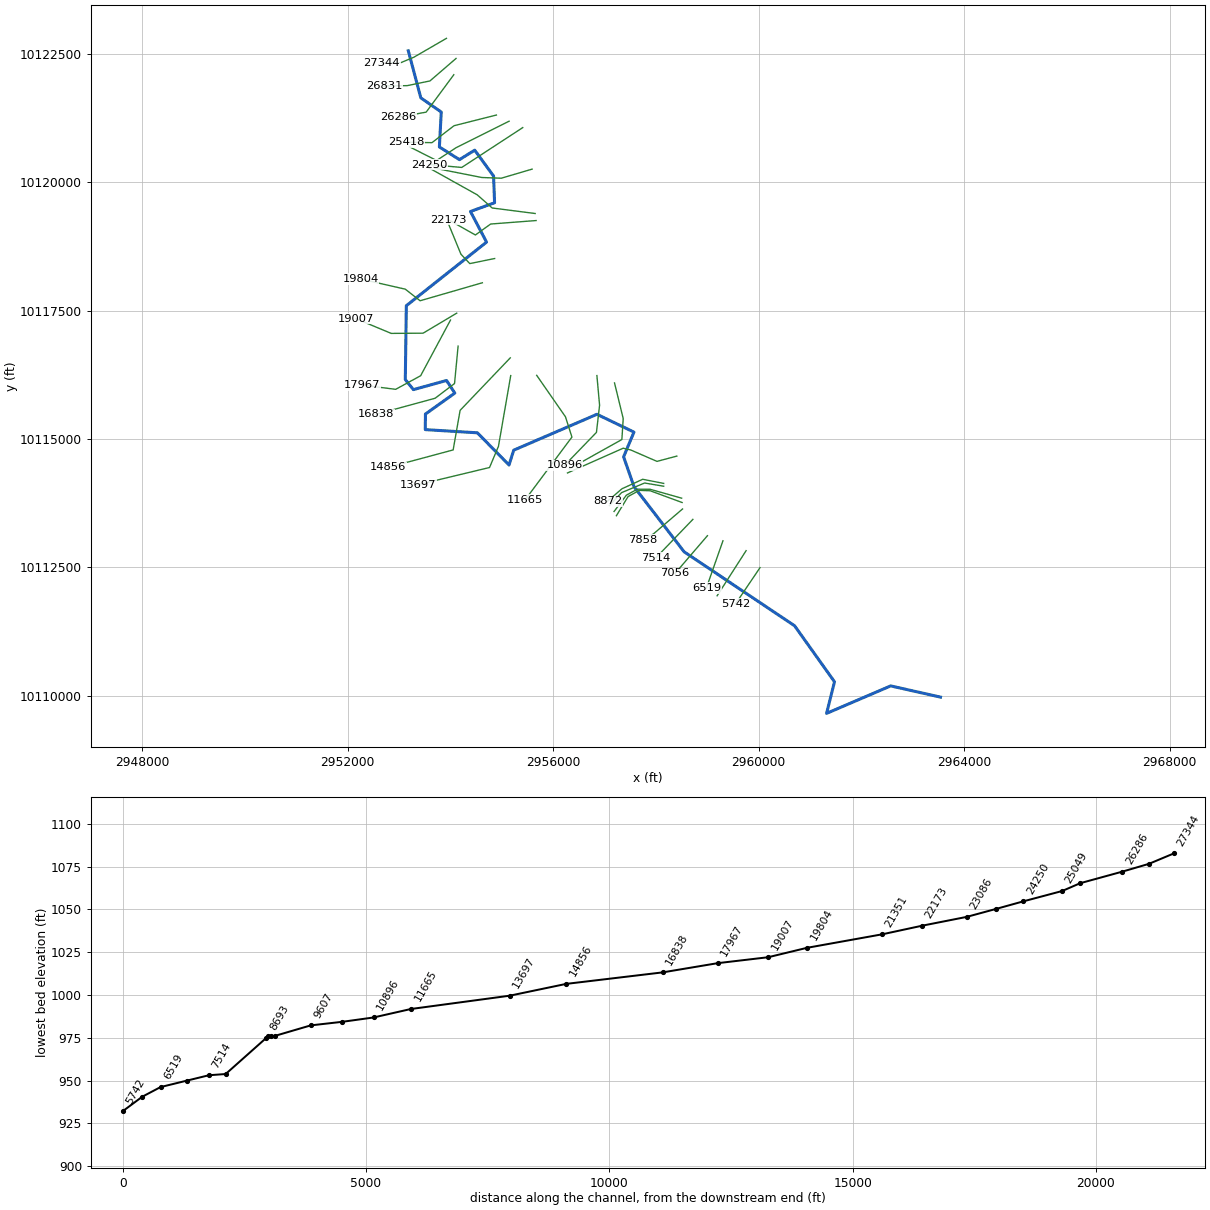
--- UNT 0022 IN LATR.prj (project) ---

Proj Title=UNT 1022 IN LATR Base Level Engineering
Current Plan=p01
Default Exp/Contr=0.3,0.1
English Units
Geom File=g01
Flow File=f01
Plan File=p01
Y Axis Title=Elevation
X Axis Title(PF)=Main Channel Distance
X Axis Title(XS)=Station
BEGIN DESCRIPTION:
UNT 1022 IN LATR
END DESCRIPTION:
DSS Export Rating Curves= 0
DSS Export Rating Curve Sorted= 0
DSS Export Volume Flow Curves= 0
DXF OffsetX= 0
DXF OffsetY= 0
DXF ScaleX= 1
DXF ScaleY= 10

--- UNT 0022 IN LATR.p01 (plan) ---

Plan Title=Multiple Run
Short Identifier=Multiple
Geom File=g01
Flow File=f01
Subcritical Flow
K Sum by GR= 0
Std Step Tol= 0.01
Critical Tol= 0.01
Num of Std Step Trials= 20
Max Error Tol= 0.3
Flow Tol Ratio= 0.001
Split Flow NTrial= 30
Split Flow Tol= 0.02
Split Flow Ratio= 0.02
Log Output Level= 0
Friction Slope Method= 1
Unsteady Friction Slope Method= 2
Unsteady Bridges Friction Slope Method= 1
Parabolic Critical Depth
Global Vel Dist=  1 , 1 , 1
Global Log Level= 0
CheckData=True
Encroach Param= -1, 0, 0, 0
BEGIN DESCRIPTION:
Multiple Run
END DESCRIPTION:

--- UNT 0022 IN LATR.f01 (steady flow) ---

Flow Title=Multiple
Program Version=4.10
Number of Profiles= 7
Profile Names=10-year,25-year,50-year,1pct_min,100-year,1pct_plu,500-year
River Rch & RM=UNT 1022 IN LATR,Reach-1         ,27344
    1097    1608    2055    1922    2599    3515    4174
River Rch & RM=UNT 1022 IN LATR,Reach-1         ,19804
    1890    2832    3672    3475    4700    6356    7736
River Rch & RM=UNT 1022 IN LATR,Reach-1         ,9607
    2681    4075    5338    5097    6893    9321   11550
River Rch & RM=UNT 1022 IN LATR,Reach-1         ,8872
    2681    4075    5338    5097    6893    9321   11550
River Rch & RM=UNT 1022 IN LATR,Reach-1         ,2535
    2991    4565    5996    5739    7762   10497   13072
Boundary for River Rch & Prof#=UNT 1022 IN LATR,Reach-1         , 1
Up Type= 0
Dn Type= 3
Dn Slope=0.013
Boundary for River Rch & Prof#=UNT 1022 IN LATR,Reach-1         , 2
Up Type= 0
Dn Type= 3
Dn Slope=0.013
Boundary for River Rch & Prof#=UNT 1022 IN LATR,Reach-1         , 3
Up Type= 0
Dn Type= 3
Dn Slope=0.013
Boundary for River Rch & Prof#=UNT 1022 IN LATR,Reach-1         , 4
Up Type= 0
Dn Type= 3
Dn Slope=0.013
Boundary for River Rch & Prof#=UNT 1022 IN LATR,Reach-1         , 5
Up Type= 0
Dn Type= 3
Dn Slope=0.013
Boundary for River Rch & Prof#=UNT 1022 IN LATR,Reach-1         , 6
Up Type= 0
Dn Type= 3
Dn Slope=0.013
Boundary for River Rch & Prof#=UNT 1022 IN LATR,Reach-1         , 7
Up Type= 0
Dn Type= 3
Dn Slope=0.013
DSS Import GetInterval= 0
DSS Import GetPeak= 0
DSS Import FillOption= 0

--- UNT 0022 IN LATR.g01 (geometry) ---

Geom Title=Existing Conditions
Program Version=4.10

River Reach=UNT 1022 IN LATR,Reach-1
Reach XY= 30
      2953178.47     10122563.73      2953422.09     10121646.96
        2953820.     10121370.92      2953783.37     10120690.86
      2954174.04     10120443.65      2954471.21     10120628.46
      2954838.35     10120123.57      2954857.85      10119603.9
      2954388.93     10119433.54      2954701.38     10118837.41
      2953140.02     10117598.17      2953119.96      10116159.4
      2953277.73     10115963.65      2953922.55     10116141.94
      2954084.14     10115896.58      2953512.06     10115487.83
      2953508.98     10115184.35        2954523.     10115122.55
      2955138.74     10114495.77      2955230.51     10114784.14
      2956850.56     10115483.08       2957570.9     10115136.36
      2957369.65     10114654.27      2957573.27     10114070.76
      2958547.56     10112804.65      2960697.91     10111363.57
       2961474.9     10110272.24      2961320.37     10109657.09
      2962568.69     10110192.36      2963538.47     10109973.73

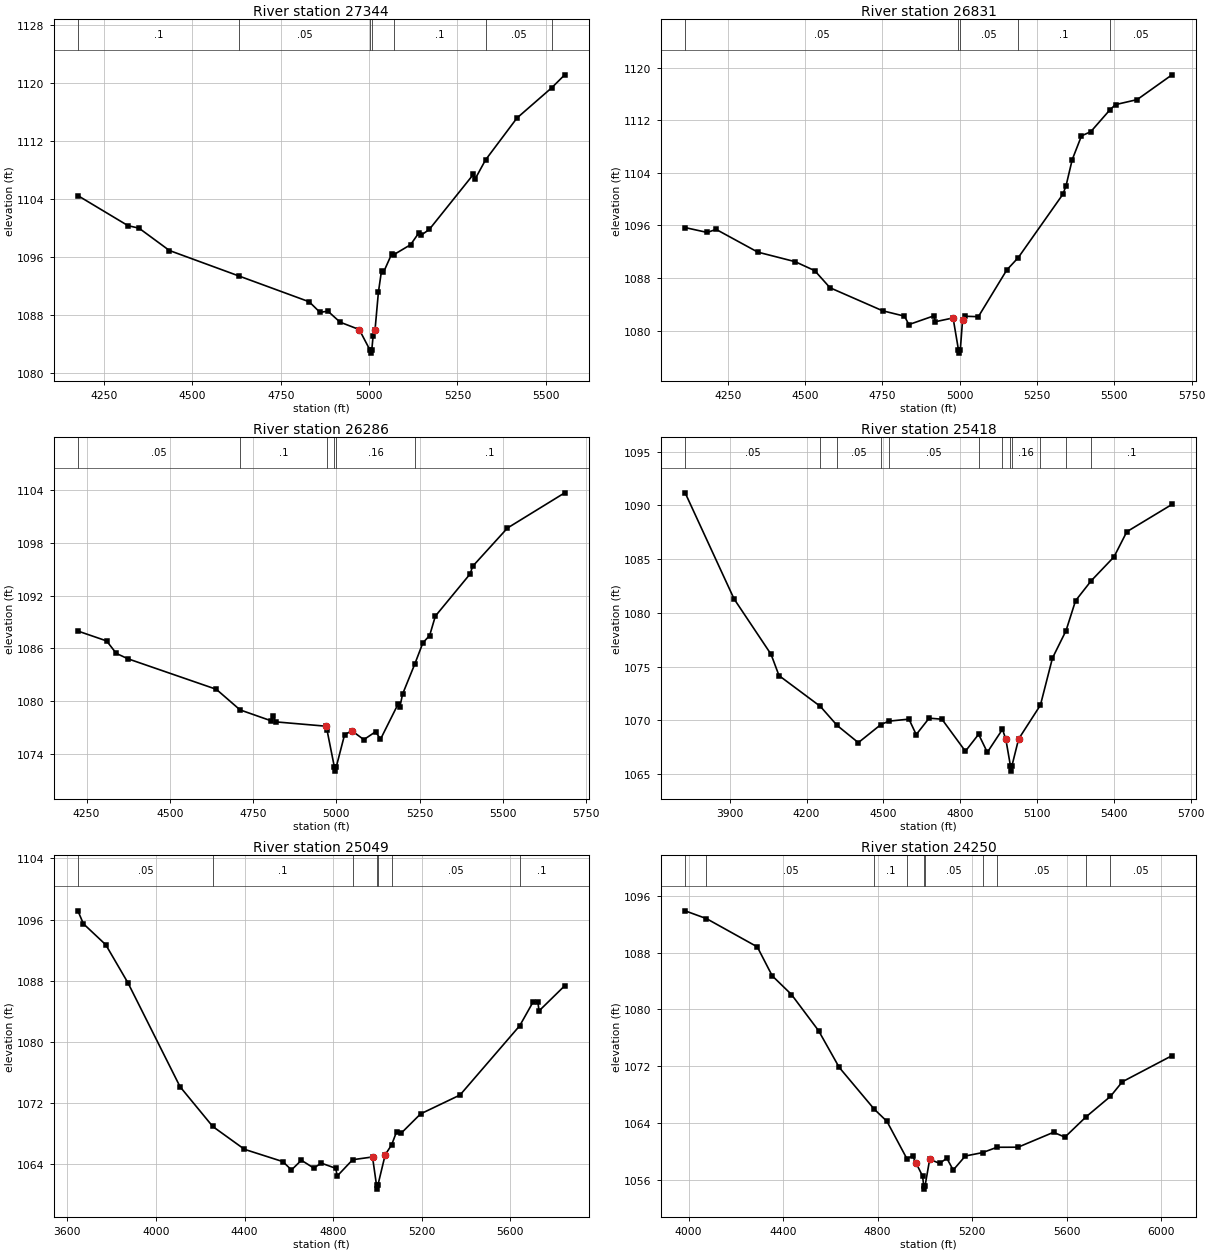
Type RM Length L Ch R = 1 ,27344   ,513,513,513
BEGIN DESCRIPTION:
UNT 1022 IN LATR 37.0
END DESCRIPTION:
XS GIS Cut Line= 4
      2953921.25     10122806.66      2953288.44     10122439.47
      2953033.23      10122332.7      2952663.43     10122319.67
#Sta/Elev= 30
  4175.5 1104.46  4317.5  1100.3  4348.5 1099.96  4434.6 1096.87  4632.9 1093.32
  4830.4 1089.78  4860.9 1088.32  4883.4 1088.48  4917.9 1086.96  4972.1 1085.94
  5001.7 1083.18  5004.4 1082.68  5007.7 1083.18  5011.4 1085.07  5016.8  1085.9
  5026.3 1091.09  5035.2 1094.09  5040.6 1093.84  5064.4 1096.44  5069.1 1096.27
  5117.4 1097.67  5141.2 1099.33  5146.6 1098.96  5170.4 1099.78    5295 1107.38
    5300 1106.74  5329.6 1109.39  5418.7 1115.19    5517 1119.37  5553.8 1121.16
#Mann= 7 ,-1 , 0
  4175.5      .1       0  4632.9     .05       0  5001.7    .035       0
  5007.7     .05       0  5069.1      .1       0  5329.6     .05       0
    5517      .1       0
Bank Sta=4972.1,5016.8
XS Rating Curve= 0 ,0
Exp/Cntr=0.3,0.1

Type RM Length L Ch R = 1 ,26831   ,545,545,545
BEGIN DESCRIPTION:
UNT 1022 IN LATR 36.0
END DESCRIPTION:
XS GIS Cut Line= 4
      2954107.92     10122415.19      2953600.07     10121976.79
       2953161.7     10121885.65      2952705.92     10121876.97
#Sta/Elev= 30
  4111.8 1095.67  4183.3 1094.93  4211.8  1095.4  4346.7 1091.94  4467.4 1090.49
    4531 1089.12  4580.4 1086.52  4750.5 1083.02  4821.2  1082.2  4835.4 1080.92
  4916.3 1082.25  4921.4 1081.36  4978.4 1081.93  4995.8 1077.08  4998.6 1076.58
  5001.8 1077.08    5009 1081.58  5016.5 1082.19  5060.1 1082.12    5152 1089.22
  5189.3 1091.11  5333.7 1100.75  5343.7 1102.03  5363.7    1106  5393.7 1109.62
  5423.7 1110.25  5485.7 1113.58  5503.7 1114.37  5573.7 1115.13  5686.3  1118.9
#Mann= 5 ,-1 , 0
  4111.8     .05       0  4995.8    .035       0  5001.8     .05       0
  5189.3      .1       0  5485.7     .05       0
Bank Sta=4978.4,5009
XS Rating Curve= 0 ,0
Exp/Cntr=0.3,0.1

Type RM Length L Ch R = 1 ,26286   ,868,868,868
BEGIN DESCRIPTION:
UNT 1022 IN LATR 34.0
END DESCRIPTION:
XS GIS Cut Line= 3
      2954064.47      10122098.3      2953526.28     10121369.15
      2952979.38     10121269.32
#Sta/Elev= 30
  4223.9 1087.96  4310.1 1086.84  4339.3 1085.42  4374.8  1084.8  4639.7 1081.34
    4711    1079  4802.8 1077.78  4811.2 1078.28  4817.5 1077.64  4967.8 1077.15
  4971.9 1076.77  4994.1 1072.54  4996.8 1072.04  5000.1 1072.54    5025 1076.19
  5047.2 1076.62  5082.7 1075.62  5118.2 1076.52  5132.8 1075.66    5186 1079.69
  5191.1 1079.34  5199.1 1080.79  5235.7  1084.2  5260.1 1086.62  5280.4 1087.45
  5297.6 1089.66  5402.4 1094.47  5409.2  1095.3  5514.2 1099.67  5686.1 1103.67
#Mann= 6 ,-1 , 0
  4223.9     .05       0    4711      .1       0  4971.9     .16       0
  4994.1     .07       0  5000.1     .16       0  5235.7      .1       0
Bank Sta=4967.8,5047.2
XS Rating Curve= 0 ,0
Exp/Cntr=0.3,0.1

Type RM Length L Ch R = 1 ,25418   ,369,369,369
BEGIN DESCRIPTION:
UNT 1022 IN LATR 33.0
END DESCRIPTION:
XS GIS Cut Line= 4
      2954893.48     10121312.73      2954068.82      10121104.4
      2953639.13     10120774.54      2953132.38      10120783.2
#Sta/Elev= 30
  3726.2 1091.17    3917  1081.3  4061.4 1076.14  4092.4 1074.16  4253.4  1071.3
  4319.2 1069.52  4401.8 1067.92  4489.6  1069.6  4520.6 1069.92  4599.3 1070.11
  4627.6 1068.67  4678.1  1070.2    4728  1070.1  4819.5 1067.12  4871.1  1068.7
    4905 1067.02  4964.1 1069.16  4977.3 1068.23  4995.1 1065.77  4997.8 1065.27
  5001.1 1065.77  5027.1 1068.26  5112.1 1071.41  5159.1 1075.79    5212 1078.34
  5249.2 1081.13  5310.8    1083  5399.2 1085.21  5449.2 1087.55  5625.3 1090.09
#Mann= 12 ,-1 , 0
  3726.2     .05       0  4253.4      .1       0  4319.2     .05       0
  4489.6      .1       0  4520.6     .05       0  4871.1      .1       0
  4964.1     .16       0  4995.1     .07       0  5001.1     .16       0
  5112.1      .1       0    5212     .05       0  5310.8      .1       0
Bank Sta=4977.3,5027.1
XS Rating Curve= 0 ,0
Exp/Cntr=0.3,0.1

Type RM Length L Ch R = 1 ,25049   ,799,799,799
BEGIN DESCRIPTION:
Mapping XS ddfc4034
END DESCRIPTION:
XS GIS Cut Line= 4
      2955140.65     10121192.64      2954109.43     10120677.03
      2953729.22     10120427.03      2953203.33     10120692.57
#Sta/Elev= 30
  3647.9 1097.15  3672.7 1095.46  3773.7 1092.71  3873.9 1087.72  4109.1 1074.12
  4256.6 1068.92  4399.8 1065.93  4573.1 1064.32  4611.8 1063.23  4656.6  1064.5
  4712.8 1063.47    4746 1064.13    4812 1063.44  4817.9 1062.42  4887.9 1064.57
  4977.6 1064.93  4995.7 1061.22  4998.5 1060.72  5001.7 1061.22  5034.9 1065.22
  5064.1 1066.53  5086.1 1068.23  5107.2 1068.05  5194.6 1070.57  5372.5 1073.04
    5642 1082.11  5701.3 1085.17  5723.6 1085.26  5729.2 1084.05    5845 1087.34
#Mann= 7 ,-1 , 0
  3647.9     .05       0  4256.6      .1       0  4887.9     .16       0
  4995.7     .07       0  5001.7     .16       0  5064.1     .05       0
    5642      .1       0
Bank Sta=4977.6,5034.9
XS Rating Curve= 0 ,0
Exp/Cntr=0.3,0.1

Type RM Length L Ch R = 1 ,24250   ,554,554,554
BEGIN DESCRIPTION:
Mapping XS 279a227b
END DESCRIPTION:
XS GIS Cut Line= 3
      2955406.27     10121067.63       2954218.8     10120291.61
      2953579.11     10120348.82
#Sta/Elev= 30
    3985  1093.9  4075.4  1092.8  4290.4 1088.82  4353.6 1084.74  4435.2  1082.1
  4549.7 1077.01  4637.2 1071.83  4785.5 1065.94  4839.3 1064.22  4923.7 1058.96
  4947.9 1059.34    4962 1058.38  4990.1 1056.51  4994.8 1055.17  4997.5 1054.67
  5000.8 1055.17  5020.3 1058.88  5062.5 1058.29  5092.7 1059.03  5119.8 1057.36
  5171.1 1059.34  5244.3 1059.82  5305.1 1060.57  5394.3 1060.58  5544.4 1062.68
  5592.7    1062  5681.8 1064.85  5785.6 1067.75  5835.6  1069.8  6045.8 1073.48
#Mann= 10 ,-1 , 0
    3985      .1       0  4075.4     .05       0  4785.5      .1       0
  4923.7     .05       0  4994.8    .035       0  5000.8     .05       0
  5244.3      .1       0  5305.1     .05       0  5681.8     .16       0
  5785.6     .05       0
Bank Sta=4962,5020.3
XS Rating Curve= 0 ,0
Exp/Cntr=0.3,0.1

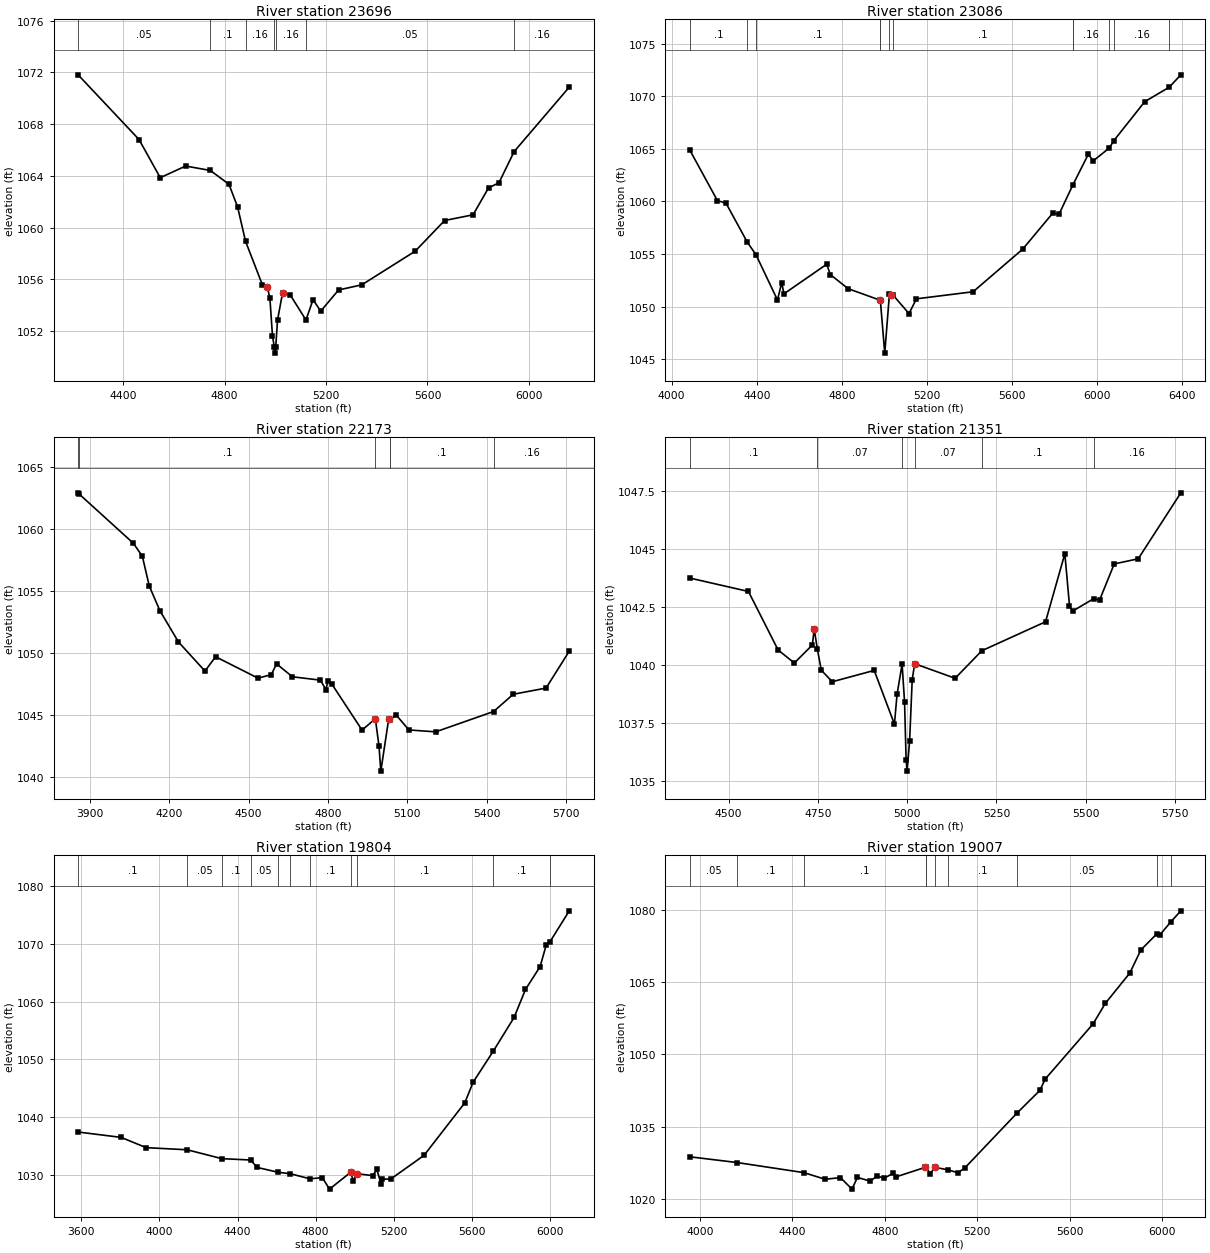
Type RM Length L Ch R = 1 ,23696   ,610,610,610
BEGIN DESCRIPTION:
UNT 1022 IN LATR 32.0
END DESCRIPTION:
XS GIS Cut Line= 4
      2955588.78     10120258.91      2954988.09     10120081.83
      2954609.62     10120095.72      2953696.47     10120276.26
#Sta/Elev= 30
    4223 1071.81  4463.1 1066.81  4546.8 1063.86  4646.8 1064.76    4744 1064.42
  4817.6 1063.35  4851.6  1061.6    4883 1058.94  4948.9  1055.6  4968.9  1055.4
    4979 1054.53    4989 1051.65    4996  1050.8  4998.7  1050.3    5002  1050.8
    5009 1052.85    5029 1054.98    5059  1054.8  5121.1 1052.86  5149.1 1054.44
  5179.1 1053.54  5249.5 1055.18  5341.3 1055.58  5551.6 1058.18  5667.5 1060.55
  5779.6 1060.99  5840.8 1063.08  5881.5 1063.46  5941.6 1065.88  6158.8 1070.86
#Mann= 7 ,-1 , 0
    4223     .05       0    4744      .1       0    4883     .16       0
    4996     .07       0    5002     .16       0  5121.1     .05       0
  5941.6     .16       0
Bank Sta=4968.9,5029
XS Rating Curve= 0 ,0
Exp/Cntr=0.3,0.1

Type RM Length L Ch R = 1 ,23086   ,913,913,913
BEGIN DESCRIPTION:
UNT 1022 IN LATR 31.0
END DESCRIPTION:
XS GIS Cut Line= 4
      2955647.82     10119394.33      2954811.01     10119501.97
      2954519.34     10119758.91      2953578.36     10120283.22
#Sta/Elev= 30
  4084.9  1064.9  4215.3 1060.08  4255.6 1059.84  4355.5 1056.14  4396.8 1054.93
  4497.6 1050.64  4517.8 1052.29  4527.9 1051.22  4729.5 1054.04  4745.6 1053.06
  4830.3 1051.71  4981.4 1050.61  5002.1 1045.59  5024.1 1051.19  5030.8 1051.14
    5042 1051.08  5116.1 1049.35  5151.3 1050.75  5417.6 1051.42  5650.8 1055.47
  5791.4 1058.87    5822  1058.8  5886.7 1061.57  5959.5 1064.49  5982.3 1063.85
  6058.6 1065.09  6079.4 1065.78  6224.7 1069.48  6339.6 1070.85  6394.5 1072.03
#Mann= 12 ,-1 , 0
  4084.9      .1       0  4355.5     .16       0  4396.8      .1       0
  4981.4     .16       0  4981.4     .07       0  5024.1     .16       0
    5042      .1       0  5886.7     .05       0  5886.7     .16       0
  6058.6     .05       0  6079.4     .16       0  6339.6     .05       0
Bank Sta=4981.4,5030.8
XS Rating Curve= 0 ,0
Exp/Cntr=0.3,0.1

Type RM Length L Ch R = 1 ,22173   ,822,822,822
BEGIN DESCRIPTION:
UNT 1022 IN LATR 30.0
END DESCRIPTION:
XS GIS Cut Line= 4
      2955666.92     10119257.18      2954781.49     10119189.47
      2954484.62     10118975.92      2953958.62     10119272.78
#Sta/Elev= 30
    3855 1062.91  3859.1 1062.81  4064.1 1058.84    4098 1057.79  4124.2 1055.39
  4164.4  1053.4  4234.6 1050.88  4334.9 1048.53    4375 1049.69  4535.4 1047.96
  4585.6 1048.24  4605.6 1049.11  4665.8 1048.07  4771.4  1047.8  4792.8 1047.02
  4798.9  1047.7  4813.6 1047.52    4929 1043.77  4979.3 1044.69  4993.1 1042.47
    5000 1040.46  5029.7 1044.66  5035.8 1044.58  5056.7 1045.02  5106.3 1043.78
  5207.6 1043.63  5426.7 1045.27  5500.7 1046.66  5624.9 1047.16  5712.7 1050.14
#Mann= 6 ,-1 , 0
    3855     .16       0  3859.1      .1       0  4979.3     .07       0
  5035.8     .16       0  5035.8      .1       0  5426.7     .16       0
Bank Sta=4979.3,5029.7
XS Rating Curve= 0 ,0
Exp/Cntr=0.3,0.1

Type RM Length L Ch R = 1 ,21351   ,1547,1547,1547
BEGIN DESCRIPTION:
UNT 1022 IN LATR 29.0
END DESCRIPTION:
XS GIS Cut Line= 4
      2954859.64      10118517.6      2954375.24     10118418.63
      2954203.37     10118600.92      2953963.77     10119184.29
#Sta/Elev= 30
  4390.9 1043.76  4555.4 1043.18  4638.6 1040.65    4684 1040.09  4734.5 1040.87
  4739.6 1041.56  4748.6 1040.68  4759.5 1039.78  4790.2 1039.28  4907.7 1039.77
  4964.3 1037.45  4971.6 1038.73  4985.8 1040.04  4992.7  1038.4    4997 1035.92
  4999.7 1035.42  5006.8 1036.72  5014.1 1039.37    5021 1040.06  5134.3 1039.43
  5209.1 1040.62  5387.5 1041.87  5441.6 1044.81  5454.6 1042.57  5463.2 1042.33
  5522.6 1042.87  5538.9 1042.81  5579.9 1044.37    5647 1044.59  5766.5 1047.44
#Mann= 6 ,-1 , 0
  4390.9      .1       0  4748.6     .07       0  4985.8     .07       0
    5021     .07       0  5209.1      .1       0  5522.6     .16       0
Bank Sta=4739.6,5021
XS Rating Curve= 0 ,0
Exp/Cntr=0.3,0.1

Type RM Length L Ch R = 1 ,19804   ,797,797,797
BEGIN DESCRIPTION:
Mapping XS d75dfac4
END DESCRIPTION:
XS GIS Cut Line= 4
      2954620.01     10118045.36      2953408.23     10117694.67
      2953120.03     10117920.37      2952252.74     10118118.11
#Sta/Elev= 30
    3583 1037.42  3803.2 1036.49    3932 1034.71  4142.1 1034.34  4319.9  1032.8
    4467 1032.57  4500.7 1031.28  4605.6 1030.46    4670 1030.19  4771.5 1029.31
  4834.5 1029.51  4871.4 1027.52  4979.2 1030.42  4993.7 1028.96  5010.6  1030.2
  5093.1 1029.86  5113.9 1030.94  5136.3 1028.33  5142.9 1029.23  5186.2 1029.29
  5355.8 1033.37  5564.5 1042.47  5607.5 1046.06  5711.3 1051.47  5817.3 1057.28
  5875.8 1062.13  5950.6 1066.09  5981.4 1069.77    6002 1070.43  6100.1 1075.76
#Mann= 11 ,-1 , 0
    3583      .1       0  4142.1     .05       0  4319.9      .1       0
    4467     .05       0  4605.6      .1       0    4670     .05       0
  4771.5      .1       0  4979.2    .035       0  5010.6      .1       0
  5711.3      .1       0    6002     .05       0
Bank Sta=4979.2,5010.6
XS Rating Curve= 0 ,0
Exp/Cntr=0.3,0.1

Type RM Length L Ch R = 1 ,19007   ,1040,1040,1040
BEGIN DESCRIPTION:
UNT 1022 IN LATR 28.0
END DESCRIPTION:
XS GIS Cut Line= 4
      2954121.77     10117453.79      2953466.39     10117063.16
      2952845.73     10117058.82      2952161.75     10117344.54
#Sta/Elev= 30
  3955.7 1028.75  4161.1 1027.55  4449.5 1025.46  4541.6 1024.08  4607.9 1024.42
  4657.8 1022.03  4681.3 1024.47  4736.6 1023.68  4766.6 1024.77  4796.6 1024.28
  4836.6 1025.35  4846.6 1024.55    4975 1026.56  4976.6 1026.64  4996.6 1025.26
  5016.6 1026.57  5073.7 1026.02  5116.6 1025.43  5146.6 1026.46  5372.8 1037.88
  5470.3 1042.52  5494.1 1044.91  5700.9 1056.36  5753.9 1060.62    5860 1066.93
  5907.6 1071.72  5976.1 1075.03  5989.9 1074.84  6037.4 1077.56  6080.6 1079.84
#Mann= 10 ,-1 , 0
  3955.7     .05       0  4161.1      .1       0  4449.5      .1       0
  4976.6     .05       0  4976.6     .07       0  5016.6     .16       0
  5073.7      .1       0  5372.8     .05       0  5976.1      .1       0
  6037.4     .16       0
Bank Sta=4975,5016.6
XS Rating Curve= 0 ,0
Exp/Cntr=0.3,0.1

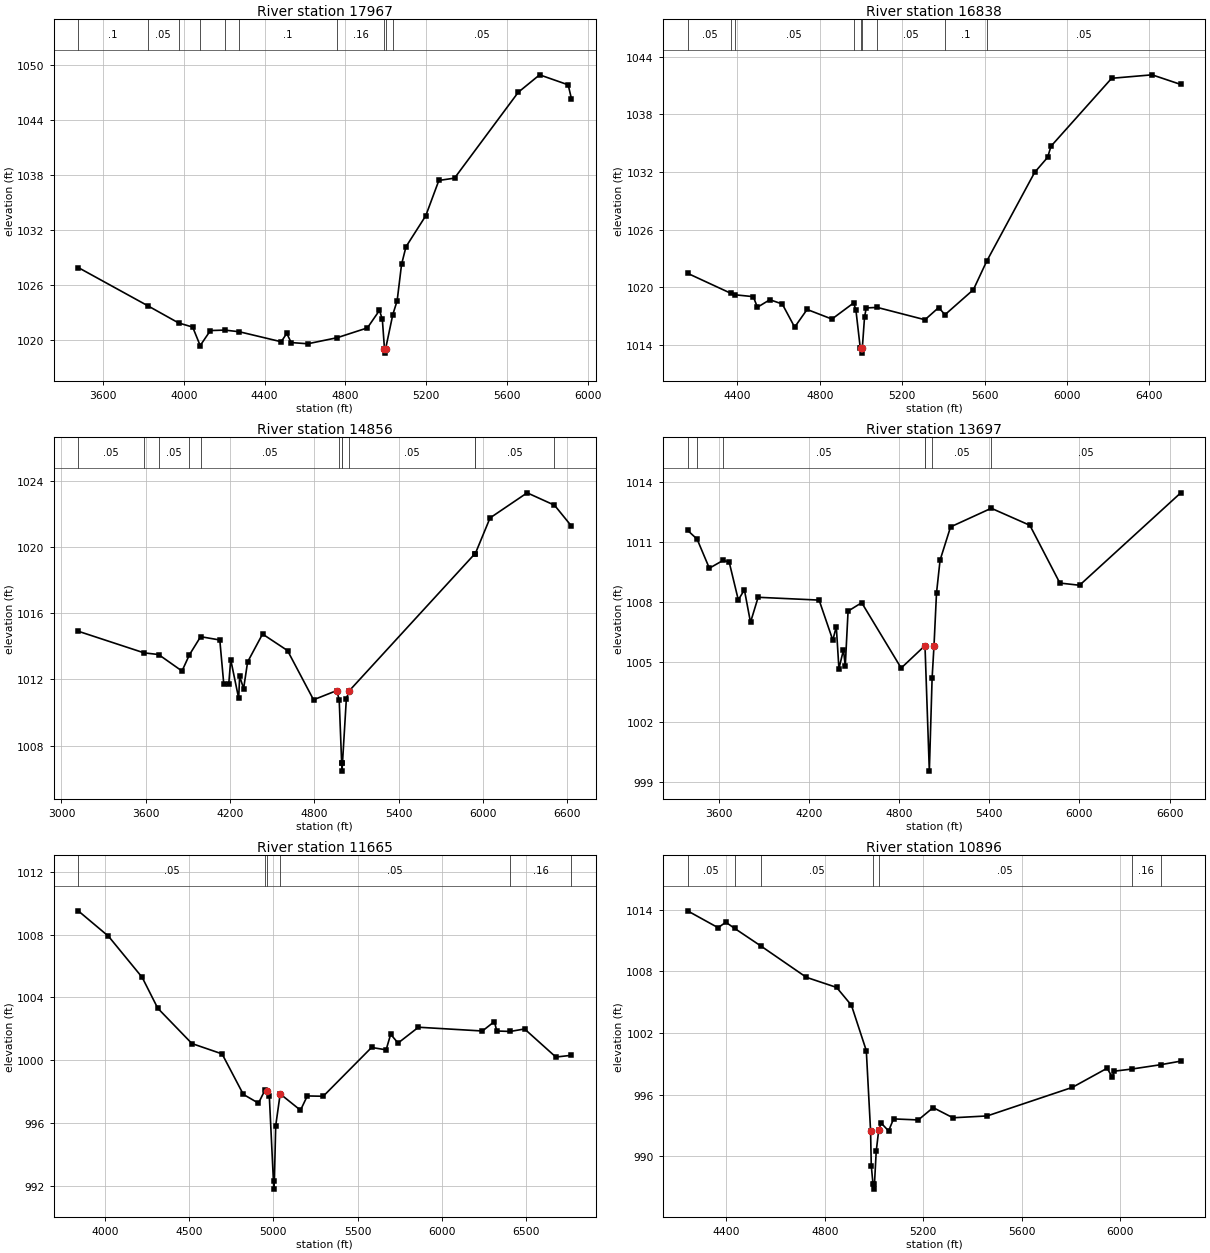
Type RM Length L Ch R = 1 ,17967   ,1129,1129,1129
BEGIN DESCRIPTION:
UNT 1022 IN LATR 27.0
END DESCRIPTION:
XS GIS Cut Line= 4
      2954000.24     10117319.23      2953418.64     10116234.17
      2952932.53     10115969.41      2952282.46     10116051.76
#Sta/Elev= 30
  3477.8 1027.88  3822.2 1023.71  3974.3 1021.84  4044.1 1021.39  4081.2 1019.37
  4131.8 1021.01  4202.6 1021.06  4274.7 1020.88  4481.9 1019.79  4509.5  1020.7
  4531.4  1019.7  4613.5 1019.57  4758.7 1020.23  4908.4  1021.3  4968.2 1023.21
  4982.4 1022.22  4992.8 1019.05  4995.5 1018.55  4998.8 1019.05  5034.1 1022.75
  5055.6 1024.26  5077.4 1028.22  5099.3 1030.14  5197.1 1033.52  5261.9 1037.37
  5339.4 1037.62  5654.8 1046.98  5760.4 1048.88  5901.6 1047.79  5917.7 1046.29
#Mann= 10 ,-1 , 0
  3477.8      .1       0  3822.2     .05       0  3974.3      .1       0
  4081.2     .05       0  4202.6     .16       0  4274.7      .1       0
  4758.7     .16       0  4992.8     .07       0  4998.8     .16       0
  5034.1     .05       0
Bank Sta=4992.8,4998.8
XS Rating Curve= 0 ,0
Exp/Cntr=0.3,0.1

Type RM Length L Ch R = 1 ,16838   ,1982,1982,1982
BEGIN DESCRIPTION:
UNT 1022 IN LATR 26.0
END DESCRIPTION:
XS GIS Cut Line= 4
      2954147.81      10116811.4      2954078.37     10116082.26
      2953700.76      10115795.8      2952554.92      10115483.3
#Sta/Elev= 30
  4158.2 1021.47  4370.3 1019.37  4386.3 1019.24  4477.3 1019.04  4497.4 1017.94
  4557.7 1018.72  4617.9 1018.28  4678.2 1015.87  4738.5 1017.71    4859 1016.71
  4964.7 1018.39  4975.7 1017.61  4996.5 1013.73  5000.5 1013.67  5003.2 1013.17
  5006.5 1013.67  5017.3  1016.9  5025.6 1017.87  5079.3 1017.92  5310.6 1016.64
  5377.4 1017.91  5407.7 1017.16  5545.9 1019.77    5610 1022.71  5843.1 1031.96
    5906 1033.52  5922.5 1034.68  6216.9 1041.74  6413.2  1042.1  6552.3  1041.1
#Mann= 9 ,-1 , 0
  4158.2     .05       0  4370.3      .1       0  4386.3     .05       0
  4964.7     .16       0  5000.5     .07       0  5006.5     .16       0
  5079.3     .05       0  5407.7      .1       0    5610     .05       0
Bank Sta=5000.5,5006.5
XS Rating Curve= 0 ,0
Exp/Cntr=0.3,0.1

Type RM Length L Ch R = 1 ,14856   ,1159,1159,1159
BEGIN DESCRIPTION:
Mapping XS dd6d307c
END DESCRIPTION:
XS GIS Cut Line= 4
       2955163.6     10116582.66      2954186.87     10115559.69
      2954051.46     10114788.86      2952784.34     10114448.65
#Sta/Elev= 30
  3119.2 1014.92    3588 1013.61    3691 1013.51  3857.7 1012.51  3910.2 1013.49
  3990.2 1014.59  4126.6 1014.39  4154.7 1011.74  4190.1  1011.7  4204.3  1013.2
  4260.9 1010.86  4267.8 1012.19  4296.1 1011.45  4324.4 1013.06  4430.7 1014.75
  4608.3 1013.75  4793.5 1010.77  4959.4 1011.33  4976.2 1010.74  4993.5 1006.95
  4996.3 1006.45  4999.5 1006.95    5027 1010.84  5047.3 1011.31  5941.4 1019.61
  5943.6  1019.6  6049.3 1021.78  6313.3  1023.3  6507.8 1022.55  6628.2 1021.29
#Mann= 12 ,-1 , 0
  3119.2     .05       0    3588      .1       0    3691     .05       0
  3910.2      .1       0  3990.2     .05       0  4976.2      .1       0
  4993.5     .07       0  4999.5      .1       0  5047.3     .05       0
  5941.4      .1       0  5943.6     .05       0  6507.8      .1       0
Bank Sta=4959.4,5047.3
XS Rating Curve= 0 ,0
Exp/Cntr=0.3,0.1

Type RM Length L Ch R = 1 ,13697   ,2032,2032,2032
BEGIN DESCRIPTION:
Mapping XS 6a16873a
END DESCRIPTION:
XS GIS Cut Line= 4
      2955172.12     10116236.82       2954933.4     10114858.74
      2954759.79     10114446.41      2953361.78     10114110.46
#Sta/Elev= 30
  3390.9 1011.57  3454.6 1011.13  3536.1 1009.68  3627.5 1010.07  3668.1 1009.99
  3728.9  1008.1  3769.5  1008.6  3810.1 1006.98  3860.9 1008.23  4266.9 1008.09
  4358.2 1006.09  4381.3 1006.77  4398.8 1004.67  4429.2 1005.61    4441  1004.8
  4459.7 1007.54  4550.4 1007.96  4813.2  1004.7  4971.8 1005.82  5000.8  999.56
  5019.3 1004.21 5031.82 1005.81  5048.5 1008.44  5072.2 1010.08  5142.1 1011.74
  5413.1 1012.67  5670.2 1011.82  5869.8 1008.94  6000.9 1008.83  6674.7 1013.44
#Mann= 7 ,-1 , 0
  3390.9      .1       0  3454.6     .05       0  3627.5     .05       0
  4971.8     .16       0  4971.8     .07       0  5019.3     .05       0
  5413.1     .05       0
#XS Ineff= 1 ,-1
 5423.99  6602.9 1011.24
Permanent Ineff=
       F
Bank Sta=4971.8,5031.82
XS Rating Curve= 0 ,0
Exp/Cntr=0.3,0.1

Type RM Length L Ch R = 1 ,11665   ,769,769,769
BEGIN DESCRIPTION:
UNT 1022 IN LATR 25.0
END DESCRIPTION:
XS GIS Cut Line= 4
      2955677.92     10116241.68       2956237.8      10115434.4
      2956363.67     10115039.44      2955449.55     10113812.86
#Sta/Elev= 30
  3842.2 1009.52  4021.8  1007.9  4221.7 1005.28  4314.3 1003.31  4516.9 1001.06
  4695.9  1000.4    4822  997.82  4911.8  997.26  4951.3  998.11  4961.8  998.06
  4976.3   997.7    5003  991.78  5006.2  992.28  5014.2  995.82  5040.7  997.85
  5161.2  996.81  5201.7  997.72  5296.2   997.7    5583 1000.81  5669.3 1000.66
  5696.4 1001.65  5740.2 1001.09  5861.1  1002.1  6240.7 1001.86  6311.6 1002.46
  6326.2 1001.86  6405.4 1001.83  6490.9 1001.99  6676.5  1000.2  6768.9 1000.31
#Mann= 6 ,-1 , 0
  3842.2     .05       0  4951.3     .16       0  4961.8     .07       0
  5040.7     .05       0  6405.4     .16       0  6768.9     .05       0
#Block Obstruct= 2 , 0
                         6153.05         1002.15
Bank Sta=4961.8,5040.7
XS Rating Curve= 0 ,0
Exp/Cntr=0.3,0.1

Type RM Length L Ch R = 1 ,10896   ,640,640,640
BEGIN DESCRIPTION:
UNT 1022 IN LATR 24.0
END DESCRIPTION:
XS GIS Cut Line= 4
      2956849.78     10116237.36      2956901.86      10115660.1
       2956841.1     10115130.58      2956220.66     10114488.45
#Sta/Elev= 30
  4241.6 1013.89  4365.7 1012.25  4397.4 1012.78  4432.6 1012.19  4539.2 1010.48
    4725 1007.42  4847.7 1006.44  4908.1  1004.7  4968.5 1000.29  4985.8  992.51
  4988.7   989.1  4995.7  987.32  4998.5  986.82  5001.7  987.32  5008.8   990.5
  5018.9  992.55  5028.9  993.25  5059.1  992.48  5079.3  993.65  5179.9  993.55
  5240.3  994.75  5320.8  993.76    5460  993.94  5806.5  996.72  5947.8  998.58
  5969.1  997.68  5976.1  998.29  6047.9   998.5  6164.9  998.92  6247.1  999.27
#Mann= 7 ,-1 , 0
  4241.6     .05       0  4432.6      .1       0  4539.2     .05       0
  4995.7     .07       0  5018.9     .05       0  6047.9     .16       0
  6164.9      .1       0
Bank Sta=4985.8,5018.9
XS Rating Curve= 0 ,0
Exp/Cntr=0.3,0.1

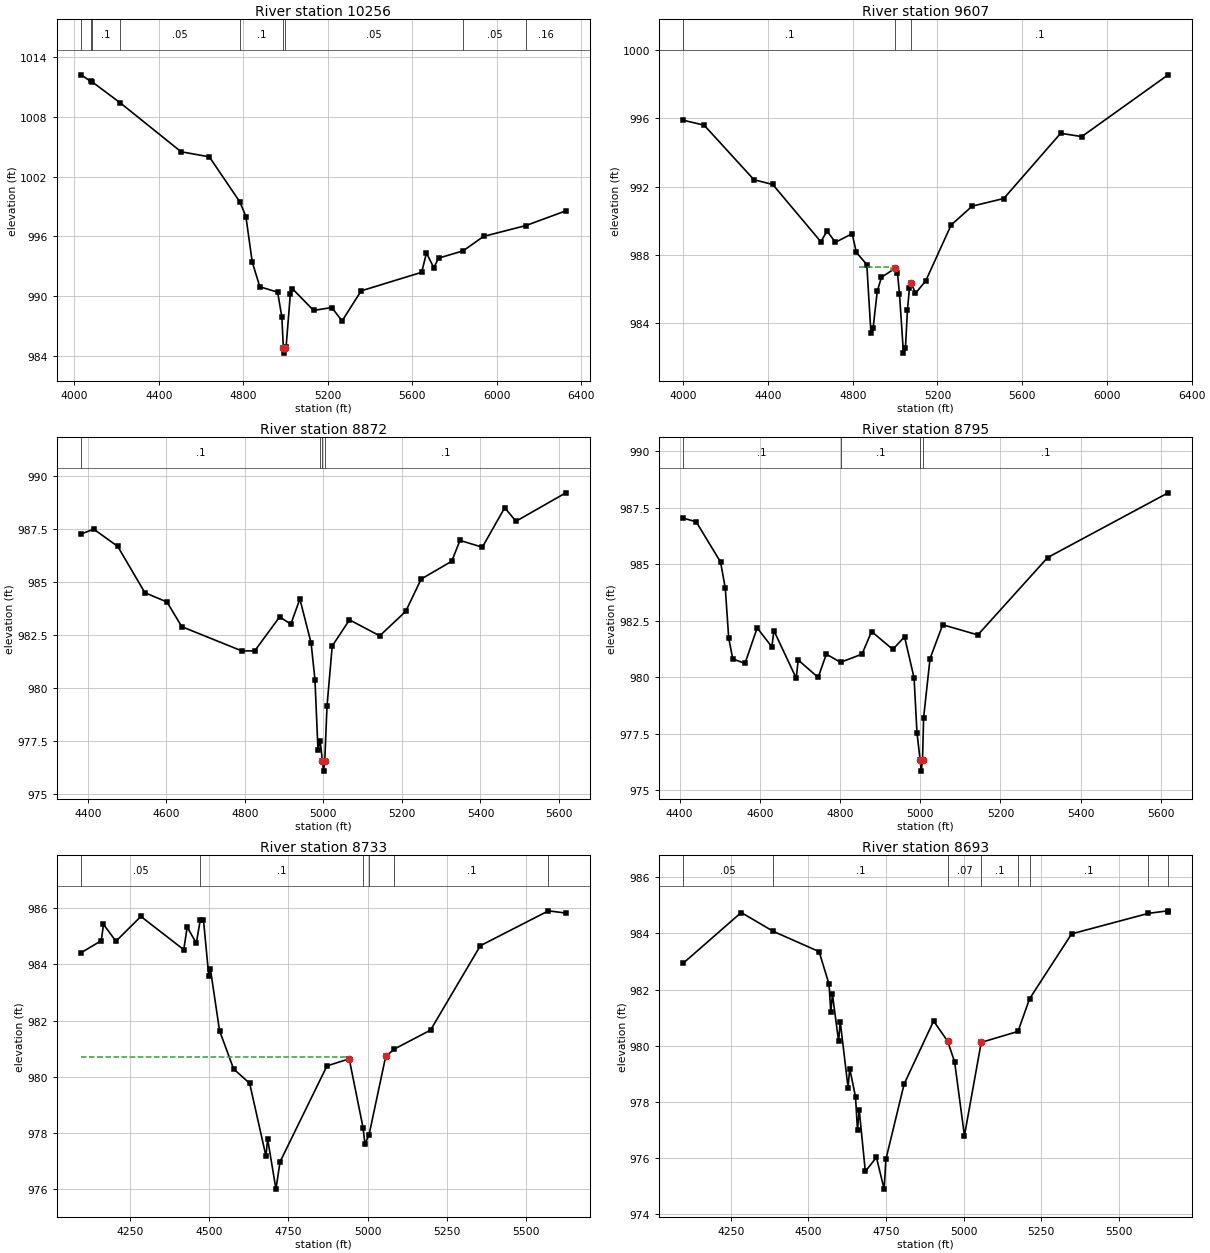
Type RM Length L Ch R = 1 ,10256   ,649,649,649
BEGIN DESCRIPTION:
UNT 1022 IN LATR 23.0
END DESCRIPTION:
XS GIS Cut Line= 4
      2957192.65     10116094.15      2957361.93     10115399.68
      2957335.89     10114991.69      2956312.51      10114419.3
#Sta/Elev= 30
  4031.9 1012.19    4078 1011.54  4083.5  1011.5  4218.3 1009.37  4505.8 1004.48
  4639.6 1003.97  4784.2  999.45  4812.8  997.99  4842.9  993.42  4878.8  990.95
  4963.1  990.41  4983.1  987.91  4990.2   984.8  4992.9   984.3  4996.2   984.8
  5003.2  984.92  5023.2   990.2  5032.4  990.77  5133.4  988.58  5219.3  988.87
  5268.4  987.53  5358.8  990.54  5645.3   992.4  5668.1  994.34  5702.6  992.86
  5725.5  993.82  5841.7  994.55  5938.7     996    6140  997.09  6328.1  998.56
#Mann= 9 ,-1 , 0
  4031.9     .05       0    4078     .16       0  4083.5      .1       0
  4218.3     .05       0  4784.2      .1       0  4990.2     .07       0
  4996.2     .05       0  5841.7     .05       0    6140     .16       0
Bank Sta=4990.2,4996.2
XS Rating Curve= 0 ,0
Exp/Cntr=0.3,0.1

Type RM Length L Ch R = 1 ,9607    ,735,735,735
BEGIN DESCRIPTION:
UNT 1022 IN LATR 22.0
END DESCRIPTION:
XS GIS Cut Line= 5
      2958405.58    10114668.788     2958019.103     10114565.66
       2957509.5      10114787.7      2957361.93     10114822.42
      2956276.84     10114340.64
#Sta/Elev= 30
    4000995.8934 4098.14995.6048 4333.66992.3969 4422.15992.1193 4649.12988.7584
 4678.72989.3802  4718.2988.7223 4797.14989.2286 4816.88988.1297 4866.22987.4138
 4885.95983.3698 4895.82983.6591 4915.56985.8404  4935.3986.6647 5001.66987.2074
 5011.07986.9222 5020.49 985.695 5039.32982.2109 5048.73982.5187 5058.15984.7548
 5067.56986.0193 5076.98986.3235 5095.81985.7194 5145.01986.4686 5264.36989.7388
 5363.82990.8466 5513.01991.2953 5781.56995.1277 5881.02994.9321 6288.81998.5618
#Mann= 3 , 0 , 0
    4000      .1       0 5001.66     .07       0 5076.98      .1       0
#XS Ineff= 1 ,-1
 4829.55 4978.69  987.29
Permanent Ineff=
       T
Bank Sta=5001.66,5076.98
XS Rating Curve= 0 ,0
Exp/Cntr=0.3,0.1

Type RM Length L Ch R = 1 ,8872    ,77,77,77
BEGIN DESCRIPTION:
UNT 1022 IN LATR 21.0
END DESCRIPTION:
XS GIS Cut Line= 4
      2958150.11     10114136.66      2957741.27     10114217.39
      2957337.63     10114032.49      2957054.33     10113788.18
#Sta/Elev= 30
  4382.6  987.25  4414.9  987.48    4476  986.67  4545.2  984.49  4601.6  984.05
  4639.1  982.89    4792  981.75    4825  981.75  4888.5  983.35    4917  983.01
    4940  984.19  4968.6  982.12  4978.4   980.4  4986.1   977.1  4991.6  977.52
  4997.4  976.59  5000.2  976.09  5003.4  976.59  5009.1  979.14  5022.4  981.98
  5066.4  983.21  5143.4  982.46  5209.6  983.61  5248.9  985.13  5326.8  985.97
  5347.8  986.95  5404.7  986.63  5461.8  988.49  5490.3  987.85  5617.4  989.19
#Mann= 4 ,-1 , 0
  4382.6      .1       0  4991.6     .05       0  4997.4    .035       0
  5003.4      .1       0
Bank Sta=4997.4,5003.4
XS Rating Curve= 0 ,0
Exp/Cntr=0.3,0.1

Type RM Length L Ch R = 1 ,8795    ,62,62,62
BEGIN DESCRIPTION:
UNT 1022 IN LATR 20.0
END DESCRIPTION:
XS GIS Cut Line= 4
       2958150.1     10114081.98      2957777.73     10114144.47
      2957329.81     10113956.97      2957093.12     10113704.67
#Sta/Elev= 30
  4409.2  987.03  4441.3  986.87  4502.1  985.09  4513.9  983.93  4522.4  981.73
  4532.5  980.81    4563  980.61  4593.4  982.18  4630.1  981.34  4635.1  982.06
  4690.7  979.96  4695.8  980.76  4745.5  979.99  4765.8  981.02  4801.3  980.66
  4854.9  981.02  4878.7  982.02  4931.7  981.23  4960.9  981.79  4984.7  979.97
    4992  977.54  4999.8  976.35  5002.5  975.85  5005.8  976.35  5008.5  978.21
  5024.5  980.82  5056.1  982.32  5143.7  981.87  5317.9  985.29  5618.3  988.15
#Mann= 4 ,-1 , 0
  4409.2      .1       0  4801.3      .1       0  4999.8    .035       0
  5005.8      .1       0
Bank Sta=4999.8,5005.8
XS Rating Curve= 0 ,0
Exp/Cntr=0.3,0.1

Type RM Length L Ch R = 1 ,8733    ,40,40,40
BEGIN DESCRIPTION:
UNT 1022 IN LATR 19.0
END DESCRIPTION:
XS GIS Cut Line= 5
      2958500.06     10113849.08       2957887.1     10114022.08
       2957637.1     10114024.68      2957423.56     10113907.49
      2957183.99     10113589.79
#Sta/Elev= 30
  4096.1  984.41  4160.1  984.84  4166.9  985.42  4206.1  984.82  4284.8   985.7
  4419.9  984.52  4430.8  985.32  4459.6  984.75    4472  985.58  4482.2  985.57
  4498.8  983.59    4504  983.83  4532.8  981.64  4577.2  980.28  4627.7  979.77
  4679.2  977.18  4684.3   977.8  4710.6  976.01  4723.5  976.98  4871.6  980.39
  4941.6  980.64  4985.1   978.2  4991.3  977.61  5004.3  977.95  5056.7  980.73
  5084.2  980.99  5197.9  981.66    5355  984.66  5569.7   985.9  5624.5  985.82
#Mann= 6 ,-1 , 0
  4096.1     .05       0    4472      .1       0  4985.1    .035       0
  5004.3     .05       0  5084.2      .1       0  5569.7     .05       0
#XS Ineff= 2 , 0
         4931.08  980.72
Permanent Ineff=
       F       F
Bank Sta=4941.6,5056.7
XS Rating Curve= 0 ,0
Exp/Cntr=0.3,0.1

Type RM Length L Ch R = 1 ,8693    ,835,835,835
BEGIN DESCRIPTION:
Mapping XS 2c1017b2
END DESCRIPTION:
XS GIS Cut Line= 5
      2958508.74     10113764.44       2957887.1     10113993.43
      2957676.17     10114001.24      2957457.42     10113881.45
      2957228.95     10113507.59
#Sta/Elev= 30
  4097.1  982.94  4283.5  984.74  4386.8  984.07  4534.3  983.35  4566.3  982.19
    4572  981.19  4577.3  981.83  4597.1  980.16  4602.5  980.85  4627.6  978.51
  4632.9  979.19  4651.6  978.18    4658  976.99  4663.4  977.73  4683.2  975.53
  4718.9  976.03  4743.8   974.9  4749.4  975.96  4808.2  978.64  4903.1  980.88
  4948.3  980.16  4970.7  979.43  5002.3   976.8  5056.4  980.12  5174.8  980.51
    5212  981.67  5347.4  983.98  5594.9  984.71  5657.1   984.8  5658.2  984.77
#Mann= 8 ,-1 , 0
  4097.1     .05       0  4386.8      .1       0  4948.3     .07       0
  5056.4      .1       0  5174.8     .05       0    5212      .1       0
  5594.9     .16       0  5657.1      .1       0
#XS Ineff= 2 , 0
         4906.52  980.72
Permanent Ineff=
       F       F
#Block Obstruct= 2 , 0
         4306.15  984.37
Bank Sta=4948.3,5056.4
XS Rating Curve= 0 ,0
Exp/Cntr=0.3,0.1

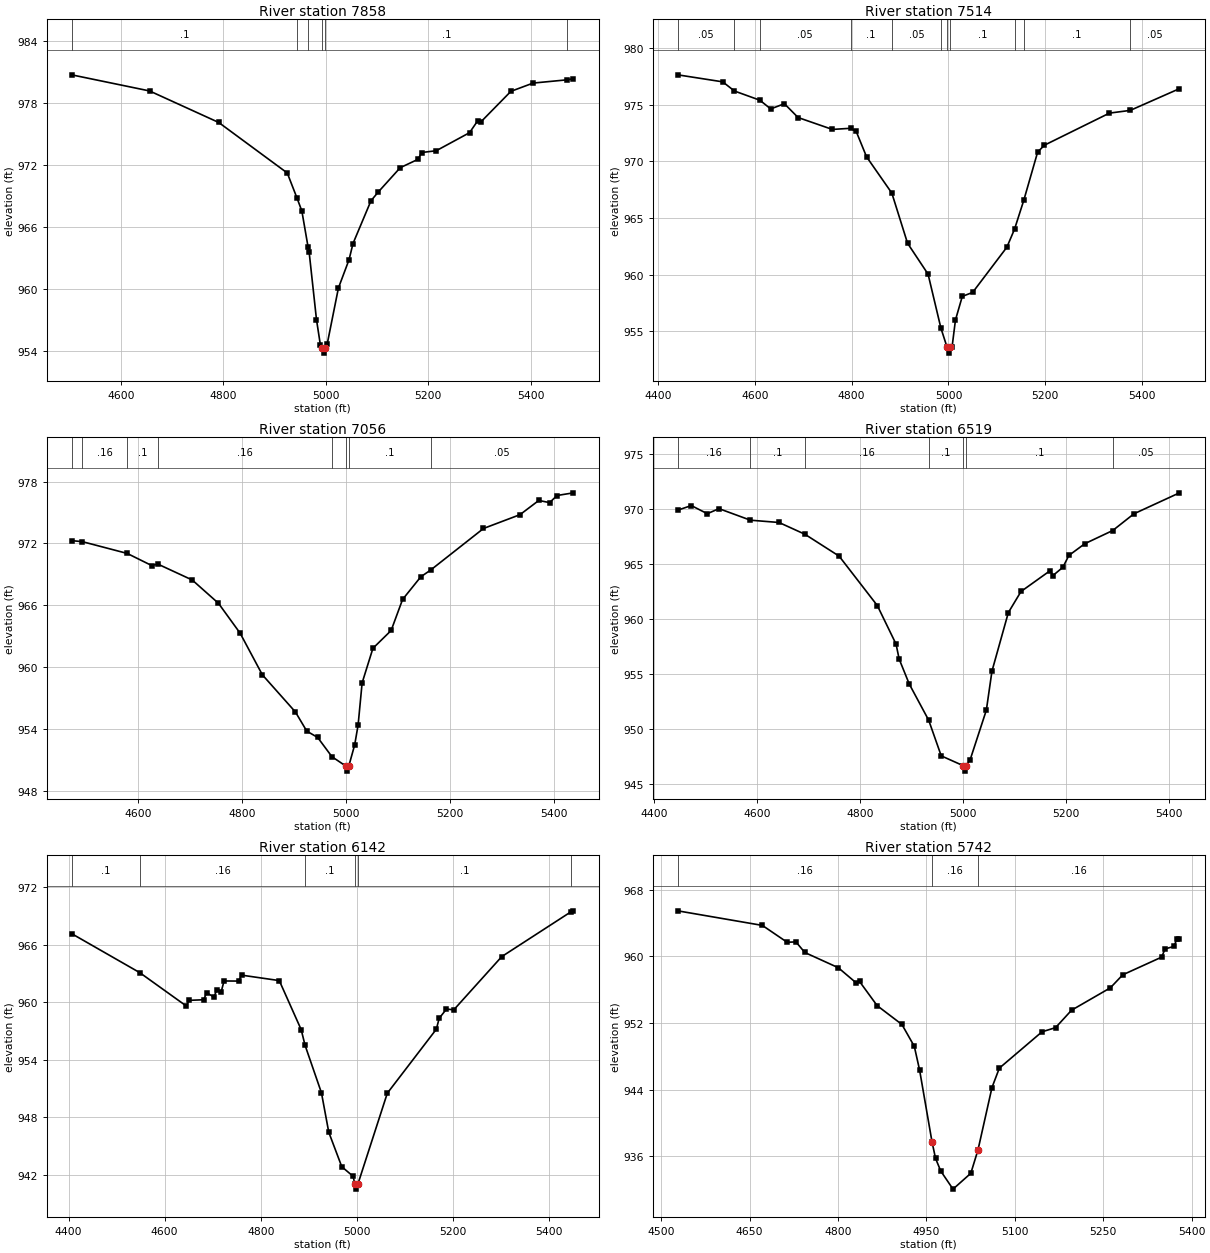
Type RM Length L Ch R = 1 ,7858    ,344,344,344
BEGIN DESCRIPTION:
UNT 1022 IN LATR 18.0
END DESCRIPTION:
XS GIS Cut Line= 3
      2958517.31     10113639.26      2957952.21     10113154.89
      2957747.39     10113038.22
#Sta/Elev= 30
  4503.7  980.73  4655.9  979.17  4790.9  976.12  4924.8  971.23    4944  968.78
  4953.3  967.55  4965.6  964.02  4967.6  963.54  4981.9  957.03  4989.5  954.58
  4993.2  954.29  4995.9  953.79  4999.2  954.29  5002.7  954.64  5024.7  960.09
  5045.5  962.84  5053.2   964.4  5088.3  968.54  5102.6  969.39  5145.4  971.74
  5180.5  972.56  5187.1  973.21  5215.7  973.38  5280.8  975.13  5296.7  976.28
  5302.5  976.15  5361.5  979.13  5404.8  979.93    5472  980.25  5483.7  980.36
#Mann= 6 ,-1 , 0
  4503.7      .1       0    4944     .05       0  4965.6      .1       0
  4993.2     .07       0  4999.2      .1       0    5472     .05       0
Bank Sta=4993.2,4999.2
XS Rating Curve= 0 ,0
Exp/Cntr=0.3,0.1

Type RM Length L Ch R = 1 ,7514    ,458,458,458
BEGIN DESCRIPTION:
UNT 1022 IN LATR 17.0
END DESCRIPTION:
XS GIS Cut Line= 2
      2958717.81     10113436.11      2957999.07     10112688.73
#Sta/Elev= 30
  4440.5  977.65  4533.6  977.03  4557.8  976.22  4610.3  975.41  4632.7  974.64
    4661   975.1  4689.3  973.88  4760.1  972.83  4797.7  972.93  4809.4  972.65
  4830.8  970.41    4883  967.21  4915.5  962.78  4957.9  960.05  4984.4  955.29
  4997.3  953.58  5000.1  953.08  5003.3  953.58  5007.5  953.63  5014.5  956.01
  5028.6  958.09    5050  958.44  5120.7  962.43  5136.6  964.03  5155.7  966.58
  5184.3  970.83  5198.4  971.44  5332.7  974.27  5375.6  974.51  5477.4  976.43
#Mann= 11 ,-1 , 0
  4440.5     .05       0  4557.8     .16       0  4610.3     .05       0
  4797.7      .1       0    4883     .05       0  4984.4      .1       0
  4997.3     .07       0  5003.3      .1       0  5136.6     .16       0
  5155.7      .1       0  5375.6     .05       0
Bank Sta=4997.3,5003.3
XS Rating Curve= 0 ,0
Exp/Cntr=0.3,0.1

Type RM Length L Ch R = 1 ,7056    ,537,537,537
BEGIN DESCRIPTION:
UNT 1022 IN LATR 16.0
END DESCRIPTION:
XS GIS Cut Line= 2
       2959001.7     10113118.44      2958372.48     10112385.22
#Sta/Elev= 30
  4471.9  972.27  4492.6  972.17  4578.8  971.03  4626.2  969.85  4637.6     970
  4704.1  968.45  4754.6  966.19  4796.3  963.29  4839.1  959.25  4902.8  955.64
  4924.7  953.78  4945.6  953.17  4973.1   951.3  4999.6   950.4  5002.4   949.9
  5005.6   950.4  5016.9  952.45  5023.5  954.38  5031.2  958.46    5052  961.82
  5087.1  963.55  5109.1  966.56  5144.2  968.76  5163.3  969.42  5264.9  973.45
  5335.2  974.79  5371.4  976.17  5392.2  975.96  5406.5  976.65  5438.1  976.91
#Mann= 8 ,-1 , 0
  4471.9      .1       0  4492.6     .16       0  4578.8      .1       0
  4637.6     .16       0  4973.1      .1       0  4999.6     .07       0
  5005.6      .1       0  5163.3     .05       0
Bank Sta=4999.6,5005.6
XS Rating Curve= 0 ,0
Exp/Cntr=0.3,0.1

Type RM Length L Ch R = 1 ,6519    ,377,377,377
BEGIN DESCRIPTION:
UNT 1022 IN LATR 15.0
END DESCRIPTION:
XS GIS Cut Line= 2
      2959303.76     10113019.43      2958980.85     10112100.19
#Sta/Elev= 30
  4445.6  969.91  4472.1  970.33  4503.1  969.59  4525.8  970.05  4586.8     969
  4642.4  968.79  4692.6  967.72    4759  965.73  4833.2  961.23  4869.6  957.72
  4875.6  956.36  4895.3  954.08    4933  950.79  4957.3  947.55  4999.8  946.66
  5002.5  946.16  5005.8  946.66  5013.4  947.19  5044.9  951.71  5055.8  955.26
  5087.6  960.59  5112.2  962.51  5168.9  964.41  5174.2  963.96  5193.6  964.72
  5205.1  965.79  5236.1  966.86  5290.3  968.06  5331.4  969.58  5419.9  971.49
#Mann= 7 ,-1 , 0
  4445.6     .16       0  4586.8      .1       0  4692.6     .16       0
    4933      .1       0  4999.8     .07       0  5005.8      .1       0
  5290.3     .05       0
Bank Sta=4999.8,5005.8
XS Rating Curve= 0 ,0
Exp/Cntr=0.3,0.1

Type RM Length L Ch R = 1 ,6142    ,400,400,400
BEGIN DESCRIPTION:
UNT 1022 IN LATR 14.0
END DESCRIPTION:
XS GIS Cut Line= 2
      2959754.27     10112826.73      2959189.87     10111947.61
#Sta/Elev= 30
  4406.3  967.16  4548.1  963.09    4645  959.61  4650.9   960.2  4681.3  960.26
  4687.3     961  4702.5  960.54  4708.4  961.27  4717.7   961.1  4723.6  962.22
    4754  962.21    4760  962.83  4838.6  962.26  4884.2  957.14  4892.2  955.52
  4926.4  950.55  4941.6  946.44  4968.7  942.84  4992.2  941.84  4996.1     941
  4998.8   940.5  5002.1     941  5063.5  950.51  5165.6  957.19  5171.5  958.33
  5186.7  959.29  5201.9  959.21  5301.7  964.76  5445.3  969.42    5451  969.54
#Mann= 6 ,-1 , 0
  4406.3      .1       0  4548.1     .16       0  4892.2      .1       0
  4996.1     .07       0  5002.1      .1       0  5445.3     .05       0
Bank Sta=4996.1,5002.1
XS Rating Curve= 0 ,0
Exp/Cntr=0.3,0.1

Type RM Length L Ch R = 1 ,5742    ,455,455,455
BEGIN DESCRIPTION:
UNT 1022 IN LATR 13.0
END DESCRIPTION:
XS GIS Cut Line= 2
      2960025.12     10112496.02      2959548.59     10111790.35
#Sta/Elev= 30
  4527.9  965.45  4671.6   963.7  4713.6  961.68  4728.6  961.72  4743.6  960.45
  4800.5  958.62  4830.5  956.82  4836.5  956.97  4866.4  954.07  4908.4  951.81
  4929.4  949.19  4938.4  946.34  4959.4  937.75  4965.4  935.75  4974.3  934.22
  4995.1  932.05  5025.3  933.95  5037.5  936.76  5061.2  944.24  5073.7  946.57
  5146.1  950.93  5169.1  951.43  5196.2  953.52  5262.1  956.21  5283.1  957.77
    5349  959.89    5355  960.88    5370  961.18  5375.1  962.08  5379.4  962.08
#Mann= 3 , 0 , 0
  4527.9     .16       0  4959.4     .16       0  5037.5     .16       0
Bank Sta=4959.4,5037.5
XS Rating Curve= 0 ,0
Exp/Cntr=0.3,0.1