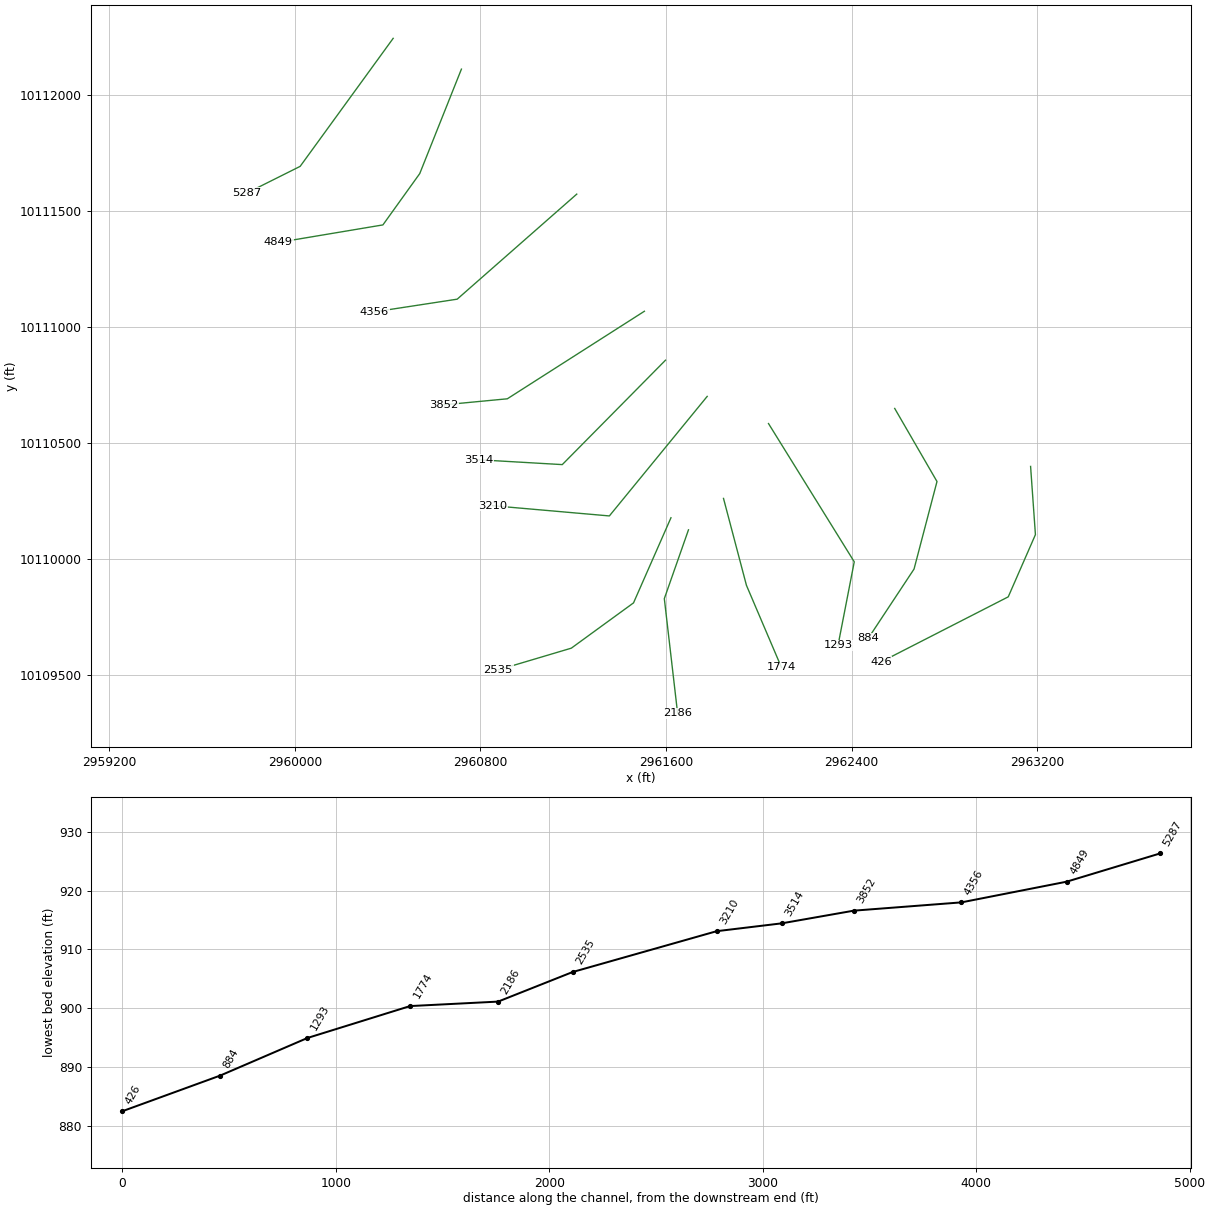
HEC-RAS study UNT 0022 IN LATR.prj: UNT 1022 IN LATR Base Level Engineering

--- UNT 0022 IN LATR.g01 (geometry) --- (continued)

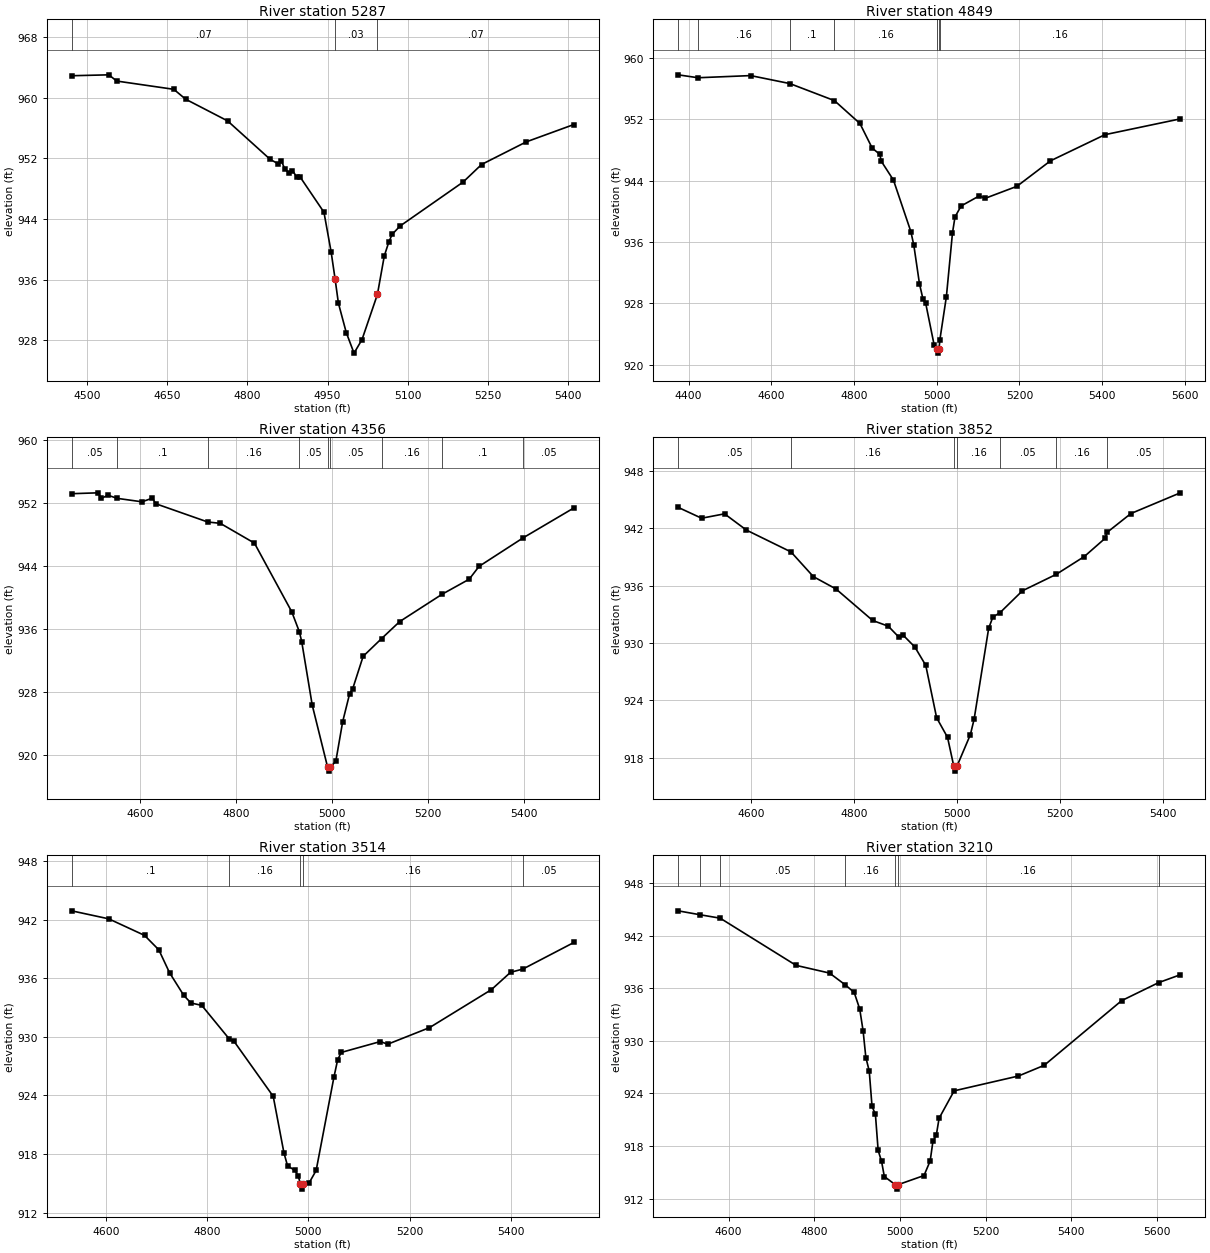
Type RM Length L Ch R = 1 ,5287    ,438,438,438
BEGIN DESCRIPTION:
UNT 1022 IN LATR 12.0
END DESCRIPTION:
XS GIS Cut Line= 3
      2960423.57     10112246.05      2960022.52     10111693.95
      2959793.45     10111579.41
#Sta/Elev= 30
  4471.8  962.88  4541.3     963    4556  962.18  4662.7  961.09  4684.8  959.79
  4763.2  956.93  4842.8  951.86  4857.5  951.28  4863.7  951.66  4870.2  950.58
  4878.4  950.07  4884.5  950.39    4893  949.47  4899.2  949.49  4943.3  944.89
  4956.7  939.67  4964.1   936.1  4970.3  932.91    4985  929.03  4999.5  926.32
  5014.4   928.1  5043.2  934.05  5056.1  939.14  5064.6  940.98  5070.8  941.98
  5085.5  943.07  5203.4  948.87  5237.8  951.18  5321.6  954.17  5410.3  956.45
#Mann= 3 , 0 , 0
  4471.8     .07       0  4964.1     .03       0  5043.2     .07       0
Bank Sta=4964.1,5043.2
XS Rating Curve= 0 ,0
Exp/Cntr=0.3,0.1

Type RM Length L Ch R = 1 ,4849    ,493,493,493
BEGIN DESCRIPTION:
UNT 1022 IN LATR 11.0
END DESCRIPTION:
XS GIS Cut Line= 4
      2960717.83     10112113.21      2960538.15      10111662.7
      2960379.29     10111441.35      2959928.76     10111365.82
#Sta/Elev= 30
  4374.7  957.78  4422.9   957.4  4550.1  957.68  4644.9  956.64  4752.6  954.42
  4814.3  951.44  4843.9  948.24  4862.2  947.42  4866.2   946.5  4895.4  944.06
  4937.4  937.36  4944.6  935.59  4958.3  930.55  4966.9  928.52    4973   928.1
  4993.9  922.54  4999.5  922.01  5002.2  921.51  5005.5  922.01  5007.7  923.28
  5023.4  928.88  5038.1  937.17  5044.2  939.26    5059  940.69  5103.2  942.01
  5116.9  941.68  5193.9  943.25    5275  946.57  5406.8  949.98    5589  952.04
#Mann= 7 ,-1 , 0
  4374.7      .1       0  4422.9     .16       0  4644.9      .1       0
  4752.6     .16       0  4999.5     .07       0  5005.5     .16       0
  5007.7     .16       0
Bank Sta=4999.5,5005.5
XS Rating Curve= 0 ,0
Exp/Cntr=0.3,0.1

Type RM Length L Ch R = 1 ,4356    ,504,504,504
BEGIN DESCRIPTION:
UNT 1022 IN LATR 10.0
END DESCRIPTION:
XS GIS Cut Line= 3
      2961215.25     10111574.18       2960699.6     10111121.03
      2960343.13     10111066.39
#Sta/Elev= 30
  4457.3  953.19    4512   953.3  4519.5   952.6  4532.9     953  4552.1   952.6
    4604  952.16  4625.8  952.63  4632.5  951.92    4741   949.6  4767.2  949.43
  4838.4  946.92  4916.2  938.21  4932.1  935.67    4937  934.42  4958.9  926.37
    4991  918.49  4993.7  917.99    4997  918.49  5008.2  919.27  5022.4  924.26
  5036.7  927.76  5043.3  928.44  5065.1  932.56  5103.4   934.8  5141.2  936.96
  5229.9  940.44  5286.2  942.34  5306.8  943.97    5399   947.6  5504.4  951.38
#Mann= 9 ,-1 , 0
  4457.3     .05       0  4552.1      .1       0    4741     .16       0
  4932.1     .05       0    4991    .035       0    4997     .05       0
  5103.4     .16       0  5229.9      .1       0    5399     .05       0
Bank Sta=4991,4997
XS Rating Curve= 0 ,0
Exp/Cntr=0.3,0.1

Type RM Length L Ch R = 1 ,3852    ,338,338,338
BEGIN DESCRIPTION:
UNT 1022 IN LATR 9.0
END DESCRIPTION:
XS GIS Cut Line= 3
      2961506.93     10111068.97      2960915.75     10110691.35
      2960642.88     10110665.36
#Sta/Elev= 30
  4458.5  944.21  4504.1  943.07  4548.7  943.53  4591.1  941.83  4677.8  939.54
  4721.3  936.95  4765.2  935.66  4836.4  932.36  4866.8  931.76    4888  930.58
  4895.7  930.82  4918.4  929.58  4939.6  927.66  4960.7  922.17  4981.9  920.12
  4994.1  917.08  4996.9  916.58  5000.1  917.08  5026.2  920.39  5033.5  922.01
  5061.8  931.54  5069.9  932.71  5084.1  933.19  5127.4  935.47    5193  937.19
  5247.7  939.06  5287.9  940.96  5291.7  941.58  5338.1  943.56  5434.1  945.73
#Mann= 7 ,-1 , 0
  4458.5     .05       0  4677.8     .16       0  4994.1     .07       0
  5000.1     .16       0  5084.1     .05       0    5193     .16       0
  5291.7     .05       0
Bank Sta=4994.1,5000.1
XS Rating Curve= 0 ,0
Exp/Cntr=0.3,0.1

Type RM Length L Ch R = 1 ,3514    ,304,304,304
BEGIN DESCRIPTION:
UNT 1022 IN LATR 8.0
END DESCRIPTION:
XS GIS Cut Line= 3
      2961598.01     10110857.98      2961152.73     10110407.49
      2960793.45     10110428.32
#Sta/Elev= 30
  4531.7  942.89  4605.1  942.07  4675.8  940.38  4704.1   938.9  4725.3  936.56
  4753.6  934.23  4767.7  933.46    4789  933.22  4843.8  929.76  4852.6  929.56
  4930.4  923.91  4951.6  918.13  4958.7  916.81  4972.8  916.35  4979.9   915.8
    4984  914.92  4986.7  914.42    4990  914.92  5001.1  915.03  5015.3  916.33
  5050.6  925.91  5057.7  927.62  5064.7   928.4  5142.5  929.52  5156.6  929.24
  5239.5  930.94    5362  934.83  5399.8   936.6  5424.1  936.93    5525  939.65
#Mann= 5 ,-1 , 0
  4531.7      .1       0  4843.8     .16       0    4984     .07       0
    4990     .16       0  5424.1     .05       0
Bank Sta=4984,4990
XS Rating Curve= 0 ,0
Exp/Cntr=0.3,0.1

Type RM Length L Ch R = 1 ,3210    ,675,675,675
BEGIN DESCRIPTION:
UNT 1022 IN LATR 7.0
END DESCRIPTION:
XS GIS Cut Line= 3
      2961777.71     10110701.74      2961355.85     10110186.14
      2960852.07     10110230.28
#Sta/Elev= 30
  4482.4  944.83  4532.7  944.39  4580.6  943.99  4757.6  938.61  4835.8  937.73
  4872.9  936.37  4893.3  935.52  4906.2  933.63  4914.1  931.13  4920.5   928.1
  4928.4  926.56  4934.9  922.53  4942.8  921.62  4949.2   917.5  4957.1  916.27
  4963.6  914.53  4989.3  913.59  4992.1  913.09  4995.3  913.59  5056.2  914.64
  5070.6  916.31    5077  918.53  5084.9  919.25  5091.4  921.17  5126.5   924.3
  5276.5  925.99  5336.7  927.21  5517.2  934.58  5603.6  936.64  5654.3  937.54
#Mann= 7 ,-1 , 0
  4482.4     .05       0  4532.7      .1       0  4580.6     .05       0
  4872.9     .16       0  4989.3     .07       0  4995.3     .16       0
  5603.6     .05       0
Bank Sta=4989.3,4995.3
XS Rating Curve= 0 ,0
Exp/Cntr=0.3,0.1

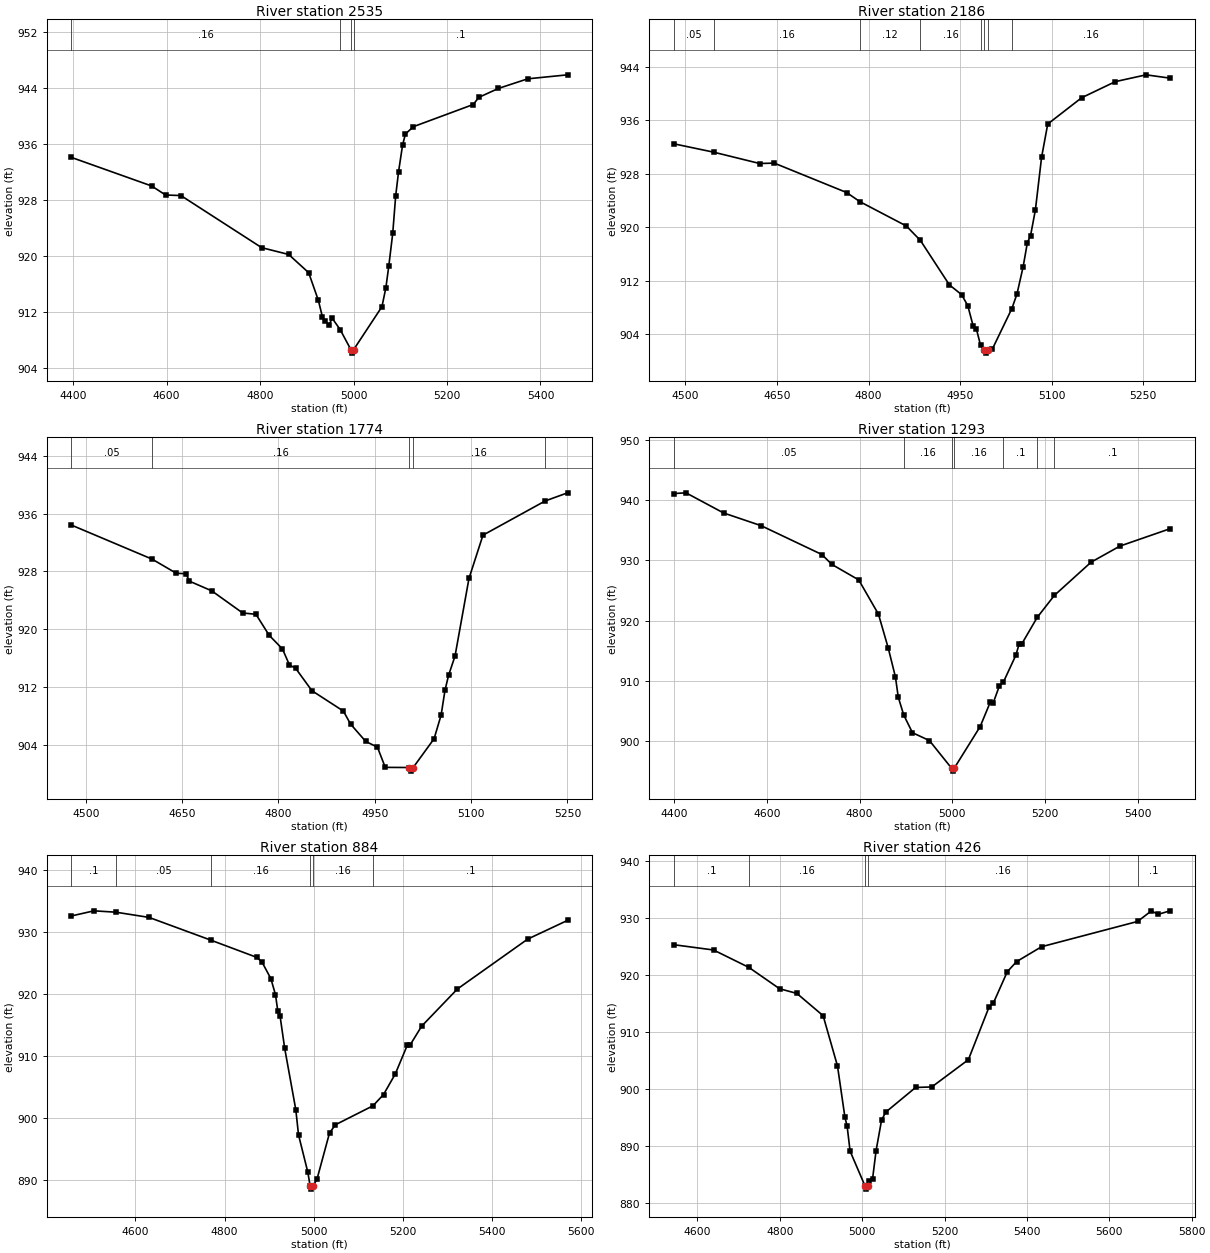
Type RM Length L Ch R = 1 ,2535    ,349,349,349
BEGIN DESCRIPTION:
UNT 1022 IN LATR 6.0
END DESCRIPTION:
XS GIS Cut Line= 4
      2961621.48     10110178.32      2961460.02     10109811.14
      2961191.79     10109615.83      2960876.66     10109522.07
#Sta/Elev= 30
  4396.3  934.09    4568  930.01  4597.9  928.72  4630.7  928.64  4803.5   921.2
  4861.2  920.23    4904  917.63  4924.8  913.67  4933.3  911.35  4939.5   910.7
  4947.8  910.17  4954.2  911.14  4971.5  909.49  4994.3  906.64    4997  906.14
  5000.3  906.64  5060.8  912.77  5069.3  915.51  5075.5   918.6  5083.9  923.25
  5090.2   928.6  5096.4  932.07  5104.9  935.83    5111  937.43  5128.2  938.48
    5256  941.64  5268.3  942.67  5310.1  943.94  5372.7  945.31    5458  945.88
#Mann= 4 ,-1 , 0
  4396.3     .16       0  4971.5      .1       0  4994.3     .07       0
  5000.3      .1       0
Bank Sta=4994.3,5000.3
XS Rating Curve= 0 ,0
Exp/Cntr=0.3,0.1

Type RM Length L Ch R = 1 ,2186    ,412,412,412
BEGIN DESCRIPTION:
UNT 1022 IN LATR 5.0
END DESCRIPTION:
XS GIS Cut Line= 3
      2961696.98      10110126.2      2961592.83     10109829.37
      2961650.13     10109334.55
#Sta/Elev= 30
  4481.2   932.5  4546.3  931.25  4621.6  929.55  4645.5  929.61  4764.2  925.19
  4785.7  923.83  4861.8  920.18  4884.9  918.01  4932.3  911.35  4952.4  909.88
  4962.5  908.22  4971.3  905.17  4976.4  904.78  4983.4   902.3  4989.7  901.61
  4992.5  901.11  4995.7  901.61  5002.8  901.74  5034.7   907.8    5043  909.97
  5053.1  914.05  5060.1   917.7  5065.2  918.71  5073.2  922.59  5083.3  930.47
  5093.4  935.47  5148.9  939.41  5204.1  941.83  5254.5  942.85  5293.9  942.35
#Mann= 8 ,-1 , 0
  4481.2     .05       0  4546.3     .16       0  4785.7     .12       0
  4884.9     .16       0  4983.4     .12       0  4989.7     .07       0
  4995.7     .12       0  5034.7     .16       0
Bank Sta=4989.7,4995.7
XS Rating Curve= 0 ,0
Exp/Cntr=0.3,0.1

Type RM Length L Ch R = 1 ,1774    ,481,481,481
BEGIN DESCRIPTION:
UNT 1022 IN LATR 4.0
END DESCRIPTION:
XS GIS Cut Line= 3
      2961848.04     10110261.68        2961947.     10109886.66
      2962098.05     10109532.48
#Sta/Elev= 30
  4477.4  934.41  4603.2  929.69  4640.8  927.74  4655.9  927.67  4661.4  926.64
  4696.1   925.3  4744.2  922.24  4764.9  922.06  4785.5  919.15  4806.2  917.26
    4817  915.06  4826.9  914.56  4852.1  911.48  4901.1  908.66  4912.3  906.86
  4935.9  904.46  4954.1  903.67  4966.3  900.87  5003.8  900.85  5006.5  900.35
  5009.8  900.85  5042.4  904.84  5053.3  908.11  5059.4  911.57  5064.9   913.6
    5075  916.29  5096.7  927.02  5118.5  933.01  5215.5  937.75  5250.3  938.87
#Mann= 5 ,-1 , 0
  4477.4     .05       0  4603.2     .16       0  5003.8     .07       0
  5009.8     .16       0  5215.5      .1       0
Bank Sta=5003.8,5009.8
XS Rating Curve= 0 ,0
Exp/Cntr=0.3,0.1

Type RM Length L Ch R = 1 ,1293    ,409,409,409
BEGIN DESCRIPTION:
UNT 1022 IN LATR 3.0
END DESCRIPTION:
XS GIS Cut Line= 3
      2962042.06     10110584.57      2962411.84     10109988.22
      2962341.77     10109627.46
#Sta/Elev= 30
  4400.1  941.14  4426.1  941.26    4507  937.91    4588  935.79  4718.8  930.99
  4740.4  929.34  4798.3  926.76  4840.8  921.05    4862  915.38  4877.4  910.59
  4883.5  907.22  4895.3  904.26    4914  901.32  4950.6  900.01  4998.2  895.42
  5000.9  894.92  5004.2  895.42    5060  902.35  5081.8  906.42  5087.7  906.21
  5101.5  909.14  5110.2  909.78  5136.9  914.23  5143.9  916.09    5149  916.02
  5182.8  920.51  5219.8  924.18  5298.9  929.71    5361  932.39  5469.3  935.29
#Mann= 7 ,-1 , 0
  4400.1     .05       0  4895.3     .16       0  4998.2     .07       0
  5004.2     .16       0  5110.2      .1       0  5182.8     .16       0
  5219.8      .1       0
Bank Sta=4998.2,5004.2
XS Rating Curve= 0 ,0
Exp/Cntr=0.3,0.1

Type RM Length L Ch R = 1 ,884     ,458,458,458
BEGIN DESCRIPTION:
UNT 1022 IN LATR 2.0
END DESCRIPTION:
XS GIS Cut Line= 4
       2962586.3     10110649.72      2962768.62     10110334.58
      2962669.66     10109956.97      2962471.74      10109657.5
#Sta/Elev= 30
  4456.2  932.63    4507  933.46  4556.1  933.24  4630.4   932.4    4769  928.73
  4872.8  925.93  4884.2  925.15  4903.9   922.5  4914.2  919.91  4919.4  917.29
  4924.6  916.41  4934.9  911.24  4959.8  901.34  4965.9  897.28  4986.6   891.3
    4992  889.02  4994.8  888.52    4998  889.02  5007.2  890.09  5035.4  897.58
  5048.6  898.91    5133  901.98  5156.6  903.79    5183  907.12  5209.7  911.72
  5215.6  911.72  5242.2  914.84  5322.4  920.84    5480  928.89  5569.6  931.92
#Mann= 6 ,-1 , 0
  4456.2      .1       0  4556.1     .05       0    4769     .16       0
    4992     .07       0    4998     .16       0    5133      .1       0
Bank Sta=4992,4998
XS Rating Curve= 0 ,0
Exp/Cntr=0.3,0.1

Type RM Length L Ch R = 1 ,426     ,0,0,0
BEGIN DESCRIPTION:
UNT 1022 IN LATR 1.0
END DESCRIPTION:
XS GIS Cut Line= 4
      2963172.26     10110399.67      2963193.09     10110105.41
      2963075.91     10109837.18      2962526.42     10109555.92
#Sta/Elev= 30
  4542.8  925.27    4639  924.35  4724.8   921.3  4799.4  917.56  4841.4  916.74
  4905.1  912.84    4940  904.03    4958  895.07  4963.4  893.48  4970.6  889.11
  5007.2  882.96    5010  882.46  5013.2  882.96  5015.7  883.96  5025.1  884.22
  5033.7  889.21    5047  894.54  5057.1  895.94  5129.7  900.27    5169  900.36
  5257.8  905.13  5307.8  914.32  5318.6  915.07  5352.3  920.54  5374.8  922.31
  5435.5  924.92  5668.8  929.35    5702  931.19  5718.6   930.6  5747.8  931.21
#Mann= 5 ,-1 , 0
  4542.8      .1       0  4724.8     .16       0  5007.2     .07       0
  5013.2     .16       0  5668.8      .1       0
Bank Sta=5007.2,5013.2
XS Rating Curve= 0 ,0
Exp/Cntr=0.3,0.1

Chan Stop Cuts=-1
Use User Specified Reach Order=0
Composite Channel Slope=5