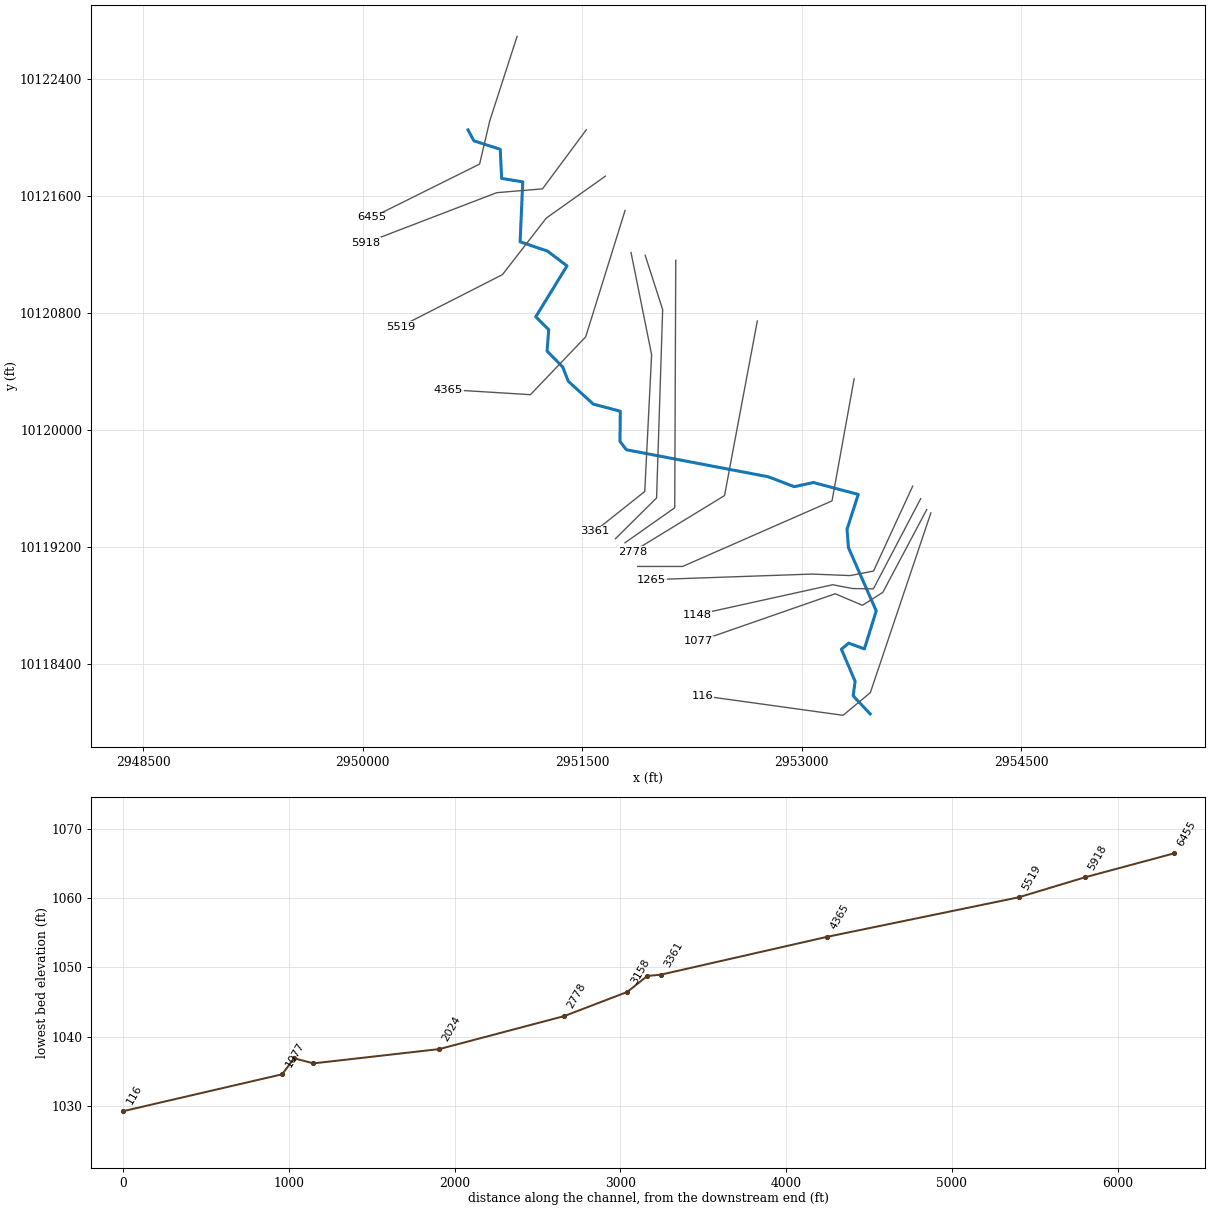
--- UNT 0023 IN LATR.prj (project) ---

Proj Title=UNT 1023 IN LATR Base Level Engineering
Current Plan=p01
Default Exp/Contr=0.3,0.1
English Units
Geom File=g01
Flow File=f01
Plan File=p01
BEGIN DESCRIPTION:
UNT 1023 IN LATR
END DESCRIPTION:

--- UNT 0023 IN LATR.p01 (plan) ---

Plan Title=Multiple Run
Short Identifier=Multiple
Geom File=g01
Flow File=f01
Subcritical Flow
K Sum by GR= 0
Std Step Tol= 0.01
Critical Tol= 0.01
Num of Std Step Trials= 20
Max Error Tol= 0.3
Flow Tol Ratio= 0.001
Split Flow NTrial= 30
Split Flow Tol= 0.02
Split Flow Ratio= 0.02
Log Output Level= 0
Friction Slope Method= 1
Unsteady Friction Slope Method= 2
Unsteady Bridges Friction Slope Method= 1
Parabolic Critical Depth
Global Vel Dist=  1 , 1 , 1
Global Log Level= 0
CheckData=True
Encroach Param= -1, 0, 0, 0
BEGIN DESCRIPTION:
Multiple Run
END DESCRIPTION:

--- UNT 0023 IN LATR.f01 (steady flow) ---

Flow Title=Multiple
Number of Profiles=7
Profile Names=10-year,25-year,50-year,1pct_min,100-year,1pct_plu,500-year
River Rch & RM= UNT 1023 IN LATR,Reach-1,6455
     777    1112    1397    1285    1738    2351    2700
River Rch & RM= UNT 1023 IN LATR,Reach-1,3158
     817    1167    1467    1348    1823    2465    2826
Boundary for River Rch & Prof#=UNT 1023 IN LATR,Reach-1,1
Up Type=0
Dn Type=3
Dn Slope=0.005
Boundary for River Rch & Prof#=UNT 1023 IN LATR,Reach-1,2
Up Type=0
Dn Type=3
Dn Slope=0.005
Boundary for River Rch & Prof#=UNT 1023 IN LATR,Reach-1,3
Up Type=0
Dn Type=3
Dn Slope=0.005
Boundary for River Rch & Prof#=UNT 1023 IN LATR,Reach-1,4
Up Type=0
Dn Type=3
Dn Slope=0.005
Boundary for River Rch & Prof#=UNT 1023 IN LATR,Reach-1,5
Up Type=0
Dn Type=3
Dn Slope=0.005
Boundary for River Rch & Prof#=UNT 1023 IN LATR,Reach-1,6
Up Type=0
Dn Type=3
Dn Slope=0.005
Boundary for River Rch & Prof#=UNT 1023 IN LATR,Reach-1,7
Up Type=0
Dn Type=3
Dn Slope=0.005

--- UNT 0023 IN LATR.g01 (geometry) ---

Geom Title=Existing Conditions

River Reach=UNT 1023 IN LATR,Reach-1
Reach XY= 30
      2950720.08     10122052.12      2950760.31     10121977.21
      2950940.33     10121919.59      2950949.96     10121720.63
      2951094.26     10121696.74      2951076.09     10121287.44
      2951263.43     10121223.64      2951396.53     10121122.83
      2951183.01     10120774.98      2951271.58     10120686.78
      2951260.38     10120540.69      2951367.41     10120431.57
      2951405.17     10120334.70      2951575.74     10120178.45
      2951760.64     10120129.79      2951758.47     10119923.73
      2951801.82     10119866.67      2952772.87     10119681.75
      2952948.90     10119614.24      2953079.82     10119642.68
      2953386.52     10119561.39      2953309.71     10119323.22
      2953319.68     10119197.33      2953509.27     10118765.73
      2953428.36     10118505.66      2953321.07     10118545.24
      2953271.26     10118503.75      2953364.99     10118284.65
      2953351.92     10118185.12      2953467.92     10118061.89

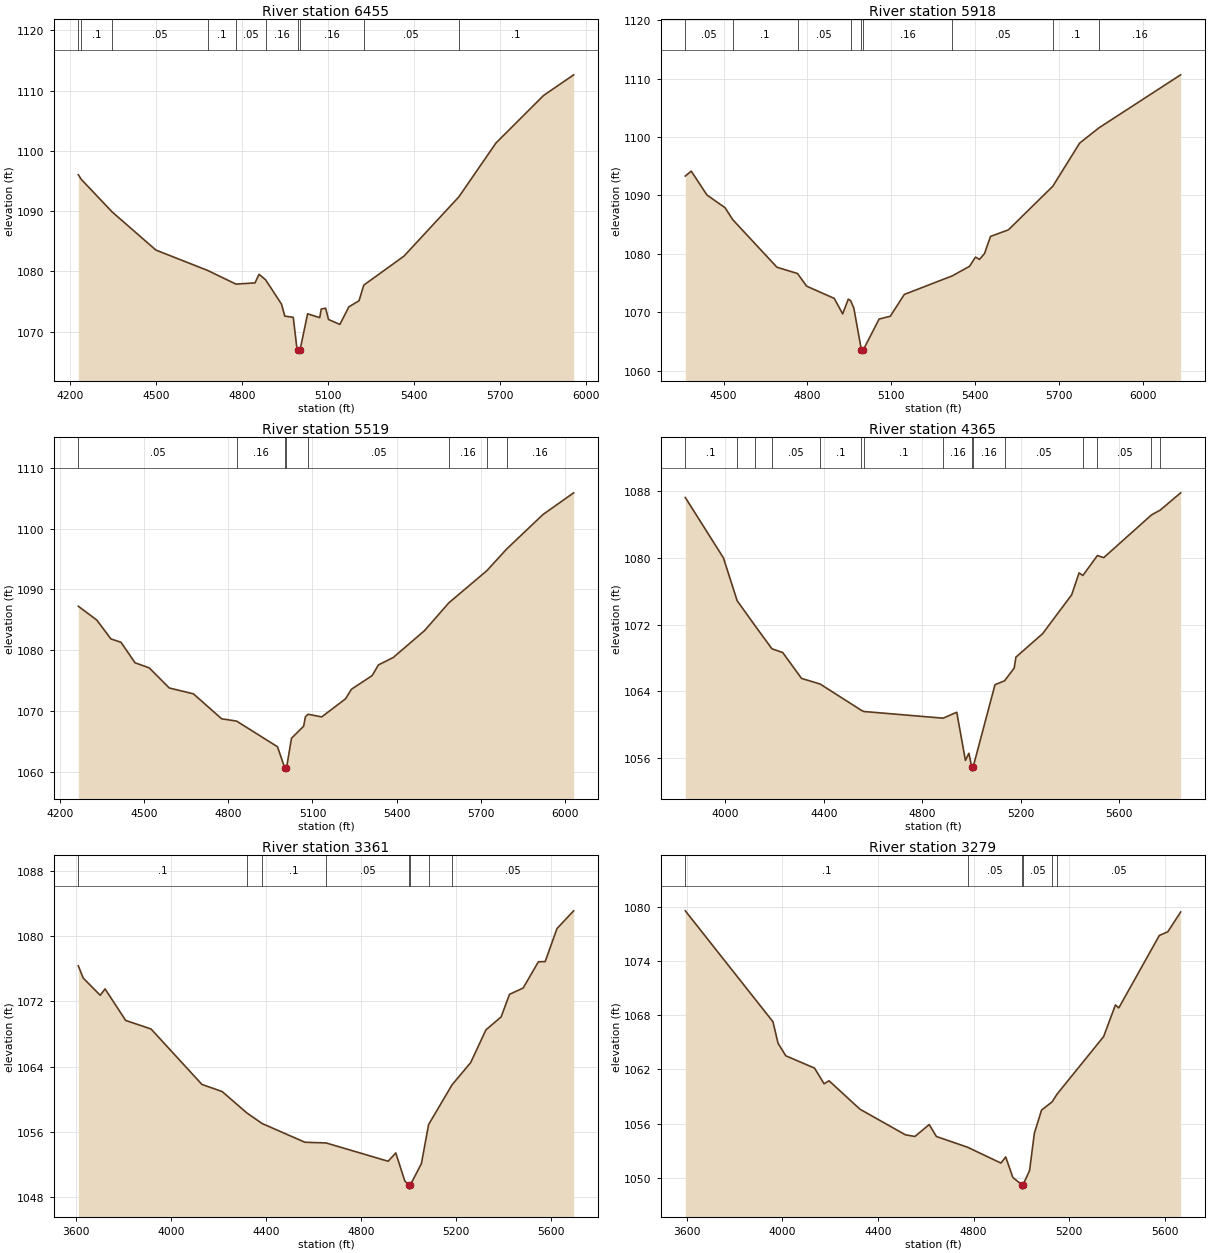
Type RM Length L Ch R = 1,6455,537,537,537
BEGIN DESCRIPTION:
UNT 1023 IN LATR 12.0
END DESCRIPTION:
XS GIS Cut Line= 4
      2951055.36     10122690.75      2950868.73     10122113.51
      2950799.29     10121818.37      2950065.75     10121453.78
#Sta/Elev= 30
  4229.0 1096.04  4239.0 1095.29  4347.2 1089.86  4499.8 1083.54  4680.9 1080.15
  4779.2 1077.89  4845.7 1078.09  4859.9 1079.52  4882.7 1078.61  4938.2 1074.58
  4949.8 1072.58  4979.3 1072.38  4992.1 1067.20  4996.8 1066.94  4999.5 1066.44
  5002.8 1066.94  5029.4 1072.96  5071.7 1072.33  5076.9 1073.76  5092.3 1073.89
  5102.5 1072.02  5142.1 1071.20  5173.3 1074.12  5208.9 1075.13  5225.4 1077.72
  5365.7 1082.53  5557.2 1092.36  5687.0 1101.31  5852.9 1109.18  5958.0 1112.61
#Mann=10,-1,0
  4229.0    0.05       0  4239.0     0.1       0  4347.2    0.05       0
  4680.9     0.1       0  4779.2    0.05       0  4882.7    0.16       0
  4996.8    0.07       0  5002.8    0.16       0  5225.4    0.05       0
  5557.2     0.1       0
Bank Sta=4996.8,5002.8
Exp/Cntr=0.3,0.1

Type RM Length L Ch R = 1,5918,399,399,399
BEGIN DESCRIPTION:
UNT 1023 IN LATR 11.0
END DESCRIPTION:
XS GIS Cut Line= 4
      2951528.43     10122052.71      2951228.97     10121649.10
      2950916.47     10121623.06      2950022.88     10121280.37
#Sta/Elev= 30
  4363.0 1093.31  4384.3 1094.15  4440.6 1090.06  4505.3 1087.89  4533.2 1085.82
  4691.0 1077.70  4764.8 1076.62  4797.5 1074.45  4896.2 1072.36  4926.3 1069.71
  4946.4 1072.22  4954.8 1071.98  4966.4 1070.69  4993.5 1063.49  4996.3 1062.99
  4999.5 1063.49  5056.7 1068.82  5096.9 1069.31  5147.0 1073.04  5318.8 1076.22
  5380.5 1077.85  5401.9 1079.43  5416.3 1079.04  5434.1 1080.04  5455.5 1082.97
  5519.7 1084.10  5678.7 1091.57  5774.6 1098.95  5844.3 1101.58  6136.2 1110.64
#Mann=9,-1,0
  4363.0    0.05       0  4533.2     0.1       0  4764.8    0.05       0
  4954.8    0.16       0  4993.5    0.07       0  4999.5    0.16       0
  5318.8    0.05       0  5678.7     0.1       0  5844.3    0.16       0
Bank Sta=4993.5,4999.5
Exp/Cntr=0.3,0.1

Type RM Length L Ch R = 1,5519,1154,1154,1154
BEGIN DESCRIPTION:
UNT 1023 IN LATR 10.0
END DESCRIPTION:
XS GIS Cut Line= 4
      2951658.63     10121735.88      2951255.02     10121449.45
      2950955.54     10121063.16      2950258.18     10120707.99
#Sta/Elev= 30
  4265.0 1087.24  4330.9 1084.97  4381.4 1081.86  4417.0 1081.32  4467.5 1077.93
  4517.9 1077.10  4589.3 1073.79  4675.4 1072.83  4776.1 1068.72  4829.5 1068.34
  4975.3 1064.12  5001.3 1060.61  5004.0 1060.11  5007.3 1060.61  5025.1 1065.51
  5068.5 1067.50  5074.9 1069.07  5084.5 1069.47  5132.8 1069.03  5217.9 1072.01
  5238.7 1073.57  5312.7 1075.83  5335.2 1077.59  5388.2 1078.81  5499.4 1083.22
  5586.4 1087.81  5721.3 1093.07  5792.1 1096.64  5921.9 1102.33  6031.3 1105.90
#Mann=8,-1,0
  4265.0    0.05       0  4829.5    0.16       0  5001.3    0.07       0
  5007.3    0.16       0  5084.5    0.05       0  5586.4    0.16       0
  5721.3     0.1       0  5792.1    0.16       0
Bank Sta=5001.3,5007.3
Exp/Cntr=0.3,0.1

Type RM Length L Ch R = 1,4365,1004,1004,1004
BEGIN DESCRIPTION:
UNT 1023 IN LATR 9.0
END DESCRIPTION:
XS GIS Cut Line= 4
      2951793.22     10121501.57      2951524.11     10120637.82
      2951146.51     10120242.85      2950586.62     10120277.57
#Sta/Elev= 30
  3836.9 1087.23  3991.8 1079.99  4047.6 1074.85  4120.0 1071.87  4188.8 1069.09
  4232.7 1068.64  4309.0 1065.54  4384.9 1064.86  4552.1 1061.71  4562.1 1061.57
  4884.2 1060.77  4939.6 1061.48  4974.8 1055.71  4989.0 1056.56  5000.1 1054.92
  5002.9 1054.42  5006.1 1054.92  5094.9 1064.78  5133.8 1065.25  5172.9 1066.78
  5179.9 1068.09  5288.0 1070.89  5406.3 1075.56  5436.4 1078.19  5451.9 1077.88
  5510.9 1080.27  5536.6 1080.02  5730.5 1085.14  5766.1 1085.72  5849.0 1087.79
#Mann=15,-1,0
  3836.9     0.1       0  4047.6    0.05       0  4120.0     0.1       0
  4188.8    0.05       0  4384.9     0.1       0  4552.1    0.05       0
  4562.1     0.1       0  4884.2    0.16       0  5000.1    0.07       0
  5006.1    0.16       0  5133.8    0.05       0  5451.9    0.16       0
  5510.9    0.05       0  5730.5     0.1       0  5766.1    0.16       0
Bank Sta=5000.1,5006.1
Exp/Cntr=0.3,0.1

Type RM Length L Ch R = 1,3361,82,82,82
BEGIN DESCRIPTION:
UNT 1023 IN LATR 8.0
END DESCRIPTION:
XS GIS Cut Line= 4
      2951834.01     10121214.21      2951974.63     10120516.29
      2951927.76     10119581.39      2951584.52     10119308.36
#Sta/Elev= 30
  3608.3 1076.36  3629.2 1074.85  3700.6 1072.75  3721.0 1073.53  3807.9 1069.66
  3914.8 1068.61  4129.0 1061.81  4214.4 1060.93  4318.3 1058.31  4382.7 1057.01
  4563.1 1054.71  4651.6 1054.63  4913.5 1052.38  4945.6 1053.40  4983.6 1049.96
  5000.7 1049.46  5003.4 1048.96  5006.7 1049.46  5053.7 1052.10  5083.8 1056.88
  5182.4 1061.75  5261.2 1064.49  5325.3 1068.50  5389.3 1070.09  5424.6 1072.86
  5482.3 1073.64  5546.3 1076.86  5574.9 1076.88  5624.8 1080.94  5694.9 1083.11
#Mann=8,-1,0
  3608.3     0.1       0  4318.3    0.05       0  4382.7     0.1       0
  4651.6    0.05       0  5000.7   0.035       0  5006.7    0.05       0
  5083.8     0.1       0  5182.4    0.05       0
Bank Sta=5000.7,5006.7
Exp/Cntr=0.3,0.1

Type RM Length L Ch R = 1,3279,121,121,121
BEGIN DESCRIPTION:
UNT 1023 IN LATR 7.0
END DESCRIPTION:
XS GIS Cut Line= 4
      2951930.38     10121195.93      2952050.15     10120823.58
      2952008.49     10119537.12      2951727.37     10119258.61
#Sta/Elev= 30
  3593.1 1079.54  3960.1 1067.28  3981.5 1064.89  4014.1 1063.51  4134.2 1062.15
  4174.2 1060.42  4195.0 1060.75  4324.3 1057.61  4514.4 1054.78  4554.4 1054.59
  4614.4 1055.91  4644.4 1054.59  4775.1 1053.40  4914.6 1051.65  4934.6 1052.33
  4964.6 1050.06  5001.6 1049.27  5004.4 1048.77  5007.6 1049.27  5034.6 1050.83
  5054.7 1054.96  5084.7 1057.51  5129.0 1058.42  5149.8 1059.28  5344.5 1065.63
  5394.0 1069.13  5408.2 1068.81  5577.9 1076.82  5613.2 1077.22  5667.1 1079.41
#Mann=6,-1,0
  3593.1     0.1       0  4775.1    0.05       0  5001.6   0.035       0
  5007.6    0.05       0  5129.0     0.1       0  5149.8    0.05       0
Bank Sta=5001.6,5007.6
Exp/Cntr=0.3,0.1

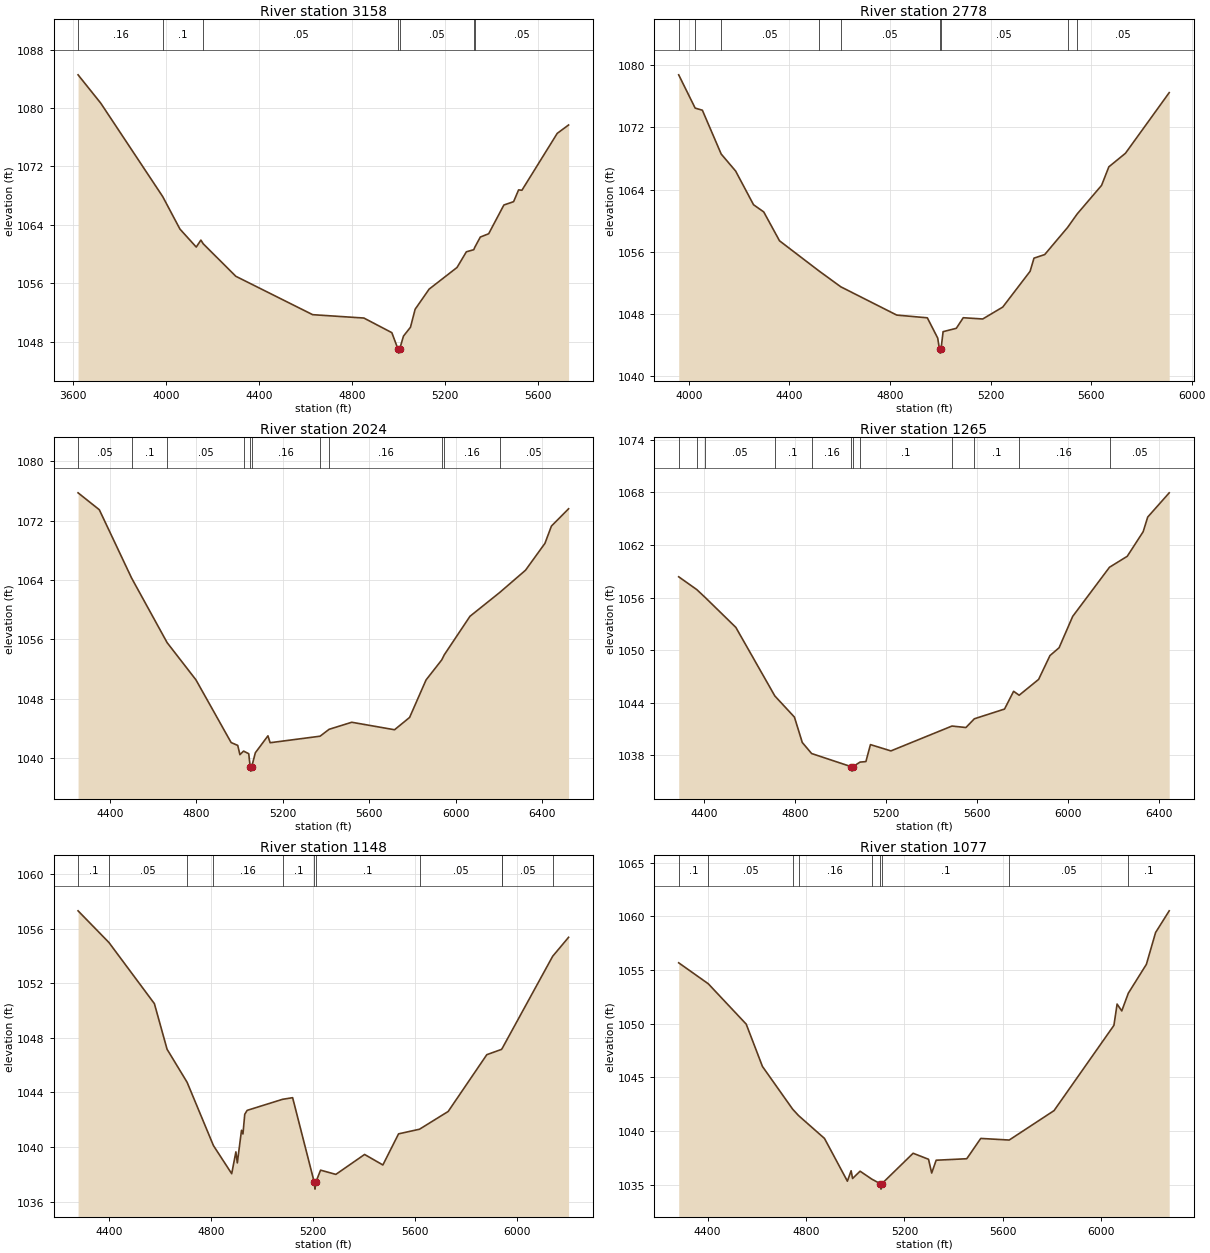
Type RM Length L Ch R = 1,3158,380,380,380
BEGIN DESCRIPTION:
UNT 1023 IN LATR 6.0
END DESCRIPTION:
XS GIS Cut Line= 3
      2952139.56     10121161.26      2952132.62     10119470.28
      2951792.88     10119231.08
#Sta/Elev= 30
  3623.1 1084.54  3720.6 1080.66  3986.5 1067.89  4060.6 1063.44  4130.6 1060.98
  4150.6 1061.93  4160.8 1061.42  4300.6 1056.98  4630.6 1051.73  4850.6 1051.27
  4970.6 1049.27  4997.6 1046.97  5000.4 1046.47  5003.6 1046.97  5020.6 1048.80
  5050.6 1050.01  5070.6 1052.47  5130.6 1055.22  5250.6 1058.19  5290.6 1060.33
  5322.5 1060.62  5327.0 1060.96  5350.6 1062.35  5386.4 1062.80  5451.7 1066.73
  5493.5 1067.19  5514.9 1068.80  5529.2 1068.75  5680.8 1076.53  5729.6 1077.68
#Mann=7,-1,0
  3623.1    0.16       0  3986.5     0.1       0  4160.8    0.05       0
  4997.6   0.035       0  5003.6    0.05       0  5322.5     0.1       0
  5327.0    0.05       0
Bank Sta=4997.6,5003.6
Exp/Cntr=0.3,0.1

Type RM Length L Ch R = 1,2778,754,754,754
BEGIN DESCRIPTION:
UNT 1023 IN LATR 5.0
END DESCRIPTION:
XS GIS Cut Line= 3
      2952696.85     10120746.31      2952472.90     10119553.62
      2951843.51     10119168.70
#Sta/Elev= 30
  3959.4 1078.77  4024.9 1074.49  4053.6 1074.22  4128.4 1068.59  4185.9 1066.40
  4257.1 1062.07  4297.8 1061.14  4360.5 1057.43  4517.4 1053.56  4604.1 1051.52
  4826.9 1047.88  4948.5 1047.53  4989.7 1044.93  4996.9 1043.49  4999.6 1042.99
  5002.9 1043.49  5011.2 1045.75  5063.7 1046.18  5091.4 1047.54  5168.8 1047.38
  5248.5 1048.91  5357.3 1053.51  5372.8 1055.20  5415.4 1055.66  5506.2 1059.14
  5544.5 1060.88  5641.7 1064.56  5670.5 1066.94  5736.5 1068.68  5910.7 1076.48
#Mann=9,-1,0
  3959.4     0.1       0  4024.9    0.16       0  4128.4    0.05       0
  4517.4     0.1       0  4604.1    0.05       0  4996.9   0.035       0
  5002.9    0.05       0  5506.2     0.1       0  5544.5    0.05       0
Bank Sta=4996.9,5002.9
Exp/Cntr=0.3,0.1

Type RM Length L Ch R = 1,2024,759,759,759
BEGIN DESCRIPTION:
UNT 1023 IN LATR 4.0
END DESCRIPTION:
XS GIS Cut Line= 4
      2953358.31     10120350.45      2953207.27     10119517.16
      2952186.44     10119069.24      2951879.18     10119069.24
#Sta/Elev= 30
  4253.5 1075.76  4351.8 1073.48  4500.9 1064.28  4665.4 1055.56  4799.0 1050.53
  4961.6 1042.08  4992.1 1041.70  5002.2 1040.45  5019.0 1040.93  5042.9 1040.58
  5050.0 1038.73  5052.8 1038.23  5056.0 1038.73  5073.4 1040.70  5131.8 1042.99
  5141.8 1042.06  5372.8 1042.94  5414.8 1043.87  5519.5 1044.82  5717.4 1043.81
  5787.0 1045.47  5863.0 1050.52  5935.7 1053.23  5947.5 1053.92  6066.3 1059.11
  6203.8 1062.32  6323.1 1065.32  6413.1 1068.95  6443.1 1071.28  6522.4 1073.61
#Mann=11,-1,0
  4253.5    0.05       0  4500.9     0.1       0  4665.4    0.05       0
  5019.0    0.16       0  5050.0   0.035       0  5056.0    0.16       0
  5372.8    0.05       0  5414.8    0.16       0  5935.7    0.05       0
  5947.5    0.16       0  6203.8    0.05       0
Bank Sta=5050,5056
Exp/Cntr=0.3,0.1

Type RM Length L Ch R = 1,1265,117,117,117
BEGIN DESCRIPTION:
UNT 1023 IN LATR 3.0
END DESCRIPTION:
XS GIS Cut Line= 5
      2953758.51     10119617.89      2953491.13     10119037.99
      2953331.40     10119006.74      2953070.99     10119017.16
      2951973.80     10118978.96
#Sta/Elev= 30
  4286.4 1058.37  4365.9 1056.91  4403.8 1055.99  4538.0 1052.59  4709.7 1044.76
  4796.0 1042.34  4830.6 1039.44  4871.7 1038.18  5047.0 1036.67  5049.7 1036.17
  5053.0 1036.67  5084.8 1037.20  5110.7 1037.26  5130.7 1039.20  5220.8 1038.48
  5489.7 1041.32  5551.0 1041.15  5588.3 1042.15  5721.1 1043.26  5761.1 1045.29
  5785.5 1044.84  5871.2 1046.65  5921.2 1049.37  5961.2 1050.26  6021.3 1053.85
  6183.3 1059.46  6261.4 1060.71  6331.5 1063.52  6351.5 1065.19  6446.2 1067.96
#Mann=12,-1,0
  4286.4    0.16       0  4365.9     0.1       0  4403.8    0.05       0
  4709.7     0.1       0  4871.7    0.16       0  5047.0    0.07       0
  5053.0    0.16       0  5084.8     0.1       0  5489.7    0.16       0
  5588.3     0.1       0  5785.5    0.16       0  6183.3    0.05       0
Bank Sta=5047,5053
Exp/Cntr=0.3,0.1

Type RM Length L Ch R = 1,1148,71,71,71
BEGIN DESCRIPTION:
UNT 1023 IN LATR 2.0
END DESCRIPTION:
XS GIS Cut Line= 5
      2953813.16     10119532.31      2953489.82     10118916.03
      2953348.77     10118918.20      2953212.05     10118944.24
      2952287.59     10118740.25
#Sta/Elev= 30
  4278.1 1057.30  4399.1 1054.98  4577.3 1050.50  4627.0 1047.16  4705.5 1044.74
  4808.8 1040.10  4880.4 1038.04  4896.8 1039.64  4902.4 1038.83  4918.8 1041.22
  4924.5 1040.95  4931.5 1042.39  4940.9 1042.68  5079.7 1043.49  5119.2 1043.61
  5204.0 1037.41  5206.8 1036.91  5210.0 1037.41  5228.7 1038.30  5288.7 1037.99
  5401.3 1039.45  5473.0 1038.68  5534.5 1040.96  5616.7 1041.30  5729.0 1042.60
  5880.4 1046.76  5938.3 1047.15  5941.6 1047.25  6138.6 1053.97  6201.0 1055.36
#Mann=11,-1,0
  4278.1     0.1       0  4399.1    0.05       0  4705.5     0.1       0
  4808.8    0.16       0  5079.7     0.1       0  5204.0    0.07       0
  5210.0     0.1       0  5616.7    0.05       0  5938.3     0.1       0
  5941.6    0.05       0  6138.6    0.16       0
Bank Sta=5204,5210
Exp/Cntr=0.3,0.1

Type RM Length L Ch R = 1,1077,961,961,961
BEGIN DESCRIPTION:
Mapping XS 1c194f5c
END DESCRIPTION:
XS GIS Cut Line= 5
      2953854.28     10119457.44      2953554.27     10118892.16
      2953415.33     10118803.74      2953229.02     10118882.68
      2952296.18     10118558.08
#Sta/Elev= 30
  4282.2 1055.67  4402.5 1053.72  4556.8 1049.96  4622.8 1046.02  4745.4 1042.05
  4769.5 1041.45  4875.1 1039.32  4968.2 1035.34  4983.4 1036.31  4989.3 1035.59
  5019.8 1036.27  5067.5 1035.53  5102.2 1035.10  5104.9 1034.60  5108.2 1035.10
  5235.5 1037.94  5298.1 1037.38  5311.0 1036.10  5329.2 1037.29  5453.6 1037.43
  5510.5 1039.32  5626.3 1039.17  5808.6 1041.91  6052.1 1049.85  6065.0 1051.83
  6083.9 1051.19  6110.6 1052.84  6184.1 1055.53  6221.5 1058.49  6276.9 1060.51
#Mann=9,-1,0
  4282.2     0.1       0  4402.5    0.05       0  4745.4     0.1       0
  4769.5    0.16       0  5067.5     0.1       0  5102.2    0.07       0
  5108.2     0.1       0  5626.3    0.05       0  6110.6     0.1       0
Bank Sta=5102.2,5108.2
Exp/Cntr=0.3,0.1

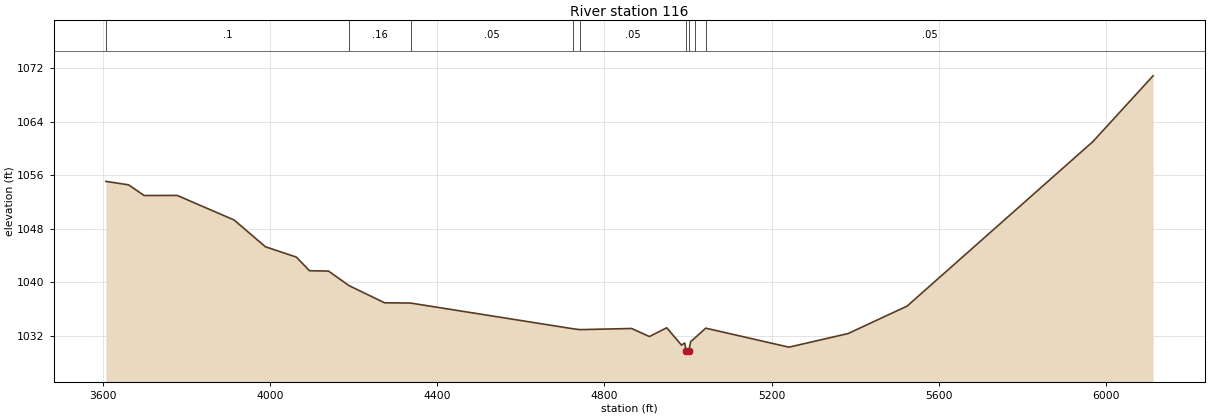
Type RM Length L Ch R = 1,116,0,0,0
BEGIN DESCRIPTION:
UNT 1023 IN LATR 1.0
END DESCRIPTION:
XS GIS Cut Line= 4
      2953882.68     10119435.29      2953469.01     10118206.91
      2953282.70     10118052.18      2952325.89     10118184.80
#Sta/Elev= 30
  3608.1 1055.08  3662.5 1054.56  3699.5 1052.97  3778.6 1052.98  3914.7 1049.31
  3989.6 1045.31  4063.5 1043.77  4095.1 1041.73  4140.5 1041.68  4190.0 1039.49
  4274.5 1036.94  4336.7 1036.90  4726.1 1033.05  4741.6 1032.93  4865.4 1033.10
  4907.9 1031.90  4949.4 1033.21  4984.6 1030.62  4992.4 1030.93  4995.9 1029.77
  4998.6 1029.27  5001.9 1029.77  5006.7 1031.15  5016.2 1031.66  5042.7 1033.15
  5241.6 1030.31  5382.9 1032.34  5524.3 1036.45  5968.5 1061.02  6112.4 1070.85
#Mann=9,-1,0
  3608.1     0.1       0  4190.0    0.16       0  4336.7    0.05       0
  4726.1    0.16       0  4741.6    0.05       0  4995.9   0.035       0
  5001.9    0.05       0  5016.2     0.1       0  5042.7    0.05       0
Bank Sta=4995.9,5001.9
Exp/Cntr=0.3,0.1

Chan Stop Cuts=-1