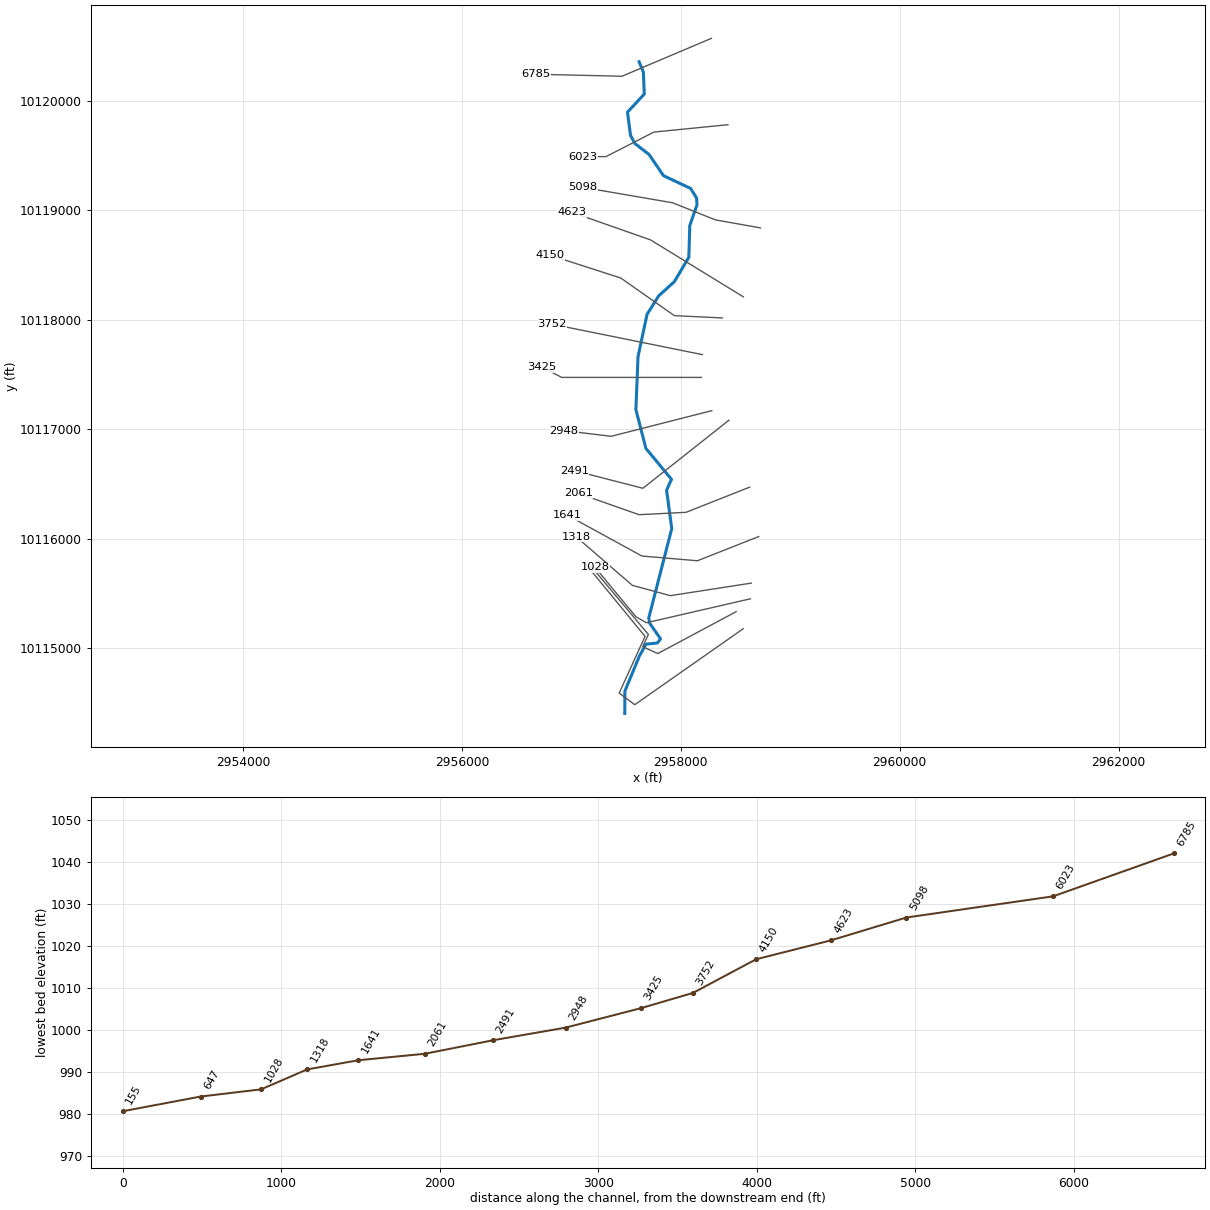
--- UNT 0024 IN LATR.prj (project) ---

Proj Title=UNT 1024 IN LATR Base Level Engineering
Current Plan=p01
Default Exp/Contr=0.3,0.1
English Units
Geom File=g01
Flow File=f01
Plan File=p01
Y Axis Title=Elevation
X Axis Title(PF)=Main Channel Distance
X Axis Title(XS)=Station
BEGIN DESCRIPTION:
UNT 1024 IN LATR
END DESCRIPTION:
DSS Export Rating Curves= 0
DSS Export Rating Curve Sorted= 0
DSS Export Volume Flow Curves= 0
DXF OffsetX= 0
DXF OffsetY= 0
DXF ScaleX= 1
DXF ScaleY= 10

--- UNT 0024 IN LATR.p01 (plan) ---

Plan Title=Multiple Run
Short Identifier=Multiple
Geom File=g01
Flow File=f01
Subcritical Flow
K Sum by GR= 0
Std Step Tol= 0.01
Critical Tol= 0.01
Num of Std Step Trials= 20
Max Error Tol= 0.3
Flow Tol Ratio= 0.001
Split Flow NTrial= 30
Split Flow Tol= 0.02
Split Flow Ratio= 0.02
Log Output Level= 0
Friction Slope Method= 1
Unsteady Friction Slope Method= 2
Unsteady Bridges Friction Slope Method= 1
Parabolic Critical Depth
Global Vel Dist=  1 , 1 , 1
Global Log Level= 0
CheckData=True
Encroach Param= -1, 0, 0, 0
BEGIN DESCRIPTION:
Multiple Run
END DESCRIPTION:

--- UNT 0024 IN LATR.f01 (steady flow) ---

Flow Title=Multiple
Program Version=4.10
Number of Profiles= 7
Profile Names=10-year,25-year,50-year,1pct_min,100-year,1pct_plu,500-year
River Rch & RM=UNT 1024 IN LATR,Reach-1         ,6785
    1422    2123    2749    2603    3520    4760    5795
Boundary for River Rch & Prof#=UNT 1024 IN LATR,Reach-1         , 1
Up Type= 0
Dn Type= 3
Dn Slope=0.00712
Boundary for River Rch & Prof#=UNT 1024 IN LATR,Reach-1         , 2
Up Type= 0
Dn Type= 3
Dn Slope=0.00712
Boundary for River Rch & Prof#=UNT 1024 IN LATR,Reach-1         , 3
Up Type= 0
Dn Type= 3
Dn Slope=0.00712
Boundary for River Rch & Prof#=UNT 1024 IN LATR,Reach-1         , 4
Up Type= 0
Dn Type= 3
Dn Slope=0.00712
Boundary for River Rch & Prof#=UNT 1024 IN LATR,Reach-1         , 5
Up Type= 0
Dn Type= 3
Dn Slope=0.00712
Boundary for River Rch & Prof#=UNT 1024 IN LATR,Reach-1         , 6
Up Type= 0
Dn Type= 3
Dn Slope=0.00712
Boundary for River Rch & Prof#=UNT 1024 IN LATR,Reach-1         , 7
Up Type= 0
Dn Type= 3
Dn Slope=0.00712
DSS Import GetInterval= 0
DSS Import GetPeak= 0
DSS Import FillOption= 0

--- UNT 0024 IN LATR.g01 (geometry) ---

Geom Title=Existing Conditions
Program Version=4.10

River Reach=UNT 1024 IN LATR,Reach-1
Reach XY= 30
      2957619.45     10120357.98      2957658.47     10120263.73
      2957666.83     10120062.57      2957513.53     10119896.98
      2957541.08     10119684.81       2957581.5     10119610.13
      2957710.57     10119510.53      2957841.82     10119317.01
      2958090.76     10119199.75      2958145.03     10119112.26
      2958148.83     10119052.22      2958082.52     10118860.65
      2958074.05     10118570.85      2957940.89     10118347.39
      2957799.41     10118219.56      2957692.27     10118050.09
      2957609.73     10117663.19      2957590.22     10117179.57
      2957681.64     10116825.05      2957915.38     10116542.57
      2957870.67       10116442.      2957917.96     10116092.11
      2957708.53     10115278.26      2957713.78     10115231.32
      2957815.74     10115084.44      2957787.42     10115047.28
      2957682.43      10115035.8      2957621.62     10114926.04
      2957489.97     10114608.11      2957488.47     10114403.73

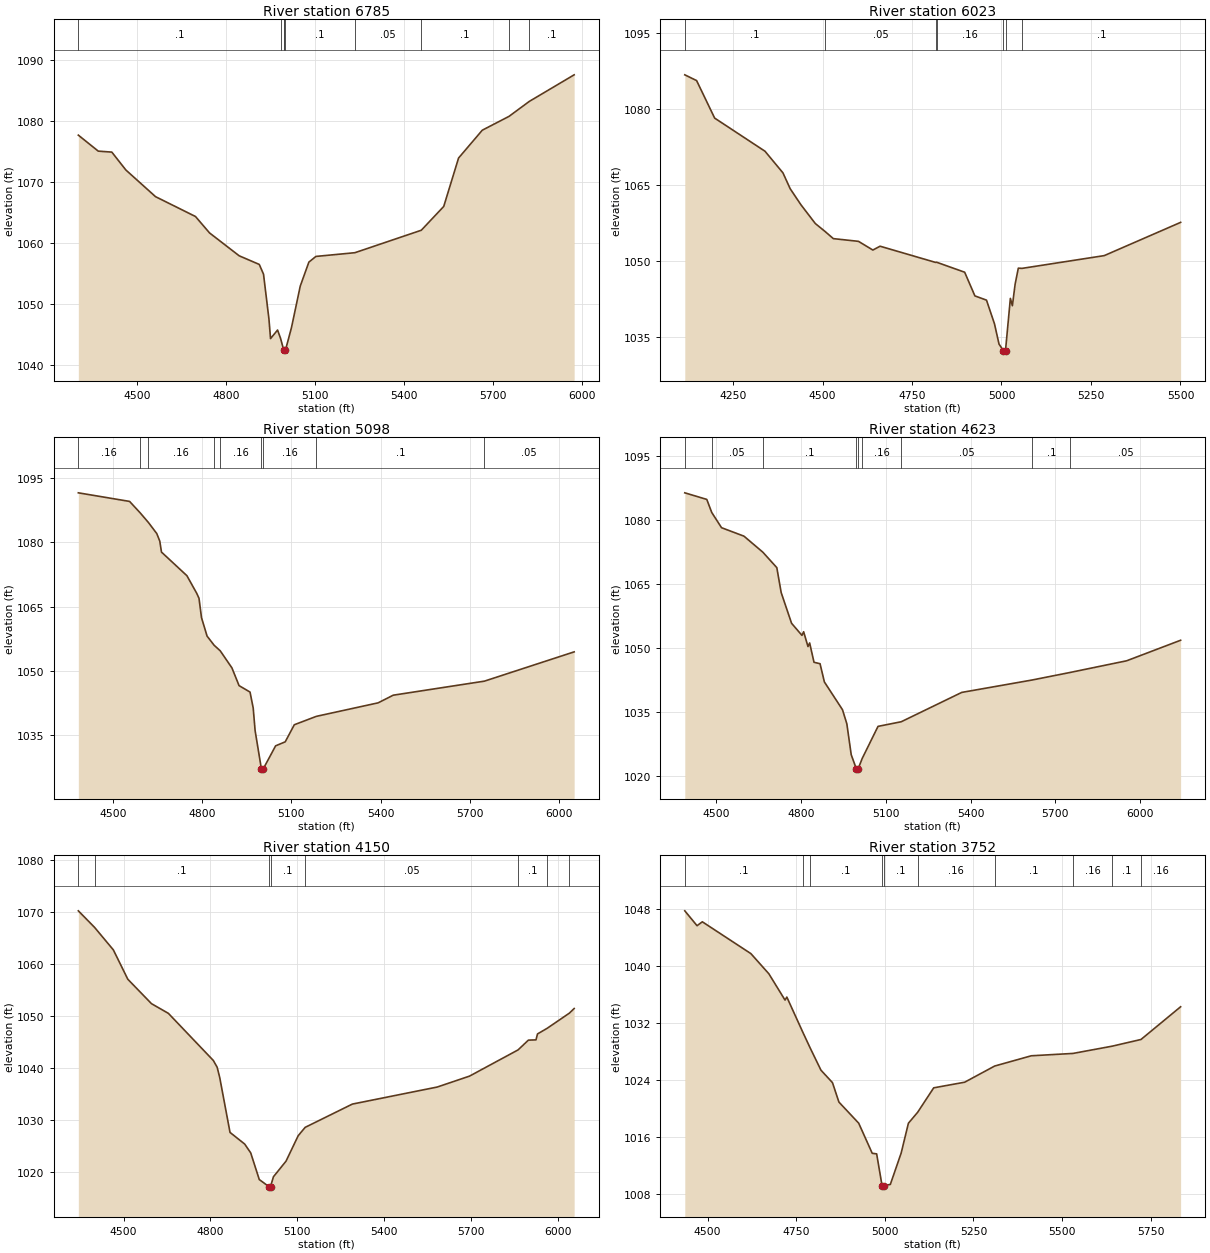
Type RM Length L Ch R = 1 ,6785    ,762,762,762
BEGIN DESCRIPTION:
UNT 1024 IN LATR 14.0
END DESCRIPTION:
XS GIS Cut Line= 3
      2958280.35     10120571.56      2957462.63      10120225.2
      2956678.79     10120243.43
#Sta/Elev= 30
  4302.8 1077.65    4370 1075.03  4415.7 1074.87  4463.1 1071.94  4563.2 1067.57
  4697.9 1064.32  4745.3 1061.63  4845.4 1057.88    4913 1056.47  4927.3 1054.88
  4945.6 1047.53    4951 1044.32  4974.7 1045.72  4984.6 1044.39  4994.7 1042.58
  4995.4 1042.44  4998.1 1041.94  5001.4 1042.44  5021.6 1046.12  5051.2 1052.92
  5080.3 1056.85    5104 1057.78  5235.4 1058.39  5459.4 1062.07  5535.1 1065.97
  5585.1  1073.9  5665.1 1078.46  5755.1 1080.72  5823.8 1083.18  5974.9 1087.53
#Mann= 9 ,-1 , 0
  4302.8      .1       0  4984.6     .05       0  4994.7      .1       0
  4995.4     .07       0  5001.4      .1       0  5235.4     .05       0
  5459.4      .1       0  5755.1     .05       0  5823.8      .1       0
Bank Sta=4995.4,5001.4
XS Rating Curve= 0 ,0
Exp/Cntr=0.3,0.1

Type RM Length L Ch R = 1 ,6023    ,925,925,925
BEGIN DESCRIPTION:
UNT 1024 IN LATR 12.0
END DESCRIPTION:
XS GIS Cut Line= 4
      2958431.41      10119782.5      2957754.29     10119714.78
      2957316.79     10119490.83      2957103.37     10119490.83
#Sta/Elev= 30
  4115.1 1086.72  4148.1 1085.58  4198.5 1078.17  4339.2 1071.62  4389.4 1067.34
  4409.5 1064.22  4439.6 1061.04  4479.8 1057.33  4507.4 1055.74  4530.1 1054.35
  4600.4 1053.81  4640.6 1052.09  4660.7 1052.85  4815.7 1049.65  4818.8 1049.68
  4897.1 1047.71  4925.7 1043.03  4958.1 1042.19  4980.4 1037.51  4993.1 1033.51
  5005.2 1032.22  5007.9 1031.72  5011.2 1032.22  5024.8 1042.54  5030.4 1041.09
  5038.1 1045.35    5047 1048.51  5057.4 1048.47  5287.1 1050.99  5500.5 1057.56
#Mann= 7 ,-1 , 0
  4115.1      .1       0  4507.4     .05       0  4815.7      .1       0
  4818.8     .16       0  5005.2     .07       0  5011.2     .16       0
  5057.4      .1       0
Bank Sta=5005.2,5011.2
XS Rating Curve= 0 ,0
Exp/Cntr=0.3,0.1

Type RM Length L Ch R = 1 ,5098    ,475,475,475
BEGIN DESCRIPTION:
UNT 1024 IN LATR 10.0
END DESCRIPTION:
XS GIS Cut Line= 4
      2958728.29     10118839.78      2958316.79      10118912.7
      2957926.17     10119068.95      2957108.49     10119209.57
#Sta/Elev= 30
  4383.1 1091.48  4555.6 1089.48  4591.5 1086.79  4618.8 1084.58    4647    1082
  4657.1 1080.25  4662.9 1077.68  4748.5 1072.18  4781.2 1068.12  4789.1 1066.93
  4797.6  1062.4  4816.3 1058.12    4840 1055.99  4860.5  1054.7  4899.8 1050.73
    4924 1046.58  4960.8 1045.09  4971.5 1041.37  4977.9 1036.12  4999.1 1027.18
  5001.8 1026.68  5005.1 1027.18  5046.9 1032.57  5079.2  1033.5  5109.8 1037.48
  5183.8 1039.43  5391.9 1042.58  5442.6 1044.36  5749.4 1047.63  6051.4 1054.45
#Mann= 9 ,-1 , 0
  4383.1     .16       0  4591.5      .1       0  4618.8     .16       0
    4840      .1       0  4860.5     .16       0  4999.1     .07       0
  5005.1     .16       0  5183.8      .1       0  5749.4     .05       0
Bank Sta=4999.1,5005.1
XS Rating Curve= 0 ,0
Exp/Cntr=0.3,0.1

Type RM Length L Ch R = 1 ,4623    ,473,473,473
BEGIN DESCRIPTION:
UNT 1024 IN LATR 9.0
END DESCRIPTION:
XS GIS Cut Line= 3
      2958572.03     10118209.56      2957723.04     10118730.41
       2957009.5     10118980.41
#Sta/Elev= 30
  4390.3  1086.3    4468 1084.76  4485.5 1081.71  4520.1 1078.15  4599.4 1076.17
  4666.2 1072.42  4715.5 1068.81  4730.9 1062.98  4767.6 1055.81  4804.3 1052.98
  4810.2 1053.83  4825.6 1050.37  4831.5 1051.21  4846.9 1046.69  4868.2 1046.36
  4883.6 1042.09  4947.5 1035.61  4962.9 1032.32  4978.4 1025.08  4996.7 1021.75
  4999.4 1021.25  5002.7 1021.75  5016.9 1024.17  5073.1 1031.71  5155.1 1032.79
    5369 1039.65  5617.9 1042.55  5753.2 1044.33  5951.7 1047.04  6142.4 1051.84
#Mann= 9 ,-1 , 0
  4390.3      .1       0  4485.5     .05       0  4666.2      .1       0
  4996.7     .07       0  5002.7      .1       0  5016.9     .16       0
  5155.1     .05       0  5617.9      .1       0  5753.2     .05       0
Bank Sta=4996.7,5002.7
XS Rating Curve= 0 ,0
Exp/Cntr=0.3,0.1

Type RM Length L Ch R = 1 ,4150    ,398,398,398
BEGIN DESCRIPTION:
UNT 1024 IN LATR 8.0
END DESCRIPTION:
XS GIS Cut Line= 4
      2958379.29     10118016.87      2957941.79      10118037.7
      2957452.21     10118381.45        2956808.     10118589.26
#Sta/Elev= 30
  4343.9 1070.18  4400.2 1066.99  4464.9 1062.68  4514.9 1057.04  4596.7 1052.35
  4655.1 1050.49  4810.4 1041.44  4823.6 1040.14  4832.3 1038.21    4868 1027.63
  4918.6  1025.4  4939.5  1023.7  4969.1 1018.58  5001.9 1017.24  5004.6 1016.74
  5007.9 1017.24  5018.1 1019.12  5061.5 1022.11  5103.6    1027  5127.6  1028.6
  5290.7 1033.07  5583.7 1036.34  5695.5 1038.44  5863.1 1043.47  5898.9 1045.35
  5925.1  1045.4  5930.4 1046.54  5963.7 1047.62  6040.4 1050.53    6057 1051.42
#Mann= 8 ,-1 , 0
  4343.9     .05       0  4400.2      .1       0  5001.9     .07       0
  5007.9      .1       0  5127.6     .05       0  5863.1      .1       0
  5963.7     .16       0  6040.4      .1       0
Bank Sta=5001.9,5007.9
XS Rating Curve= 0 ,0
Exp/Cntr=0.3,0.1

Type RM Length L Ch R = 1 ,3752    ,327,327,327
BEGIN DESCRIPTION:
UNT 1024 IN LATR 7.0
END DESCRIPTION:
XS GIS Cut Line= 2
      2958196.99      10117681.8      2956825.43     10117959.58
#Sta/Elev= 30
  4435.5  1047.8  4470.1 1045.71    4485 1046.26  4622.1 1041.79  4672.8 1038.96
  4718.4 1035.27  4723.5 1035.69  4768.4 1030.78  4789.8  1028.5  4819.8 1025.43
  4852.3 1023.68  4870.5 1020.95  4926.3 1017.99  4964.5 1013.76    4977 1013.68
  4992.2 1009.23  4994.9 1008.73  4998.2 1009.23  5015.6 1009.39  5046.2  1013.8
  5066.6 1017.98  5092.6 1019.51    5138 1022.95  5225.4 1023.74  5310.1 1026.01
  5413.5 1027.45  5531.1 1027.78  5641.9  1028.8  5723.1 1029.74  5834.9 1034.33
#Mann= 10 ,-1 , 0
  4435.5      .1       0  4768.4     .05       0  4789.8      .1       0
  4992.2     .07       0  4998.2      .1       0  5092.6     .16       0
  5310.1      .1       0  5531.1     .16       0  5641.9      .1       0
  5723.1     .16       0
Bank Sta=4992.2,4998.2
XS Rating Curve= 0 ,0
Exp/Cntr=0.3,0.1

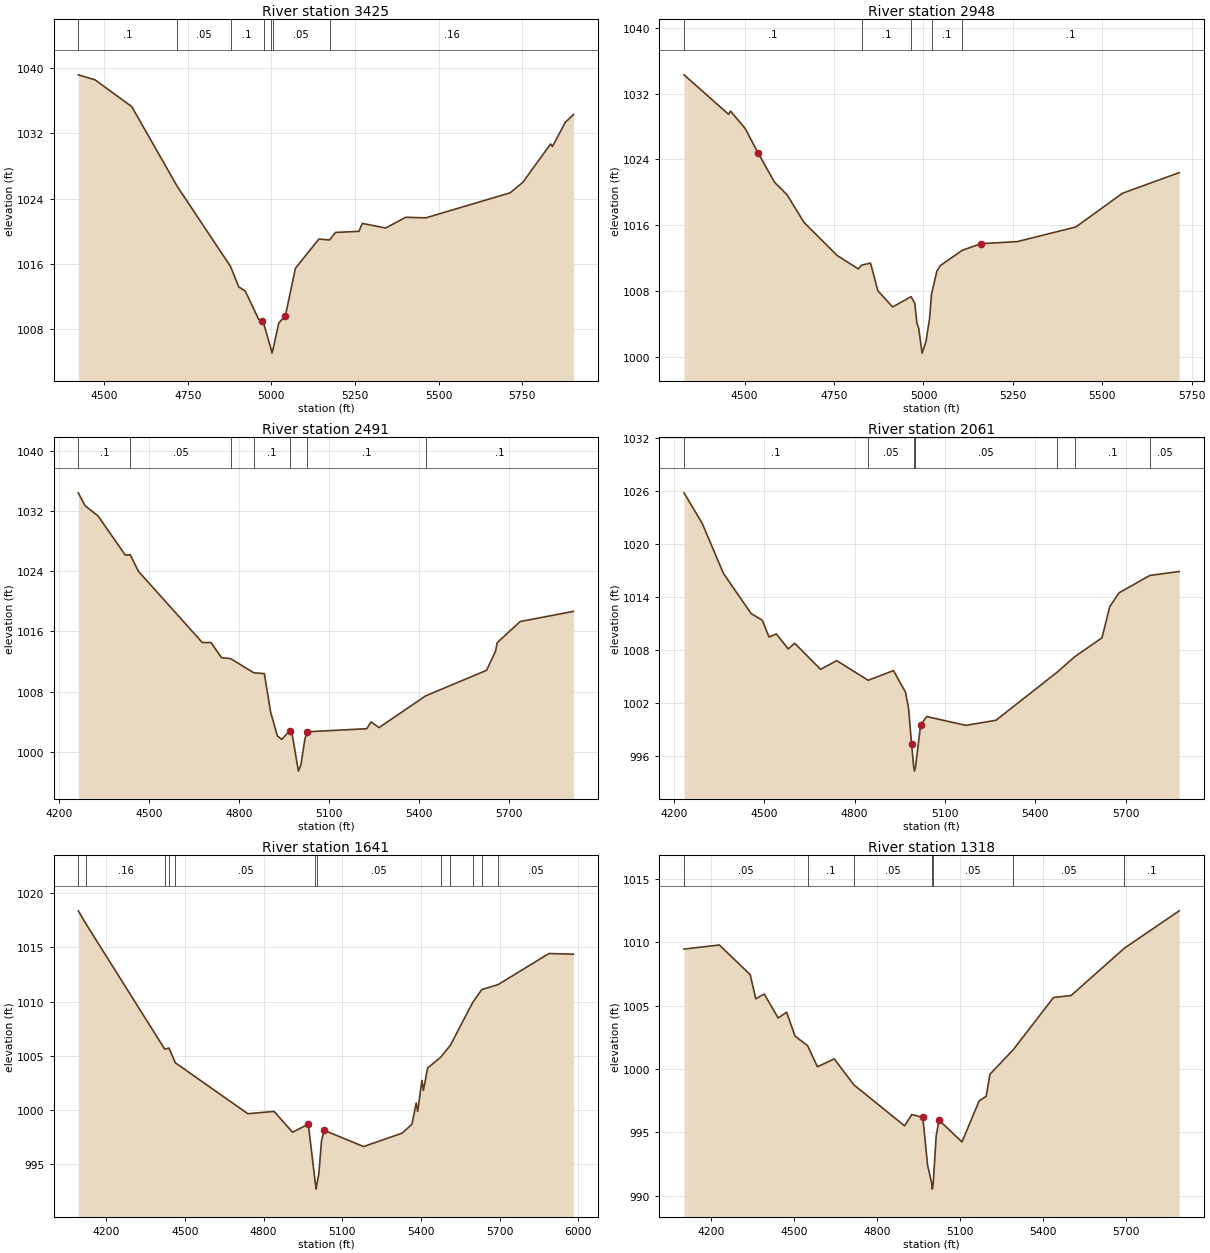
Type RM Length L Ch R = 1 ,3425    ,477,477,477
BEGIN DESCRIPTION:
UNT 1024 IN LATR 6.0
END DESCRIPTION:
XS GIS Cut Line= 3
      2958188.36     10117473.46      2956912.28     10117473.46
      2956729.95     10117568.97
#Sta/Elev= 30
    4422 1039.12  4471.9 1038.51  4581.9 1035.24  4718.4 1025.47  4877.8 1015.69
  4901.9 1013.22  4921.9 1012.68  4961.9 1009.23  4971.9 1009.06  4976.5 1008.79
  4998.9 1005.61  5001.6 1005.11  5004.9 1005.61  5021.9 1008.78  5041.9  1009.7
  5071.9 1015.48  5141.9 1019.05  5173.9 1018.94  5191.9 1019.86  5261.9 1019.99
  5271.9 1020.96  5341.9  1020.4  5401.9 1021.71  5461.9 1021.64  5714.4  1024.7
  5752.9 1026.01  5835.5 1030.67  5841.1 1030.37  5879.6 1033.32  5903.9 1034.27
#Mann= 7 ,-1 , 0
    4422      .1       0  4718.4     .05       0  4877.8      .1       0
  4976.5     .05       0  4998.9    .035       0  5004.9     .05       0
  5173.9     .16       0
Bank Sta=4971.9,5041.9
XS Rating Curve= 0 ,0
Exp/Cntr=0.3,0.1

Type RM Length L Ch R = 1 ,2948    ,457,457,457
BEGIN DESCRIPTION:
UNT 1024 IN LATR 5.0
END DESCRIPTION:
XS GIS Cut Line= 3
       2958283.8     10117169.64      2957363.67     10116935.27
      2956931.58     10116987.12
#Sta/Elev= 30
  4330.5 1034.27  4455.2 1029.47  4460.4 1029.87  4501.3 1027.76    4537 1024.82
  4583.7 1021.22  4618.8 1019.69  4666.2 1016.33  4759.1 1012.31  4818.1 1010.69
    4827 1011.15    4852  1011.4  4872.6 1008.03  4913.9 1006.07  4965.5 1007.32
  4975.8 1006.51  4981.7 1004.11  4986.8 1003.48  4996.2 1000.46  5006.8 1001.81
  5017.1 1004.65  5022.6 1007.63  5037.7 1010.45    5048 1011.12  5108.9 1012.96
  5161.5 1013.76  5262.8 1014.01  5426.3 1015.79  5556.5 1019.88  5715.2 1022.39
#Mann= 5 ,-1 , 0
  4330.5      .1       0    4827      .1       0  4965.5     .07       0
  5022.6      .1       0  5108.9      .1       0
Bank Sta=4537,5161.5
XS Rating Curve= 0 ,0
Exp/Cntr=0.3,0.1

Type RM Length L Ch R = 1 ,2491    ,430,430,430
BEGIN DESCRIPTION:
UNT 1024 IN LATR 4.0
END DESCRIPTION:
XS GIS Cut Line= 3
      2958440.95     10117082.86      2957654.47     10116460.44
      2957026.87      10116621.9
#Sta/Elev= 30
  4263.7 1034.39  4286.2 1032.68  4329.5 1031.33  4420.8 1026.11  4436.8 1026.18
  4464.1 1023.98  4677.3 1014.52  4706.1 1014.53  4741.4 1012.51  4771.6 1012.39
  4848.8 1010.51    4884  1010.4  4904.8 1005.32  4927.3 1002.14  4941.8 1001.67
  4968.9 1002.82    4977 1002.31  4997.6  997.46  5005.9  998.29  5019.3 1001.73
  5026.7 1002.68  5225.4 1003.09  5239.8 1003.99  5266.7 1003.24  5421.5 1007.44
  5625.1 1010.84  5654.9 1013.37  5660.6 1014.51  5736.9 1017.31  5914.7 1018.66
#Mann= 7 ,-1 , 0
  4263.7      .1       0  4436.8     .05       0  4771.6     .16       0
  4848.8      .1       0  4968.9     .07       0  5026.7      .1       0
  5421.5      .1       0
Bank Sta=4968.9,5026.7
XS Rating Curve= 0 ,0
Exp/Cntr=0.3,0.1

Type RM Length L Ch R = 1 ,2061    ,420,420,420
BEGIN DESCRIPTION:
UNT 1024 IN LATR 3.0
END DESCRIPTION:
XS GIS Cut Line= 4
      2958630.18     10116470.87      2958048.56     10116240.83
      2957618.88     10116219.12       2957063.4     10116414.41
#Sta/Elev= 30
  4233.5  1025.8  4294.1 1022.32  4364.4 1016.66  4456.3 1012.11  4493.4 1011.35
  4515.8 1009.45  4540.1  1009.8  4579.5  1008.1    4601 1008.74    4687 1005.78
  4740.8 1006.77    4845 1004.54  4929.1 1005.64  4969.2 1003.18  4979.2 1001.35
  4989.2  997.31  4996.2  994.74    4999  994.24  5002.2  994.74  5019.3  999.46
  5039.3 1000.43  5169.5  999.43  5269.6 1000.01    5472 1005.44  5530.9 1007.21
  5621.6 1009.36  5647.3 1012.88  5678.3 1014.46  5780.5 1016.43    5878 1016.88
#Mann= 7 ,-1 , 0
  4233.5      .1       0    4845     .05       0  4996.2     .07       0
  5002.2     .05       0    5472     .16       0  5530.9      .1       0
  5780.5     .05       0
Bank Sta=4989.2,5019.3
XS Rating Curve= 0 ,0
Exp/Cntr=0.3,0.1

Type RM Length L Ch R = 1 ,1641    ,323,323,323
BEGIN DESCRIPTION:
UNT 1024 IN LATR 2.0
END DESCRIPTION:
XS GIS Cut Line= 4
      2958712.64     10116019.48      2958152.73     10115798.12
      2957644.92     10115841.52      2956963.49     10116214.79
#Sta/Elev= 30
    4093 1018.38  4123.5 1017.13  4422.9 1005.61  4438.8 1005.72  4463.1 1004.36
  4739.5  999.66  4839.9  999.87  4910.1  997.95  4970.3  998.69  4997.4   993.2
  5000.2   992.7  5003.4   993.2  5010.5   994.1  5020.5  997.11  5030.6  998.13
  5181.1  996.63  5327.8  997.86  5365.7  998.69  5381.8 1000.65  5387.5  999.87
  5403.7 1002.73  5409.4 1001.81  5425.5 1003.88  5474.8 1004.86  5512.1 1005.97
  5597.6 1009.93  5631.9 1011.11    5694 1011.57  5888.2 1014.44  5981.7 1014.38
#Mann= 12 ,-1 , 0
    4093      .1       0  4123.5     .16       0  4422.9     .05       0
  4438.8      .1       0  4463.1     .05       0  4997.4     .07       0
  5003.4     .05       0  5474.8      .1       0  5512.1     .16       0
  5597.6      .1       0  5631.9     .16       0    5694     .05       0
Bank Sta=4970.3,5030.6
XS Rating Curve= 0 ,0
Exp/Cntr=0.3,0.1

Type RM Length L Ch R = 1 ,1318    ,290,290,290
BEGIN DESCRIPTION:
Mapping XS d6afd47c
END DESCRIPTION:
XS GIS Cut Line= 4
      2958644.59     10115593.97      2957904.96     10115479.38
       2957558.6     10115573.13      2957043.19     10116018.26
#Sta/Elev= 30
  4103.8 1009.48  4231.4  1009.8  4342.7 1007.46    4363 1005.55  4393.3 1005.93
  4443.9 1004.03  4474.3 1004.49  4504.6  1002.6  4549.9 1001.85  4585.6 1000.18
  4646.3  1000.8  4717.2  998.75  4900.4  995.51  4926.3   996.4  4966.2  996.18
  4983.3  992.42  4997.9  991.01  5000.6  990.51  5003.9  991.01  5014.4  994.72
  5024.7  995.96  5107.6  994.24  5169.8  997.49    5195  997.84  5208.6  999.59
  5292.9 1001.53  5438.2 1005.65  5501.9 1005.81  5694.3 1009.55  5892.1  1012.5
#Mann= 7 ,-1 , 0
  4103.8     .05       0  4549.9      .1       0  4717.2     .05       0
  4997.9     .07       0  5003.9     .05       0  5292.9     .05       0
  5694.3      .1       0
Bank Sta=4966.2,5024.7
XS Rating Curve= 0 ,0
Exp/Cntr=0.3,0.1

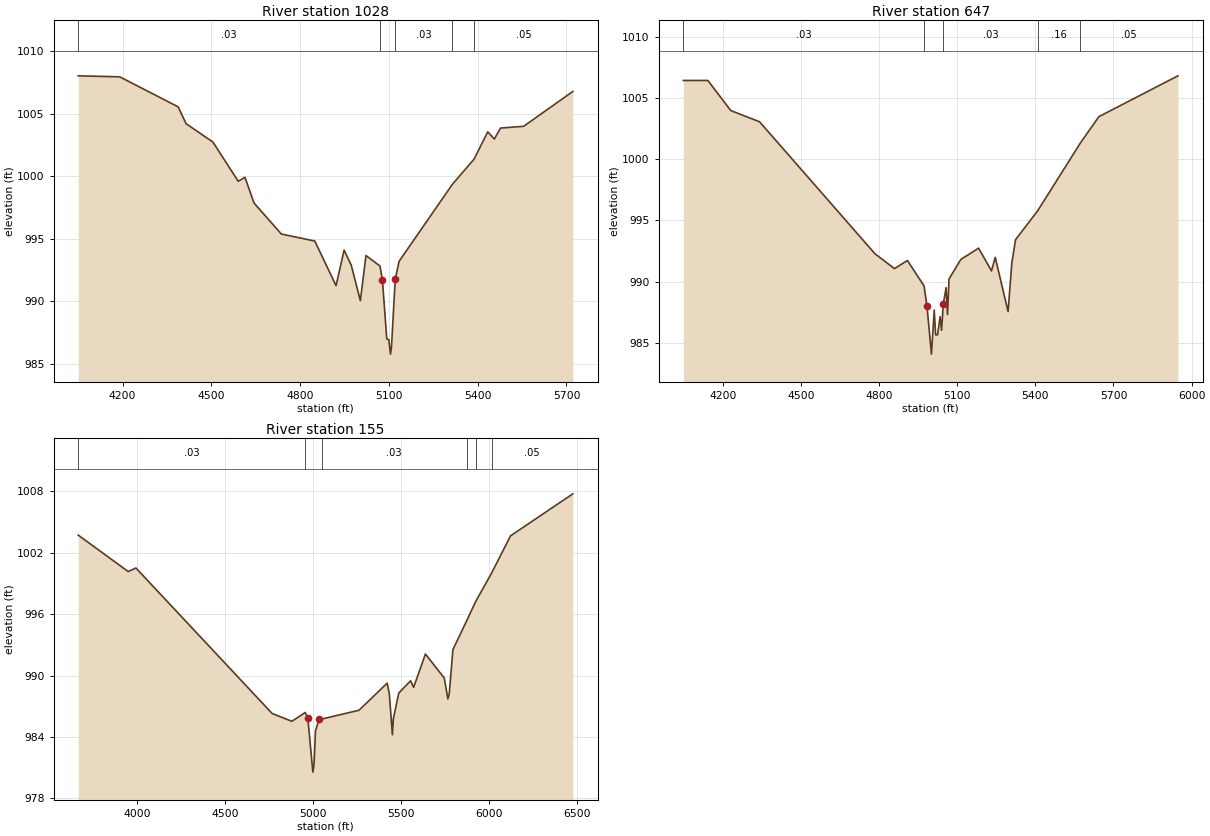
Type RM Length L Ch R = 1 ,1028    ,381,381,381
BEGIN DESCRIPTION:
Mapping XS 368c1333
END DESCRIPTION:
XS GIS Cut Line= 4
      2958637.17     10115450.87      2957686.62     10115231.68
      2957591.14     10115285.94       2957217.9      10115737.3
#Sta/Elev= 30
  4050.5 1008.04  4190.6 1007.96  4387.8 1005.56  4414.8 1004.21  4505.5 1002.74
    4591   999.6  4613.6  999.92  4644.4  997.86  4736.7  995.38  4849.6  994.82
  4921.5  991.25  4948.6  994.09  4972.8  992.89  5003.6  990.05  5022.5  993.66
  5069.9  992.82  5078.2  991.68  5092.9  986.98  5099.8  986.93  5105.3  985.77
  5108.6  986.27  5121.4  991.75  5134.5   993.2  5314.3  999.35  5387.6 1001.37
  5434.1 1003.56  5456.3 1002.98  5477.1 1003.86  5555.3    1004  5721.5 1006.79
#Mann= 5 ,-1 , 0
  4050.5     .03       0  5069.9     .03       0  5121.4     .03       0
  5314.3     .16       0  5387.6     .05       0
Bank Sta=5078.2,5121.4
XS Rating Curve= 0 ,0
Exp/Cntr=0.3,0.1

Type RM Length L Ch R = 1 ,647     ,492,492,492
BEGIN DESCRIPTION:
Mapping XS c0e4eac9
END DESCRIPTION:
XS GIS Cut Line= 5
      2958506.45      10115333.1      2957790.33      10114950.3
      2957652.31      10115012.8      2957704.39     10115124.78
      2957182.22     10115745.67
#Sta/Elev= 30
  4049.1 1006.45  4143.2 1006.45    4231 1003.99  4341.6 1003.07  4784.6  992.27
  4859.3  991.06  4909.2  991.72  4972.9  989.64    4984  988.03  5001.3  984.06
    5012  987.67  5017.3  985.64  5024.7  985.64  5034.6  987.12  5040.2  986.01
  5046.7  988.14  5057.5   989.5    5063  987.31  5068.8  990.21  5114.3  991.81
  5182.3  992.73  5231.8  990.87  5246.1  991.98  5295.5  987.54  5309.8  991.51
  5324.1  993.42  5409.1  995.79  5572.8 1001.33    5644 1003.49  5947.4 1006.83
#Mann= 5 ,-1 , 0
  4049.1     .03       0  4972.9     .03       0  5046.7     .03       0
  5409.1     .16       0  5572.8     .05       0
Bank Sta=4984,5046.7
XS Rating Curve= 0 ,0
Exp/Cntr=0.3,0.1

Type RM Length L Ch R = 1 ,155     ,0,0,0
BEGIN DESCRIPTION:
UNT 1024 IN LATR 1.0
END DESCRIPTION:
XS GIS Cut Line= 5
      2958571.01     10115177.14      2957579.94     10114483.09
      2957437.49     10114589.16      2957673.89     10115107.42
      2957132.43     10115766.85
#Sta/Elev= 30
    3665 1003.73  3948.9 1000.17  3992.5 1000.52  4766.9  986.29    4879  985.53
  4954.6  986.39  4969.2   985.9  4998.1  980.56  5004.6  981.24    5013  984.59
  5033.8  985.75  5048.4  985.75  5260.3  986.61  5420.3  989.26  5432.6  988.21
  5450.1  984.22  5455.6  985.79  5486.2  988.29  5553.3  989.49  5570.8  988.85
  5637.7  992.11  5744.6  989.76  5765.4  987.72  5772.7  988.16  5794.1  992.55
  5872.3  995.36  5923.8  997.26  6013.7 1000.02  6121.3 1003.66  6475.4 1007.77
#Mann= 6 ,-1 , 0
    3665     .03       0  4954.6     .03       0  5048.4     .03       0
  5872.3      .1       0  5923.8     .16       0  6013.7     .05       0
Bank Sta=4969.2,5033.8
XS Rating Curve= 0 ,0
Exp/Cntr=0.3,0.1

Chan Stop Cuts=-1
Use User Specified Reach Order=0
Composite Channel Slope=5