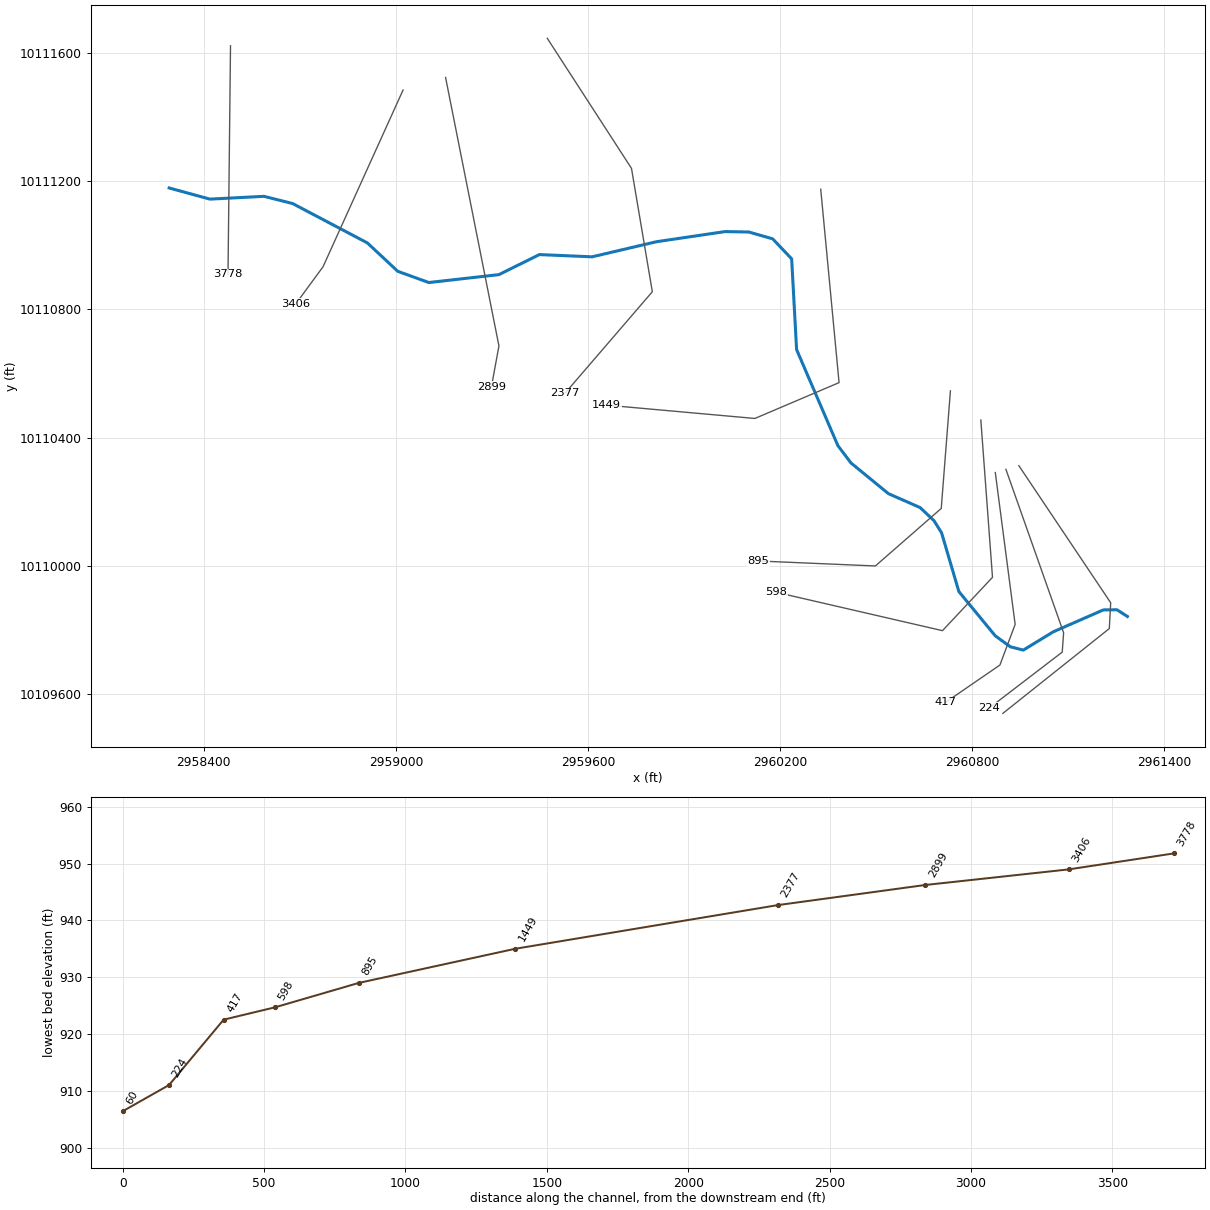
--- UNT 0025 IN LATR.prj (project) ---

Proj Title=UNT 1025 IN LATR Base Level Engineering
Current Plan=p01
Default Exp/Contr=0.3,0.1
English Units
Geom File=g01
Flow File=f01
Plan File=p01
BEGIN DESCRIPTION:
UNT 1025 IN LATR
END DESCRIPTION:

--- UNT 0025 IN LATR.p01 (plan) ---

Plan Title=Multiple Run
Short Identifier=Multiple
Geom File=g01
Flow File=f01
Subcritical Flow
K Sum by GR= 0
Std Step Tol= 0.01
Critical Tol= 0.01
Num of Std Step Trials= 20
Max Error Tol= 0.3
Flow Tol Ratio= 0.001
Split Flow NTrial= 30
Split Flow Tol= 0.02
Split Flow Ratio= 0.02
Log Output Level= 0
Friction Slope Method= 1
Unsteady Friction Slope Method= 2
Unsteady Bridges Friction Slope Method= 1
Parabolic Critical Depth
Global Vel Dist=  1 , 1 , 1
Global Log Level= 0
CheckData=True
Encroach Param= -1, 0, 0, 0
BEGIN DESCRIPTION:
Multiple Run
END DESCRIPTION:

--- UNT 0025 IN LATR.f01 (steady flow) ---

Flow Title=Multiple
Number of Profiles=7
Profile Names=10-year,25-year,50-year,1pct_min,100-year,1pct_plu,500-year
River Rch & RM= UNT 1025 IN LATR,Reach-1,3778
     659     930    1159    1057    1430    1934    2184
Boundary for River Rch & Prof#=UNT 1025 IN LATR,Reach-1,1
Up Type=0
Dn Type=3
Dn Slope=0.005
Boundary for River Rch & Prof#=UNT 1025 IN LATR,Reach-1,2
Up Type=0
Dn Type=3
Dn Slope=0.005
Boundary for River Rch & Prof#=UNT 1025 IN LATR,Reach-1,3
Up Type=0
Dn Type=3
Dn Slope=0.005
Boundary for River Rch & Prof#=UNT 1025 IN LATR,Reach-1,4
Up Type=0
Dn Type=3
Dn Slope=0.005
Boundary for River Rch & Prof#=UNT 1025 IN LATR,Reach-1,5
Up Type=0
Dn Type=3
Dn Slope=0.005
Boundary for River Rch & Prof#=UNT 1025 IN LATR,Reach-1,6
Up Type=0
Dn Type=3
Dn Slope=0.005
Boundary for River Rch & Prof#=UNT 1025 IN LATR,Reach-1,7
Up Type=0
Dn Type=3
Dn Slope=0.005

--- UNT 0025 IN LATR.g01 (geometry) ---

Geom Title=Existing Conditions

River Reach=UNT 1025 IN LATR,Reach-1
Reach XY= 30
      2958291.80     10111179.59      2958419.01     10111144.77
      2958588.16     10111153.51      2958677.33     10111131.01
      2958910.86     10111008.06      2959006.00     10110919.23
      2959103.01     10110884.24      2959321.74     10110908.86
      2959448.38     10110971.53      2959613.09     10110964.55
      2959813.94     10111011.67      2960028.67     10111043.41
      2960102.73     10111042.03      2960177.28     10111020.58
      2960236.41     10110958.16      2960251.83     10110674.76
      2960380.85     10110374.69      2960421.76     10110320.56
      2960538.83     10110224.62      2960637.57     10110181.32
      2960681.12     10110140.25      2960704.79     10110102.23
      2960758.75     10109918.84      2960872.35     10109780.66
      2960919.76     10109746.35      2960960.06     10109736.03
      2961053.70     10109793.14      2961210.07     10109861.54
      2961252.51     10109862.05      2961285.31     10109841.00

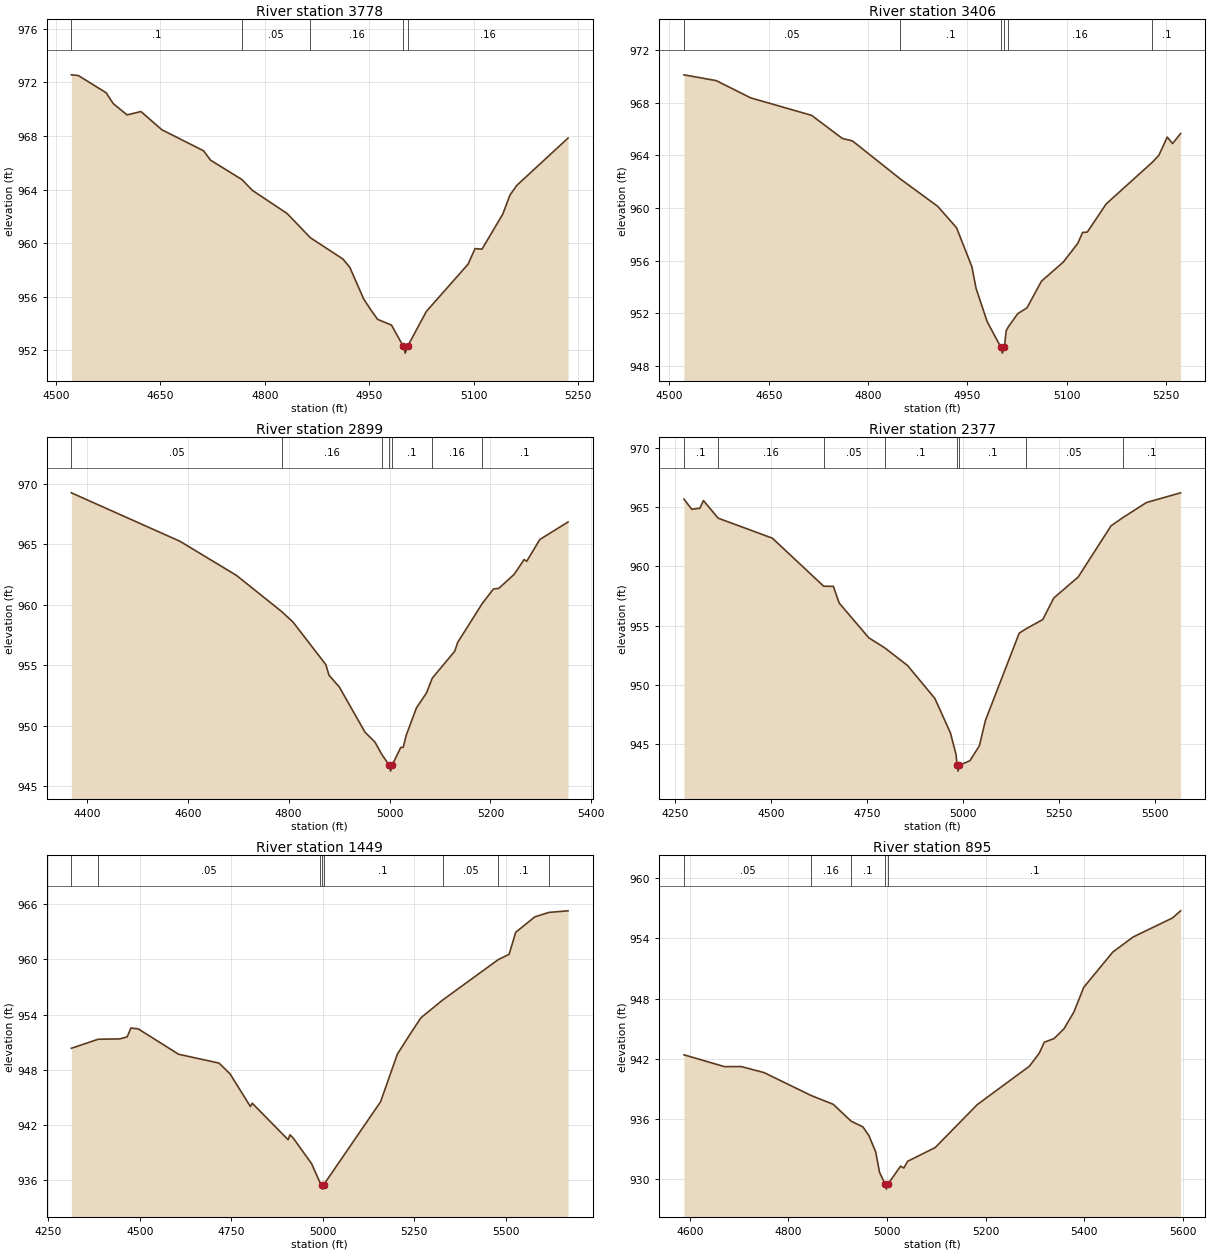
Type RM Length L Ch R = 1,3778,372,372,372
BEGIN DESCRIPTION:
UNT 1025 IN LATR 6.0
END DESCRIPTION:
XS GIS Cut Line= 2
      2958483.46     10111623.69      2958475.65     10110910.13
#Sta/Elev= 30
  4522.2  972.56  4532.2  972.51  4572.2  971.22  4582.2  970.42  4602.2  969.57
  4622.2  969.82  4652.2  968.46  4712.2  966.89  4722.2  966.19  4767.4  964.74
  4782.2  963.94  4832.2  962.21  4865.7  960.40  4912.2  958.82  4922.2  958.20
  4942.2  955.83  4952.2  955.04  4962.2  954.31  4982.2  953.88  4999.2  952.29
  5001.9  951.79  5005.2  952.29  5032.2  954.90  5092.2  958.43  5102.2  959.59
  5112.2  959.55  5142.2  962.18  5152.2  963.57  5162.2  964.31  5235.8  967.84
#Mann=5,-1,0
  4522.2     0.1       0  4767.4    0.05       0  4865.7    0.16       0
  4999.2    0.07       0  5005.2    0.16       0
Bank Sta=4999.2,5005.2
Exp/Cntr=0.3,0.1

Type RM Length L Ch R = 1,3406,507,507,507
BEGIN DESCRIPTION:
UNT 1025 IN LATR 5.0
END DESCRIPTION:
XS GIS Cut Line= 3
      2959022.51     10111485.59      2958772.52     10110933.53
      2958687.44     10110817.51
#Sta/Elev= 30
  4522.0  970.12  4570.8  969.68  4622.8  968.37  4714.9  967.04  4761.1  965.29
  4776.5  965.10  4848.5  962.22  4905.2  960.13  4933.7  958.50  4956.8  955.54
  4963.1  953.90  4979.9  951.37  5000.0  949.48  5002.8  948.98  5006.0  949.48
  5008.5  950.67  5012.0  950.99  5026.1  951.98  5040.0  952.42  5061.9  954.45
  5094.9  955.90  5116.8  957.33  5124.0  958.15  5131.0  958.17  5159.5  960.31
  5228.8  963.46  5239.0  964.00  5251.8  965.39  5259.8  964.90  5271.9  965.66
#Mann=6,-1,0
  4522.0    0.05       0  4848.5     0.1       0  5000.0    0.07       0
  5006.0     0.1       0  5012.0    0.16       0  5228.8     0.1       0
Bank Sta=5000,5006
Exp/Cntr=0.3,0.1

Type RM Length L Ch R = 1,2899,522,522,522
BEGIN DESCRIPTION:
UNT 1025 IN LATR 4.0
END DESCRIPTION:
XS GIS Cut Line= 3
      2959155.33     10111524.68      2959322.00     10110686.14
      2959298.58     10110558.62
#Sta/Elev= 30
  4369.3  969.24  4584.4  965.24  4696.5  962.42  4786.4  959.42  4808.7  958.56
  4873.8  955.04  4880.0  954.17  4900.4  953.20  4951.4  949.46  4971.0  948.65
  4985.3  947.58  4999.4  946.74  5002.1  946.24  5005.4  946.74  5022.1  948.19
  5027.2  948.21  5033.0  949.19  5053.4  951.47  5073.3  952.70  5084.7  953.92
  5129.5  956.16  5134.9  956.86  5184.1  960.11  5206.3  961.30  5216.5  961.34
  5247.0  962.50  5266.9  963.73  5272.0  963.58  5297.9  965.38  5353.9  966.83
#Mann=7,-1,0
  4369.3    0.05       0  4786.4    0.16       0  4985.3     0.1       0
  4999.4    0.07       0  5005.4     0.1       0  5084.7    0.16       0
  5184.1     0.1       0
Bank Sta=4999.4,5005.4
Exp/Cntr=0.3,0.1

Type RM Length L Ch R = 1,2377,928,928,928
BEGIN DESCRIPTION:
UNT 1025 IN LATR 3.0
END DESCRIPTION:
XS GIS Cut Line= 4
      2959473.06     10111647.05      2959736.06     10111240.83
      2959801.17     10110855.41      2959528.17     10110538.22
#Sta/Elev= 30
  4272.9  965.68  4293.4  964.82  4314.5  964.91  4323.7  965.56  4362.0  964.07
  4503.2  962.38  4636.9  958.32  4662.0  958.31  4677.2  956.90  4754.4  953.96
  4795.6  953.12  4855.3  951.62  4926.4  948.84  4966.9  945.93  4981.7  944.08
  4984.1  943.20  4986.9  942.70  4990.1  943.20  5017.6  943.58  5042.2  944.84
  5058.1  946.99  5146.0  954.36  5162.7  954.70  5207.4  955.51  5235.9  957.32
  5299.6  959.10  5385.1  963.42  5415.1  964.10  5477.3  965.39  5566.2  966.21
#Mann=8,-1,0
  4272.9     0.1       0  4362.0    0.16       0  4636.9    0.05       0
  4795.6     0.1       0  4984.1    0.07       0  4990.1     0.1       0
  5162.7    0.05       0  5415.1     0.1       0
Bank Sta=4984.1,4990.1
Exp/Cntr=0.3,0.1

Type RM Length L Ch R = 1,1449,554,554,554
BEGIN DESCRIPTION:
UNT 1025 IN LATR 2.0
END DESCRIPTION:
XS GIS Cut Line= 4
      2960327.21     10111175.72      2960384.50     10110571.56
      2960121.48     10110459.58      2959657.89     10110501.25
#Sta/Elev= 30
  4312.6  950.34  4385.9  951.32  4445.2  951.36  4465.3  951.58  4475.3  952.54
  4495.4  952.45  4605.9  949.69  4716.4  948.73  4746.5  947.56  4802.2  944.01
  4807.2  944.37  4905.4  940.40  4910.4  940.93  4919.5  940.57  4969.5  937.80
  4993.7  935.64  4997.0  935.53  4999.7  935.03  5003.0  935.53  5158.1  944.52
  5204.3  949.72  5238.5  951.85  5268.6  953.66  5327.8  955.58  5480.1  959.98
  5509.6  960.55  5527.8  962.95  5579.9  964.62  5618.7  965.11  5670.8  965.28
#Mann=8,-1,0
  4312.6     0.1       0  4385.9    0.05       0  4993.7     0.1       0
  4997.0    0.07       0  5003.0     0.1       0  5327.8    0.05       0
  5480.1     0.1       0  5618.7    0.05       0
Bank Sta=4997,5003
Exp/Cntr=0.3,0.1

Type RM Length L Ch R = 1,895,297,297,297
BEGIN DESCRIPTION:
Mapping XS 60bd1415
END DESCRIPTION:
XS GIS Cut Line= 4
      2960732.36     10110545.76      2960703.71     10110178.53
      2960497.98     10109998.84      2960132.11     10110014.41
#Sta/Elev= 30
  4588.1  942.40  4670.4  941.22  4704.0  941.23  4750.6  940.63  4846.4  938.34
  4891.0  937.47  4927.6  935.78  4951.2  935.22  4963.4  934.35  4977.3  932.72
  4984.9  930.71  4996.2  929.52  4998.9  929.02  5002.2  929.52  5027.7  931.31
  5034.3  931.12  5041.9  931.79  5097.9  933.16  5183.3  937.44  5289.2  941.27
  5309.2  942.57  5319.2  943.65  5339.2  944.02  5359.2  944.99  5379.3  946.66
  5399.3  949.12  5458.2  952.63  5499.4  954.13  5579.4  956.03  5595.8  956.74
#Mann=5,-1,0
  4588.1    0.05       0  4846.4    0.16       0  4927.6     0.1       0
  4996.2    0.07       0  5002.2     0.1       0
Bank Sta=4996.2,5002.2
Exp/Cntr=0.3,0.1

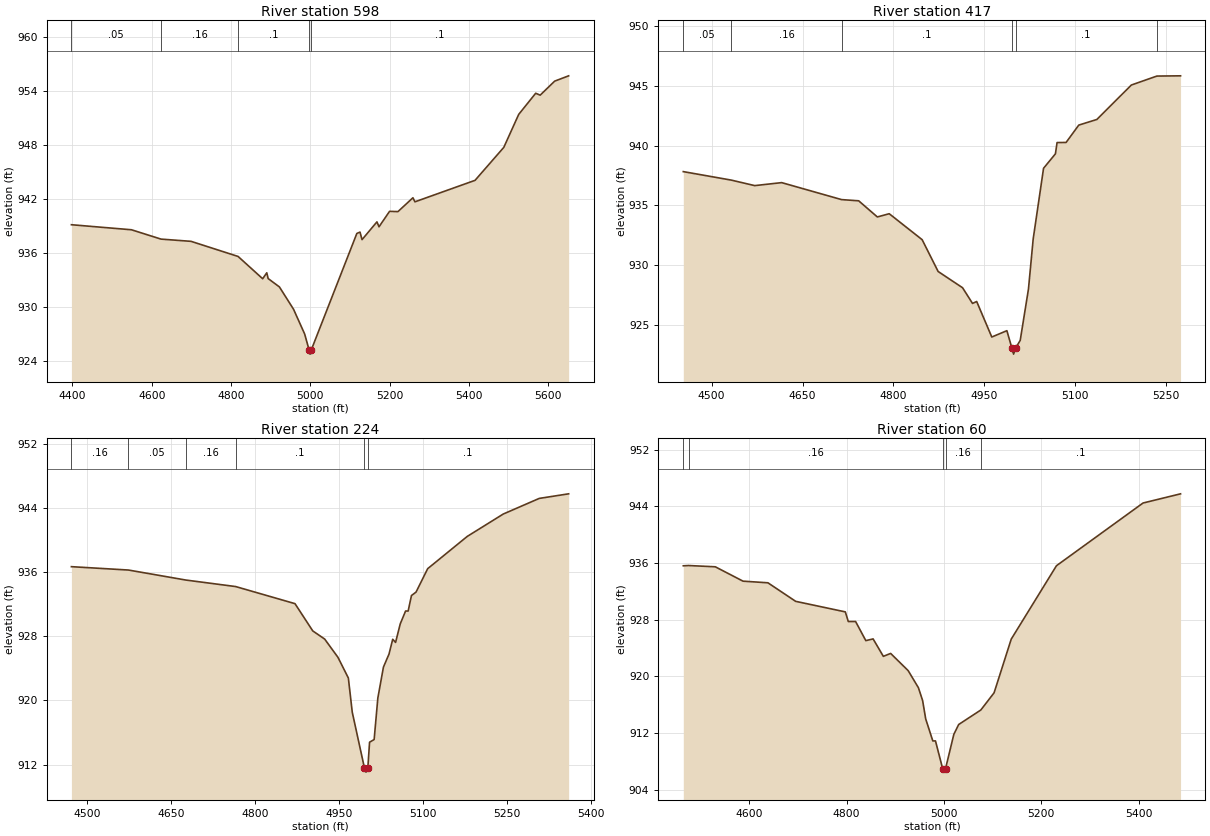
Type RM Length L Ch R = 1,598,181,181,181
BEGIN DESCRIPTION:
Mapping XS 850e2b8b
END DESCRIPTION:
XS GIS Cut Line= 4
      2960827.34     10110454.75      2960863.80     10109963.38
      2960707.55     10109796.71      2960188.47     10109916.50
#Sta/Elev= 30
  4397.4  939.12  4548.8  938.56  4623.4  937.52  4699.2  937.27  4817.7  935.59
  4879.7  933.11  4890.1  933.77  4893.5  933.13  4921.9  932.20  4957.5  929.72
  4985.6  926.96  4996.6  925.22  4999.3  924.72  5002.6  925.22  5117.2  938.15
  5125.2  938.30  5130.3  937.46  5167.9  939.44  5173.1  938.89  5199.7  940.61
  5220.9  940.58  5258.6  942.12  5263.7  941.67  5415.3  944.06  5487.8  947.73
  5525.4  951.40  5568.2  953.75  5579.5  953.54  5616.1  955.10  5651.3  955.69
#Mann=5,-1,0
  4397.4    0.05       0  4623.4    0.16       0  4817.7     0.1       0
  4996.6    0.07       0  5002.6     0.1       0
Bank Sta=4996.6,5002.6
Exp/Cntr=0.3,0.1

Type RM Length L Ch R = 1,417,193,193,193
BEGIN DESCRIPTION:
Mapping XS 9a475991
END DESCRIPTION:
XS GIS Cut Line= 4
      2960872.56     10110290.57      2960934.56     10109816.18
      2960886.98     10109689.30      2960716.84     10109572.51
#Sta/Elev= 30
  4453.3  937.82  4532.5  937.11  4571.1  936.65  4615.6  936.90  4714.4  935.48
  4742.6  935.38  4773.4  934.03  4793.0  934.30  4847.3  932.13  4873.7  929.47
  4914.0  928.11  4930.4  926.80  4937.3  926.96  4962.2  923.99  4987.1  924.52
  4995.4  923.06  4998.2  922.56  5001.4  923.06  5009.1  923.71  5022.7  928.00
  5030.5  932.19  5047.6  938.10  5067.2  939.31  5069.9  940.25  5084.8  940.26
  5105.7  941.71  5135.5  942.18  5192.4  945.06  5234.5  945.81  5273.6  945.83
#Mann=6,-1,0
  4453.3    0.05       0  4532.5    0.16       0  4714.4     0.1       0
  4995.4    0.07       0  5001.4     0.1       0  5234.5    0.16       0
Bank Sta=4995.4,5001.4
Exp/Cntr=0.3,0.1

Type RM Length L Ch R = 1,224,164,164,164
BEGIN DESCRIPTION:
Mapping XS 9f348032
END DESCRIPTION:
XS GIS Cut Line= 4
      2960905.73     10110300.59      2961085.95     10109790.22
      2961081.62     10109729.67      2960853.81     10109555.20
#Sta/Elev= 30
  4471.8  936.68  4573.8  936.26  4676.6  935.01  4765.5  934.20  4871.5  932.07
  4903.3  928.67  4924.5  927.66  4948.3  925.38  4966.9  922.80  4973.9  918.53
  4995.7  911.57  4998.5  911.07  5001.7  911.57  5004.8  914.80  5013.0  915.13
  5019.6  920.30  5029.6  924.16  5039.6  925.79  5046.2  927.63  5051.3  927.24
  5059.7  929.56  5069.2  931.15  5073.8  931.15  5079.7  933.08  5087.9  933.51
  5108.7  936.43  5179.4  940.45  5243.8  943.24  5308.2  945.19  5360.7  945.76
#Mann=6,-1,0
  4471.8    0.16       0  4573.8    0.05       0  4676.6    0.16       0
  4765.5     0.1       0  4995.7    0.07       0  5001.7     0.1       0
Bank Sta=4995.7,5001.7
Exp/Cntr=0.3,0.1

Type RM Length L Ch R = 1,60,0,0,0
BEGIN DESCRIPTION:
UNT 1025 IN LATR 1.0
END DESCRIPTION:
XS GIS Cut Line= 4
      2960946.11     10110312.12      2961233.01     10109883.94
      2961228.68     10109803.20      2960896.15     10109538.33
#Sta/Elev= 30
  4464.7  935.61  4475.4  935.65  4530.4  935.47  4587.4  933.44  4638.5  933.21
  4695.5  930.59  4797.5  929.10  4803.6  927.74  4818.6  927.74  4839.6  925.04
  4854.6  925.28  4875.6  922.82  4890.6  923.23  4926.6  920.80  4947.6  918.39
  4956.3  916.57  4962.6  913.98  4977.2  910.87  4982.7  910.87  4997.4  906.96
  5000.1  906.46  5003.4  906.96  5020.4  911.80  5030.4  913.19  5075.9  915.24
  5103.1  917.67  5138.3  925.25  5231.2  935.62  5409.0  944.48  5486.1  945.78
#Mann=5,-1,0
  4464.7    0.05       0  4475.4    0.16       0  4997.4    0.07       0
  5003.4    0.16       0  5075.9     0.1       0
Bank Sta=4997.4,5003.4
Exp/Cntr=0.3,0.1

Chan Stop Cuts=-1