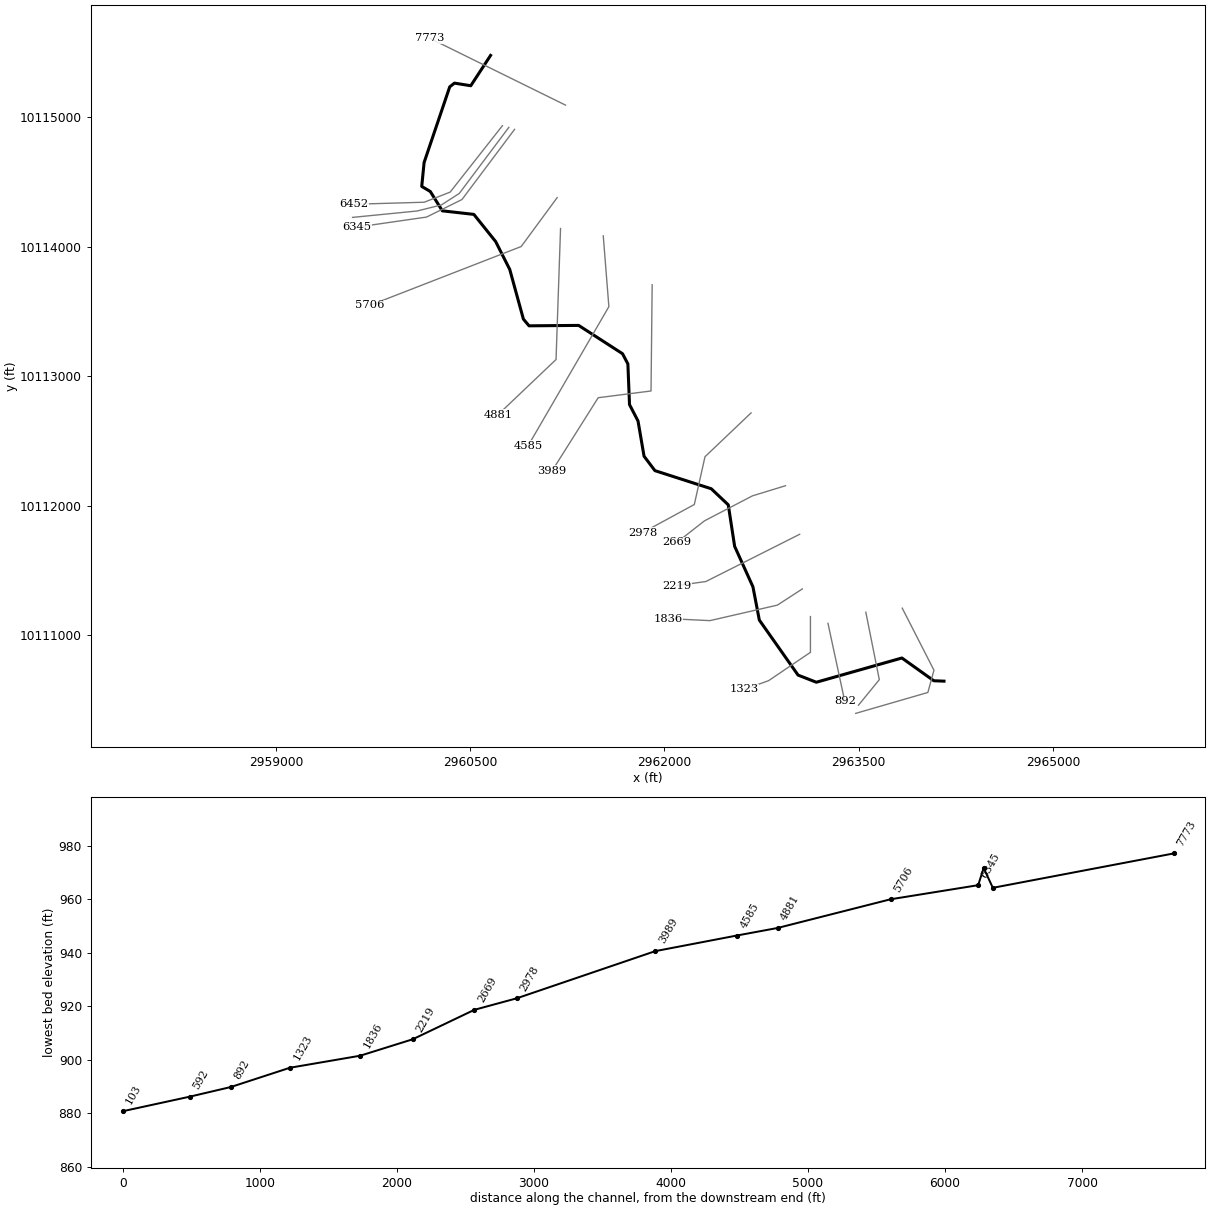
--- UNT 0026 IN LATR.prj (project) ---

Proj Title=UNT 1026 IN LATR Base Level Engineering
Current Plan=p01
Default Exp/Contr=0.3,0.1
English Units
Geom File=g01
Flow File=f01
Plan File=p01
BEGIN DESCRIPTION:
UNT 1026 IN LATR
END DESCRIPTION:

--- UNT 0026 IN LATR.p01 (plan) ---

Plan Title=Multiple Run
Short Identifier=Multiple
Geom File=g01
Flow File=f01
Subcritical Flow
K Sum by GR= 0
Std Step Tol= 0.01
Critical Tol= 0.01
Num of Std Step Trials= 20
Max Error Tol= 0.3
Flow Tol Ratio= 0.001
Split Flow NTrial= 30
Split Flow Tol= 0.02
Split Flow Ratio= 0.02
Log Output Level= 0
Friction Slope Method= 1
Unsteady Friction Slope Method= 2
Unsteady Bridges Friction Slope Method= 1
Parabolic Critical Depth
Global Vel Dist=  1 , 1 , 1
Global Log Level= 0
CheckData=True
Encroach Param= -1, 0, 0, 0
BEGIN DESCRIPTION:
Multiple Run
END DESCRIPTION:

--- UNT 0026 IN LATR.f01 (steady flow) ---

Flow Title=Multiple
Number of Profiles=7
Profile Names=10-year,25-year,50-year,1pct_min,100-year,1pct_plu,500-year
River Rch & RM= UNT 1026 IN LATR,Reach-1,7773
     987    1448    1854    1739    2352    3181    3797
River Rch & RM= UNT 1026 IN LATR,Reach-1,4881
    1165    1721    2213    2082    2815    3808    4576
Boundary for River Rch & Prof#=UNT 1026 IN LATR,Reach-1,1
Up Type=0
Dn Type=3
Dn Slope=0.005
Boundary for River Rch & Prof#=UNT 1026 IN LATR,Reach-1,2
Up Type=0
Dn Type=3
Dn Slope=0.005
Boundary for River Rch & Prof#=UNT 1026 IN LATR,Reach-1,3
Up Type=0
Dn Type=3
Dn Slope=0.005
Boundary for River Rch & Prof#=UNT 1026 IN LATR,Reach-1,4
Up Type=0
Dn Type=3
Dn Slope=0.005
Boundary for River Rch & Prof#=UNT 1026 IN LATR,Reach-1,5
Up Type=0
Dn Type=3
Dn Slope=0.005
Boundary for River Rch & Prof#=UNT 1026 IN LATR,Reach-1,6
Up Type=0
Dn Type=3
Dn Slope=0.005
Boundary for River Rch & Prof#=UNT 1026 IN LATR,Reach-1,7
Up Type=0
Dn Type=3
Dn Slope=0.005

--- UNT 0026 IN LATR.g01 (geometry) ---

Geom Title=Existing Conditions

River Reach=UNT 1026 IN LATR,Reach-1
Reach XY= 30
      2960657.15     10115475.69      2960504.20     10115241.49
      2960378.20     10115261.69      2960341.74     10115232.99
      2960143.91     10114648.91      2960125.56     10114464.17
      2960191.83     10114424.78      2960284.54     10114275.47
      2960528.11     10114248.04      2960696.64     10114037.88
      2960805.30     10113822.73      2960910.60     10113439.48
      2960954.13     10113387.56      2961337.23     10113390.82
      2961676.01     10113172.24      2961717.43     10113093.32
      2961730.01     10112779.38      2961795.73     10112652.69
      2961842.36     10112380.57      2961926.19     10112269.37
      2962361.39     10112129.40      2962492.71     10112005.11
      2962541.75     10111685.05      2962683.22     10111371.98
      2962732.44     10111115.38      2963031.68     10110690.33
      2963172.60     10110635.34      2963833.47     10110822.48
      2964079.83     10110646.79      2964158.47     10110643.73

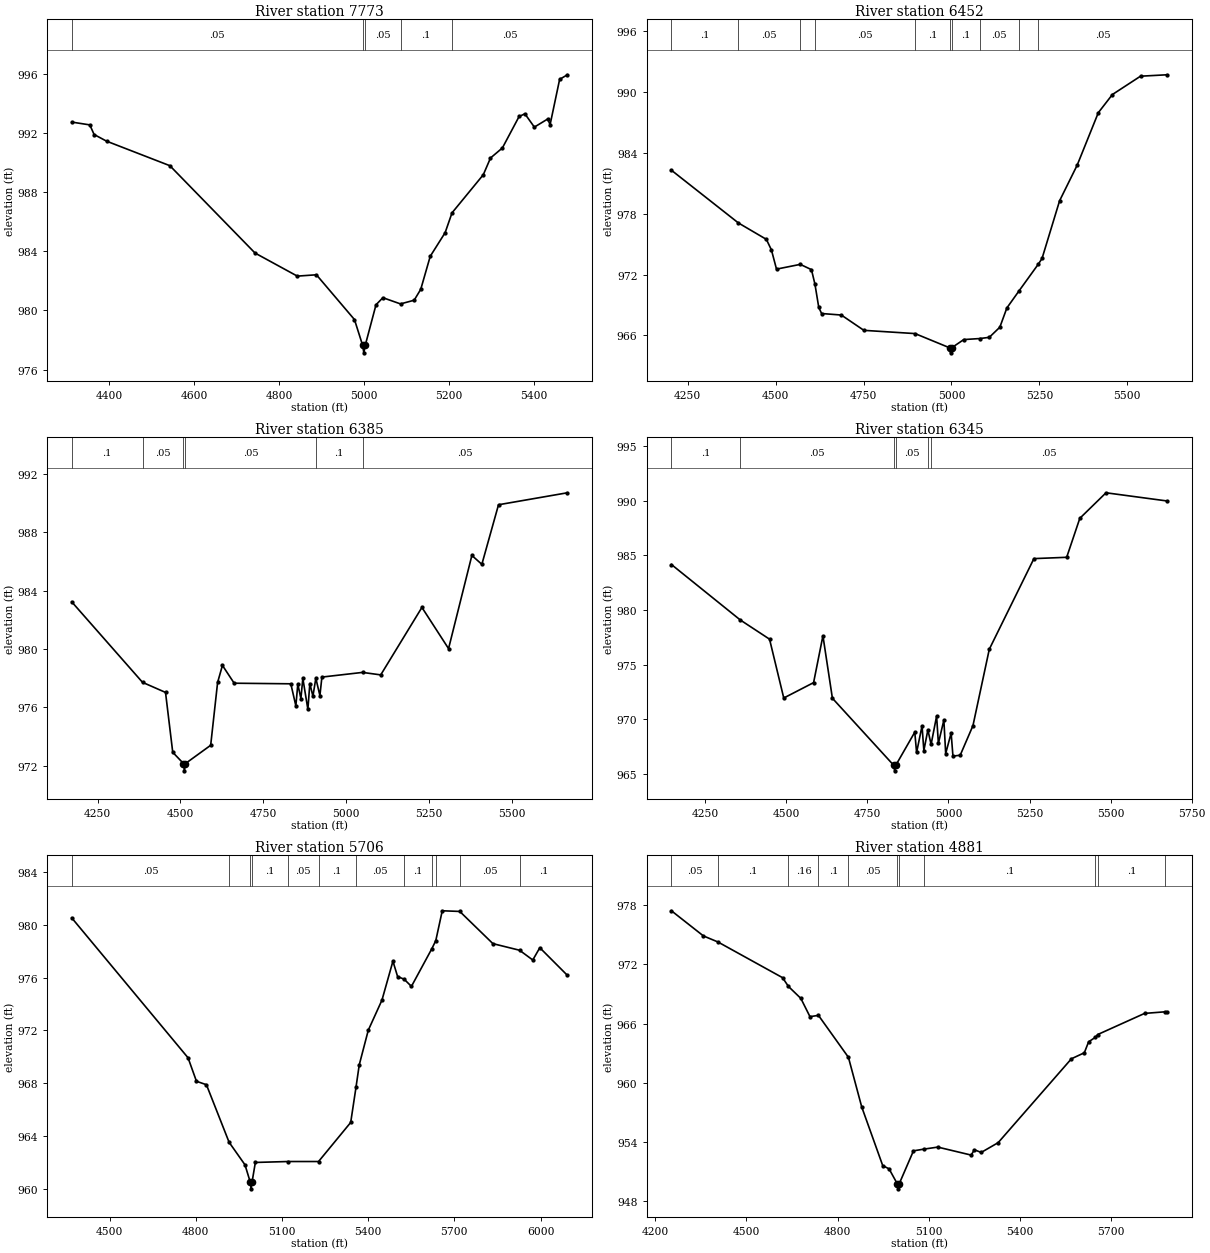
Type RM Length L Ch R = 1,7773,1321,1321,1321
BEGIN DESCRIPTION:
UNT 1026 IN LATR 16.0
END DESCRIPTION:
XS GIS Cut Line= 2
      2961235.67     10115091.94      2960188.76     10115607.57
#Sta/Elev= 30
  4311.2  992.74  4353.7  992.55  4363.8  991.90  4393.1  991.45  4542.2  989.79
  4742.8  983.88  4842.3  982.32  4887.3  982.41  4976.9  979.38  4996.2  977.63
  4999.0  977.13  5002.2  977.63  5027.6  980.38  5043.8  980.86  5085.3  980.44
  5117.5  980.69  5133.0  981.43  5155.3  983.66  5190.4  985.26  5206.6  986.60
  5280.3  989.18  5297.2  990.31  5325.2  990.99  5364.6  993.12  5378.2  993.30
  5400.5  992.40  5432.0  992.95  5437.5  992.56  5460.0  995.63  5478.2  995.94
#Mann=5,-1,0
  4311.2    0.05       0  4996.2   0.035       0  5002.2    0.05       0
  5085.3     0.1       0  5206.6    0.05       0
Bank Sta=4996.2,5002.2
Exp/Cntr=0.3,0.1

Type RM Length L Ch R = 1,6452,67,67,67
BEGIN DESCRIPTION:
Mapping XS 57fe31ad
END DESCRIPTION:
XS GIS Cut Line= 4
      2960748.67     10114933.13      2960345.00     10114420.08
      2960144.48     10114341.95      2959603.13     10114326.34
#Sta/Elev= 30
  4203.6  982.29  4394.0  977.09  4473.6  975.47  4488.0  974.43  4502.5  972.53
  4570.1  973.00  4601.9  972.48  4611.8  971.05  4622.7  968.75  4630.8  968.15
  4686.9  968.00  4751.0  966.49  4896.6  966.17  4994.7  964.77  4997.5  964.27
  5000.7  964.77  5035.2  965.58  5080.6  965.68  5107.7  965.80  5137.7  966.80
  5157.7  968.70  5191.6  970.35  5246.9  973.01  5257.7  973.58  5307.7  979.28
  5357.8  982.80  5417.8  987.97  5457.8  989.76  5537.8  991.57  5613.2  991.71
#Mann=10,-1,0
  4203.6     0.1       0  4394.0    0.05       0  4570.1    0.16       0
  4611.8    0.05       0  4896.6     0.1       0  4994.7    0.07       0
  5000.7     0.1       0  5080.6    0.05       0  5191.6     0.1       0
  5246.9    0.05       0
Bank Sta=4994.7,5000.7
Exp/Cntr=0.3,0.1

Type RM Length L Ch R = 1,6385,40,40,40
BEGIN DESCRIPTION:
UNT 1026 IN LATR 15.0
END DESCRIPTION:
XS GIS Cut Line= 5
      2960798.15     10114920.10      2960415.32     10114409.66
      2960277.30     10114321.12      2960089.80     10114274.25
      2959591.63     10114224.95
#Sta/Elev= 30
  4172.1  983.23  4385.7  977.72  4455.1  977.03  4476.9  972.93  4509.3  972.16
  4512.0  971.66  4515.3  972.16  4591.4  973.41  4612.3  977.71  4626.9  978.88
  4662.3  977.66  4833.3  977.62  4848.5  976.11  4854.4  977.60  4863.7  976.61
  4869.6  977.99  4884.8  975.87  4890.7  977.64  4900.0  976.77  4908.8  978.00
  4921.1  976.81  4927.1  978.08  5049.7  978.40  5104.7  978.23  5229.0  982.85
  5309.4  980.03  5379.8  986.41  5409.9  985.80  5460.2  989.88  5668.0  990.70
#Mann=6,-1,0
  4172.1     0.1       0  4385.7    0.05       0  4509.3    0.07       0
  4515.3    0.05       0  4908.8     0.1       0  5049.7    0.05       0
Bank Sta=4509.3,4515.3
Exp/Cntr=0.3,0.1

Type RM Length L Ch R = 1,6345,639,639,639
BEGIN DESCRIPTION:
UNT 1026 IN LATR 14.0
END DESCRIPTION:
XS GIS Cut Line= 4
      2960842.38     10114904.42      2960436.15     10114362.79
      2960162.71     10114227.37      2959622.28     10114149.42
#Sta/Elev= 30
  4145.8  984.16  4358.1  979.08  4448.4  977.32  4492.2  971.93  4584.2  973.34
  4613.0  977.63  4642.2  971.91  4831.5  965.76  4834.2  965.26  4837.5  965.76
  4896.2  968.80  4901.8  966.94  4918.6  969.37  4924.2  967.12  4936.6  969.01
  4946.5  967.68  4963.5  970.27  4969.0  967.78  4985.9  969.91  4991.5  966.84
  5008.3  968.72  5013.9  966.61  5036.3  966.69  5075.6  969.40  5126.0  976.40
  5263.6  984.70  5364.6  984.82  5405.1  988.39  5485.9  990.73  5674.0  989.98
#Mann=6,-1,0
  4145.8     0.1       0  4358.1    0.05       0  4831.5   0.035       0
  4837.5    0.05       0  4936.6     0.1       0  4946.5    0.05       0
Bank Sta=4831.5,4837.5
Exp/Cntr=0.3,0.1

Type RM Length L Ch R = 1,5706,825,825,825
BEGIN DESCRIPTION:
UNT 1026 IN LATR 13.0
END DESCRIPTION:
XS GIS Cut Line= 3
      2961171.38     10114377.53      2960893.62     10113999.94
      2959722.60     10113544.55
#Sta/Elev= 30
  4368.3  980.52  4773.1  969.92  4802.4  968.14  4837.1  967.88  4916.0  963.52
  4971.3  961.81  4989.8  960.49  4992.5  959.99  4995.8  960.49  5007.4  961.99
  5121.2  962.06  5227.4  962.06  5339.3  965.02  5357.7  967.68  5369.1  969.39
  5400.5  972.01  5448.1  974.29  5486.3  977.24  5502.5  976.08  5525.5  975.87
  5550.7  975.33  5621.9  978.19  5635.5  978.80  5658.0  981.06  5719.0  981.01
  5834.3  978.57  5927.0  978.07  5973.1  977.33  5997.6  978.26  6093.5  976.17
#Mann=12,-1,0
  4368.3    0.05       0  4916.0     0.1       0  4989.8    0.07       0
  4995.8     0.1       0  5121.2    0.05       0  5227.4     0.1       0
  5357.7    0.05       0  5525.5     0.1       0  5621.9    0.05       0
  5635.5     0.1       0  5719.0    0.05       0  5927.0     0.1       0
Bank Sta=4989.8,4995.8
Exp/Cntr=0.3,0.1

Type RM Length L Ch R = 1,4881,296,296,296
BEGIN DESCRIPTION:
UNT 1026 IN LATR 11.0
END DESCRIPTION:
XS GIS Cut Line= 3
      2961197.44     10114138.85      2961162.71     10113127.54
      2960715.64     10112702.18
#Sta/Elev= 30
  4254.1  977.44  4359.3  974.89  4406.9  974.28  4619.4  970.66  4638.8  969.77
  4679.5  968.56  4709.5  966.71  4737.4  966.84  4835.9  962.59  4879.6  957.56
  4948.6  951.62  4969.6  951.28  4996.7  949.76  4999.4  949.26  5002.7  949.76
  5049.7  953.11  5083.0  953.28  5129.7  953.49  5239.4  952.68  5249.8  953.22
  5272.4  952.95  5328.1  953.94  5568.8  962.44  5611.3  963.05  5625.4  964.16
  5646.8  964.60  5655.5  964.90  5809.4  967.04  5876.2  967.20  5883.1  967.15
#Mann=11,-1,0
  4254.1    0.05       0  4406.9     0.1       0  4638.8    0.16       0
  4737.4     0.1       0  4835.9    0.05       0  4996.7   0.035       0
  5002.7    0.05       0  5083.0     0.1       0  5646.8    0.05       0
  5655.5     0.1       0  5876.2    0.16       0
Bank Sta=4996.7,5002.7
Exp/Cntr=0.3,0.1

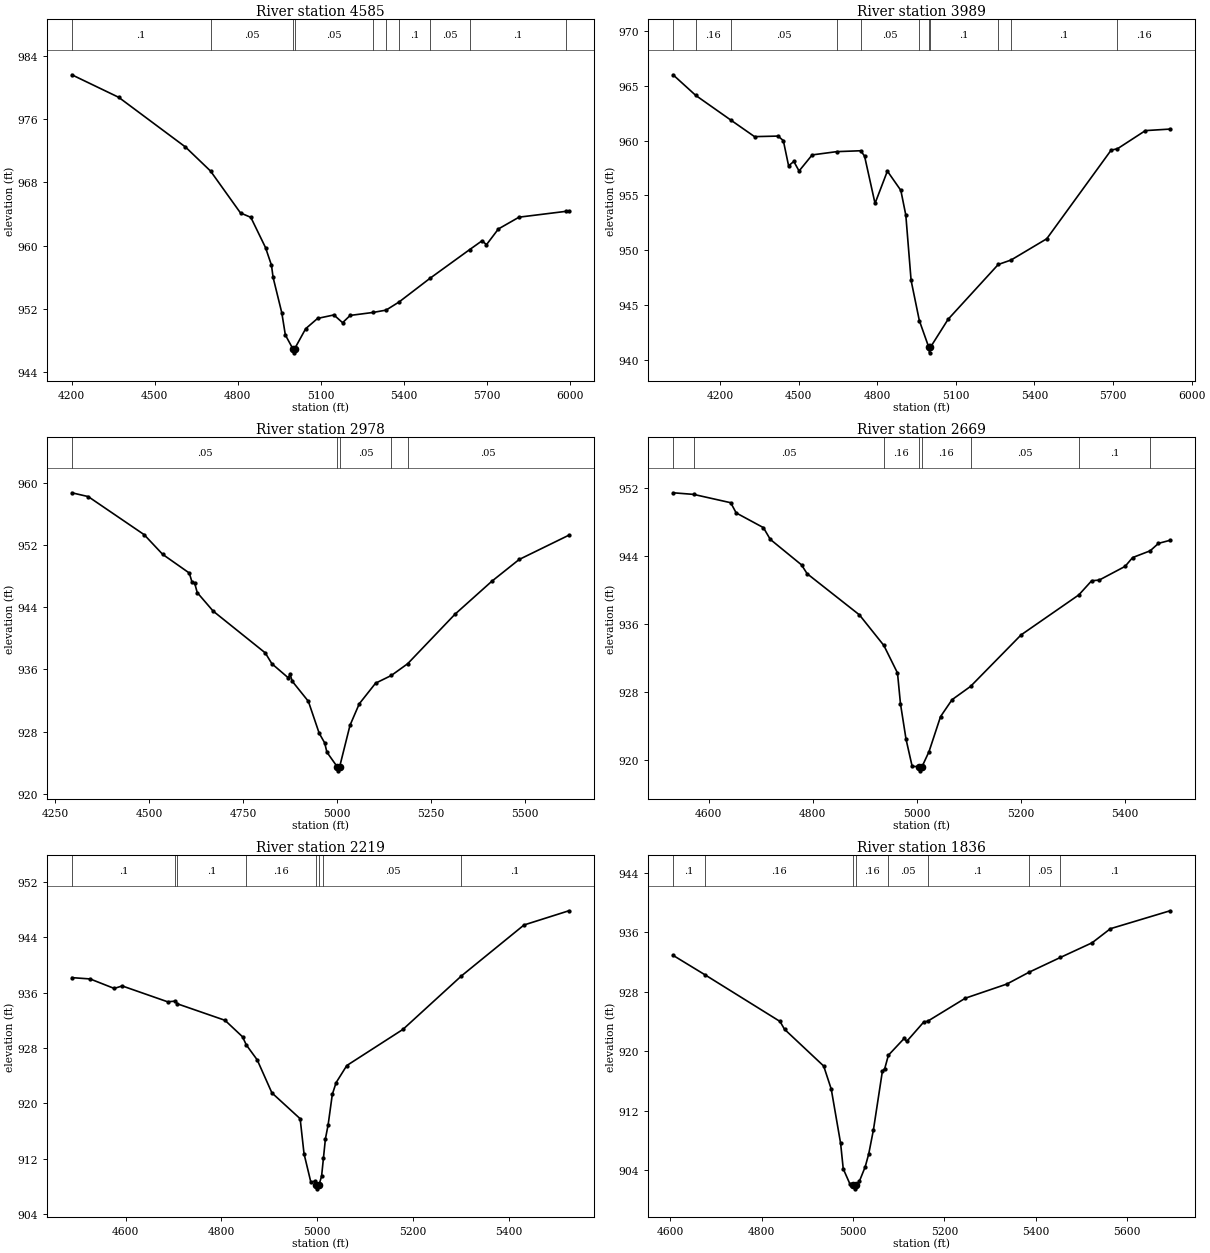
Type RM Length L Ch R = 1,4585,596,596,596
BEGIN DESCRIPTION:
UNT 1026 IN LATR 10.0
END DESCRIPTION:
XS GIS Cut Line= 3
      2961527.29     10114082.43      2961570.70     10113535.53
      2960945.70     10112459.15
#Sta/Elev= 30
  4201.0  981.60  4370.2  978.75  4611.0  972.47  4701.5  969.43  4809.6  964.13
  4846.8  963.58  4899.8  959.76  4921.4  957.52  4927.1  956.00  4958.6  951.51
  4971.4  948.71  4998.7  946.95  5001.4  946.45  5004.7  946.95  5044.7  949.50
  5087.7  950.80  5146.5  951.24  5178.0  950.26  5205.3  951.18  5286.8  951.55
  5334.7  951.85  5381.8  952.88  5494.8  955.91  5636.4  959.50  5681.3  960.62
  5697.1  960.12  5740.1  962.11  5814.6  963.60  5982.3  964.33  5994.3  964.32
#Mann=10,-1,0
  4201.0     0.1       0  4701.5    0.05       0  4998.7   0.035       0
  5004.7    0.05       0  5286.8     0.1       0  5334.7    0.16       0
  5381.8     0.1       0  5494.8    0.05       0  5636.4     0.1       0
  5982.3    0.16       0
Bank Sta=4998.7,5004.7
Exp/Cntr=0.3,0.1

Type RM Length L Ch R = 1,3989,1011,1011,1011
BEGIN DESCRIPTION:
UNT 1026 IN LATR 9.0
END DESCRIPTION:
XS GIS Cut Line= 4
      2961904.90     10113704.77      2961896.22     10112884.49
      2961488.23     10112832.41      2961133.09     10112269.38
#Sta/Elev= 30
  4020.2  966.01  4107.2  964.12  4240.9  961.87  4331.3  960.36  4421.3  960.41
  4441.3  959.99  4461.3  957.70  4481.3  958.09  4501.3  957.22  4551.3  958.69
  4645.6  958.99  4736.7  959.07  4751.3  958.58  4791.3  954.26  4838.4  957.21
  4889.8  955.45  4908.8  953.19  4929.0  947.22  4960.5  943.55  4996.6  941.11
  4999.3  940.61  5002.6  941.11  5070.1  943.67  5261.6  948.68  5310.7  949.09
  5446.8  951.03  5692.7  959.13  5716.6  959.25  5823.4  960.91  5917.5  961.05
#Mann=11,-1,0
  4020.2     0.1       0  4107.2    0.16       0  4240.9    0.05       0
  4645.6     0.1       0  4736.7    0.05       0  4960.5     0.1       0
  4996.6    0.07       0  5002.6     0.1       0  5261.6    0.16       0
  5310.7     0.1       0  5716.6    0.16       0
Bank Sta=4996.6,5002.6
Exp/Cntr=0.3,0.1

Type RM Length L Ch R = 1,2978,309,309,309
BEGIN DESCRIPTION:
UNT 1026 IN LATR 7.0
END DESCRIPTION:
XS GIS Cut Line= 4
      2962668.77     10112715.20      2962312.89     10112376.68
      2962230.42     10112007.75      2961832.32     10111791.39
#Sta/Elev= 30
  4294.4  958.70  4338.0  958.21  4486.8  953.32  4536.1  950.79  4606.9  948.39
  4613.8  947.28  4621.1  947.11  4628.0  945.88  4670.4  943.50  4809.1  938.13
  4826.6  936.74  4870.0  934.94  4875.1  935.38  4880.8  934.49  4923.7  931.91
  4952.5  927.81  4967.1  926.57  4973.0  925.38  5000.8  923.48  5003.5  922.98
  5006.8  923.48  5034.5  928.83  5059.1  931.59  5102.5  934.24  5144.4  935.23
  5187.9  936.74  5313.8  943.10  5411.7  947.33  5484.5  950.13  5616.7  953.25
#Mann=5,-1,0
  4294.4    0.05       0  5000.8   0.035       0  5006.8    0.05       0
  5144.4    0.16       0  5187.9    0.05       0
Bank Sta=5000.8,5006.8
Exp/Cntr=0.3,0.1

Type RM Length L Ch R = 1,2669,450,450,450
BEGIN DESCRIPTION:
UNT 1026 IN LATR 6.0
END DESCRIPTION:
XS GIS Cut Line= 4
      2962934.43     10112152.72      2962679.21     10112074.59
      2962309.41     10111881.88      2962095.86     10111715.21
#Sta/Elev= 30
  4531.7  951.39  4571.3  951.20  4642.5  950.22  4653.0  949.02  4705.3  947.29
  4718.5  945.91  4778.5  942.91  4789.3  941.87  4889.7  937.03  4936.7  933.43
  4962.9  930.19  4968.6  926.58  4979.3  922.40  4991.1  919.20  5004.1  919.18
  5006.8  918.68  5010.1  919.18  5023.5  920.95  5045.6  925.06  5067.7  927.05
  5103.2  928.61  5200.3  934.67  5311.3  939.38  5335.9  941.04  5350.4  941.12
  5400.1  942.73  5414.6  943.77  5448.2  944.56  5464.3  945.44  5486.5  945.80
#Mann=8,-1,0
  4531.7    0.16       0  4571.3    0.05       0  4936.7    0.16       0
  5004.1    0.07       0  5010.1    0.16       0  5103.2    0.05       0
  5311.3     0.1       0  5448.2    0.05       0
Bank Sta=5004.1,5010.1
Exp/Cntr=0.3,0.1

Type RM Length L Ch R = 1,2219,383,383,383
BEGIN DESCRIPTION:
UNT 1026 IN LATR 5.0
END DESCRIPTION:
XS GIS Cut Line= 3
      2963043.83     10111777.74      2962319.83     10111413.13
      2962095.83     10111381.88
#Sta/Elev= 30
  4487.9  938.16  4526.0  937.97  4576.3  936.60  4593.0  936.96  4687.8  934.67
  4703.8  934.77  4708.0  934.38  4807.4  932.00  4844.0  929.62  4851.9  928.44
  4874.6  926.29  4905.3  921.52  4964.2  917.79  4972.3  912.73  4986.6  908.61
  4994.6  908.79  4997.2  908.17  4999.9  907.67  5003.2  908.17  5008.9  909.48
  5012.8  912.12  5016.9  914.90  5022.5  916.88  5031.3  921.31  5039.2  923.00
  5061.5  925.47  5178.7  930.69  5300.7  938.41  5431.2  945.76  5524.7  947.81
#Mann=8,-1,0
  4487.9     0.1       0  4703.8    0.16       0  4708.0     0.1       0
  4851.9    0.16       0  4997.2    0.07       0  5003.2    0.16       0
  5012.8    0.05       0  5300.7     0.1       0
Bank Sta=4997.2,5003.2
Exp/Cntr=0.3,0.1

Type RM Length L Ch R = 1,1836,513,513,513
BEGIN DESCRIPTION:
UNT 1026 IN LATR 4.0
END DESCRIPTION:
XS GIS Cut Line= 4
      2963064.66     10111355.87      2962871.91     10111230.84
      2962351.08     10111111.05      2962028.14     10111126.68
#Sta/Elev= 30
  4606.3  932.92  4676.3  930.30  4840.4  924.03  4850.2  922.98  4935.9  918.04
  4952.5  914.93  4973.0  907.63  4978.7  904.22  4993.5  902.16  5000.8  902.03
  5003.5  901.53  5006.8  902.03  5014.0  902.54  5026.7  904.48  5034.5  906.23
  5044.8  909.47  5064.4  917.36  5069.5  917.69  5077.5  919.49  5112.3  921.77
  5117.5  921.34  5155.2  923.98  5163.1  924.05  5245.9  927.16  5336.7  929.06
  5385.3  930.65  5454.0  932.64  5523.3  934.61  5563.3  936.50  5693.8  938.91
#Mann=8,-1,0
  4606.3     0.1       0  4676.3    0.16       0  5000.8    0.07       0
  5006.8    0.16       0  5077.5    0.05       0  5163.1     0.1       0
  5385.3    0.05       0  5454.0     0.1       0
Bank Sta=5000.8,5006.8
Exp/Cntr=0.3,0.1

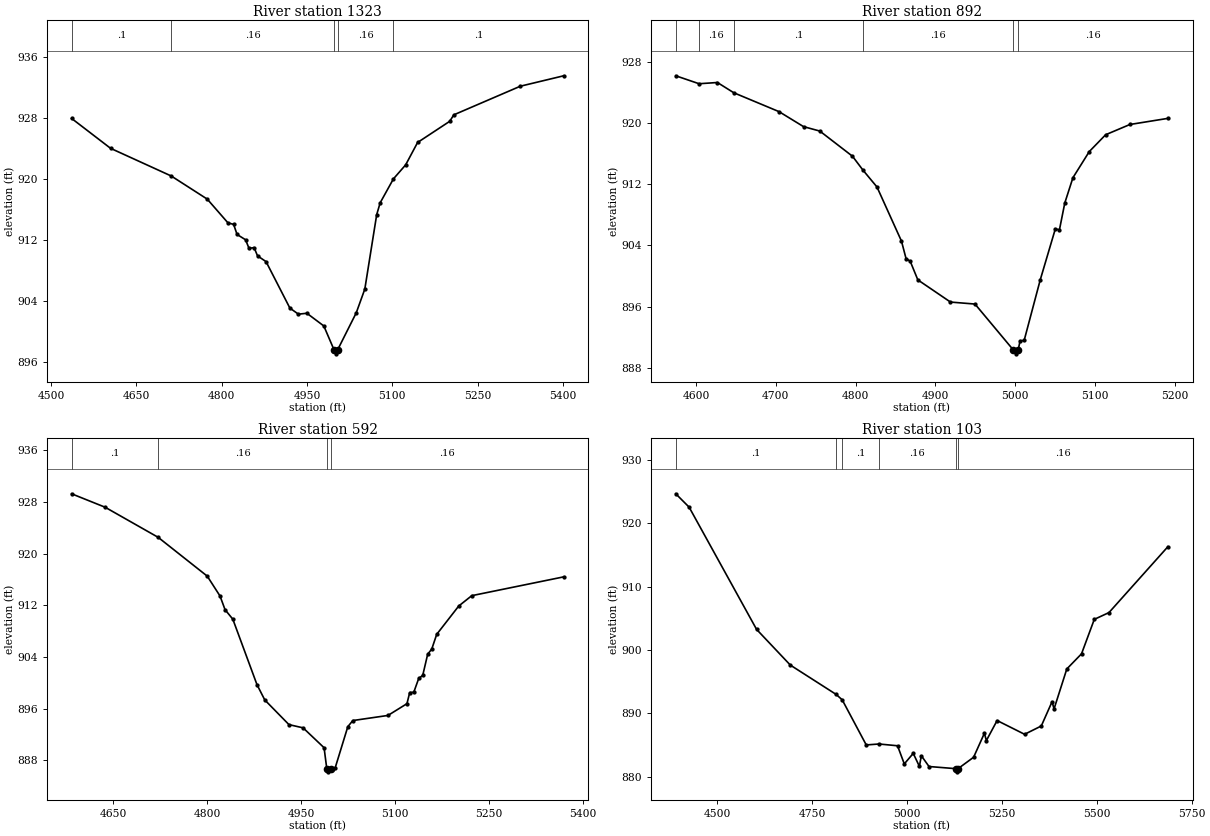
Type RM Length L Ch R = 1,1323,431,431,431
BEGIN DESCRIPTION:
UNT 1026 IN LATR 3.0
END DESCRIPTION:
XS GIS Cut Line= 4
      2963127.12     10111142.35      2963127.12     10110866.26
      2962804.21     10110647.51      2962616.68     10110579.79
#Sta/Elev= 30
  4536.1  927.95  4604.7  924.02  4711.3  920.39  4774.7  917.35  4811.0  914.24
  4821.1  914.03  4827.1  912.71  4842.1  912.01  4848.1  910.89  4857.1  910.98
  4863.1  909.90  4878.1  909.14  4920.0  903.04  4935.0  902.24  4949.9  902.36
  4979.7  900.69  4997.8  897.53  5000.6  897.03  5003.8  897.53  5036.8  902.43
  5051.8  905.54  5072.7  915.32  5078.8  916.87  5102.1  920.01  5123.6  921.85
  5144.6  924.79  5201.1  927.57  5208.3  928.42  5325.3  932.18  5401.6  933.55
#Mann=5,-1,0
  4536.1     0.1       0  4711.3    0.16       0  4997.8    0.07       0
  5003.8    0.16       0  5102.1     0.1       0
Bank Sta=4997.8,5003.8
Exp/Cntr=0.3,0.1

Type RM Length L Ch R = 1,892,300,300,300
BEGIN DESCRIPTION:
UNT 1026 IN LATR 2.0
END DESCRIPTION:
XS GIS Cut Line= 2
      2963262.54     10111090.20      2963392.45     10110487.44
#Sta/Elev= 30
  4574.7  926.19  4603.9  925.15  4626.9  925.31  4647.4  923.97  4704.1  921.50
  4734.8  919.54  4755.2  918.96  4796.1  915.67  4809.5  913.82  4826.8  911.65
  4857.5  904.57  4863.3  902.26  4868.4  901.95  4878.0  899.50  4918.9  896.60
  4949.6  896.34  4997.7  890.33  5000.5  889.83  5003.7  890.33  5006.1  891.53
  5011.2  891.58  5031.4  899.52  5050.3  906.18  5055.4  906.04  5062.1  909.55
  5072.3  912.86  5092.8  916.28  5113.3  918.48  5143.7  919.82  5191.3  920.62
#Mann=6,-1,0
  4574.7     0.1       0  4603.9    0.16       0  4647.4     0.1       0
  4809.5    0.16       0  4997.7    0.07       0  5003.7    0.16       0
Bank Sta=4997.7,5003.7
Exp/Cntr=0.3,0.1

Type RM Length L Ch R = 1,592,489,489,489
BEGIN DESCRIPTION:
Mapping XS b1fa66f5
END DESCRIPTION:
XS GIS Cut Line= 3
      2963554.85     10111176.15      2963659.02     10110655.28
      2963498.13     10110458.06
#Sta/Elev= 30
  4583.6  929.26  4637.1  927.18  4721.8  922.52  4800.2  916.51  4820.6  913.43
  4828.6  911.32  4841.0  909.85  4879.6  899.71  4892.0  897.35  4930.6  893.53
  4953.2  893.03  4986.7  889.95  4991.0  886.72  4993.7  886.22  4997.0  886.72
  5004.2  886.77  5024.6  893.21  5032.6  894.16  5088.7  894.95  5119.0  896.77
  5123.4  898.49  5129.9  898.54  5137.8  900.68  5144.2  901.15  5152.1  904.43
  5158.6  905.22  5166.5  907.50  5201.7  911.89  5222.5  913.49  5369.3  916.40
#Mann=4,-1,0
  4583.6     0.1       0  4721.8    0.16       0  4991.0    0.07       0
  4997.0    0.16       0
Bank Sta=4991,4997
Exp/Cntr=0.3,0.1

Type RM Length L Ch R = 1,103,0,0,0
BEGIN DESCRIPTION:
UNT 1026 IN LATR 1.0
END DESCRIPTION:
XS GIS Cut Line= 4
      2963836.10     10111207.38      2964080.90     10110728.20
      2964034.02     10110556.33      2963476.77     10110394.88
#Sta/Elev= 30
  4391.0  924.62  4426.2  922.51  4603.9  903.24  4692.8  897.61  4813.4  892.99
  4829.4  892.14  4892.8  885.02  4926.5  885.17  4975.2  884.89  4993.0  882.03
  5016.6  883.69  5032.8  881.64  5037.9  883.32  5058.1  881.62  5128.6  881.28
  5131.3  880.78  5134.6  881.28  5175.6  883.08  5204.0  886.86  5209.2  885.71
  5237.5  888.87  5309.9  886.70  5353.9  888.01  5382.3  891.84  5387.5  890.70
  5421.1  897.00  5459.9  899.39  5493.5  904.82  5532.2  905.89  5687.4  916.28
#Mann=6,-1,0
  4391.0     0.1       0  4813.4    0.16       0  4829.4     0.1       0
  4926.5    0.16       0  5128.6    0.07       0  5134.6    0.16       0
Bank Sta=5128.6,5134.6
Exp/Cntr=0.3,0.1

Chan Stop Cuts=-1