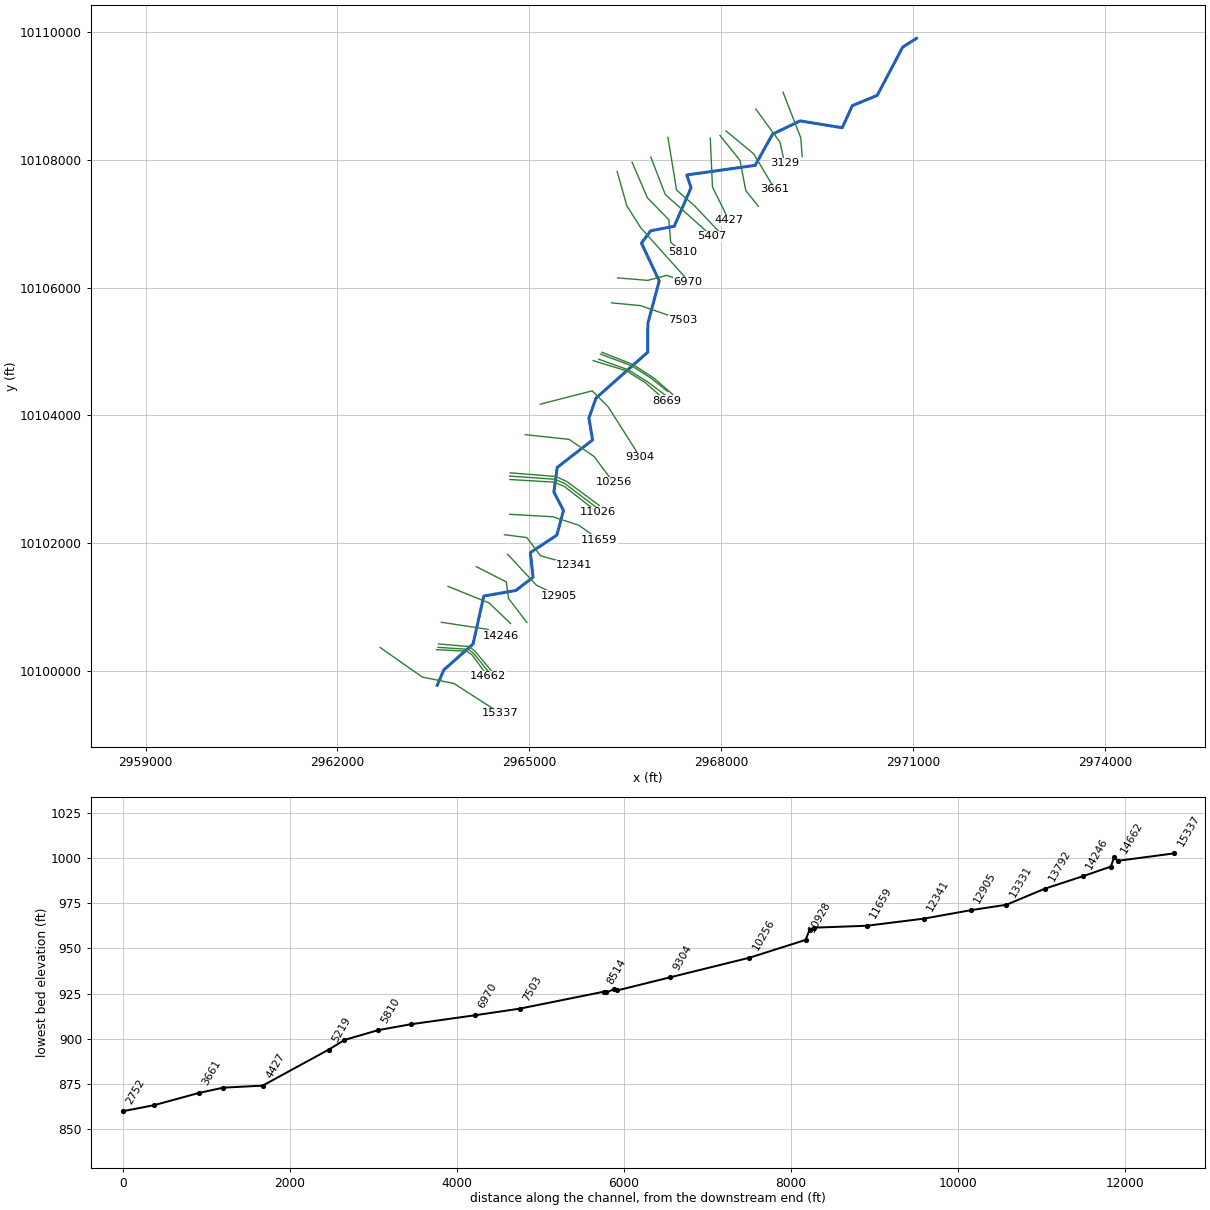
--- UNT 0027 IN LATR.prj (project) ---

Proj Title=UNT 1027 IN LATR Base Level Engineering
Current Plan=p01
Default Exp/Contr=0.3,0.1
English Units
Geom File=g01
Flow File=f01
Plan File=p01
Y Axis Title=Elevation
X Axis Title(PF)=Main Channel Distance
X Axis Title(XS)=Station
BEGIN DESCRIPTION:
UNT 1027 IN LATR
END DESCRIPTION:
DSS Export Rating Curves= 0
DSS Export Rating Curve Sorted= 0
DSS Export Volume Flow Curves= 0
DXF OffsetX= 0
DXF OffsetY= 0
DXF ScaleX= 1
DXF ScaleY= 10

--- UNT 0027 IN LATR.p01 (plan) ---

Plan Title=Multiple Run
Short Identifier=Multiple
Geom File=g01
Flow File=f01
Subcritical Flow
K Sum by GR= 0
Std Step Tol= 0.01
Critical Tol= 0.01
Num of Std Step Trials= 20
Max Error Tol= 0.3
Flow Tol Ratio= 0.001
Split Flow NTrial= 30
Split Flow Tol= 0.02
Split Flow Ratio= 0.02
Log Output Level= 0
Friction Slope Method= 1
Unsteady Friction Slope Method= 2
Unsteady Bridges Friction Slope Method= 1
Parabolic Critical Depth
Global Vel Dist=  1 , 1 , 1
Global Log Level= 0
CheckData=True
Encroach Param= -1, 0, 0, 0
BEGIN DESCRIPTION:
Multiple Run
END DESCRIPTION:

--- UNT 0027 IN LATR.f01 (steady flow) ---

Flow Title=Multiple
Program Version=4.10
Number of Profiles= 7
Profile Names=10-year,25-year,50-year,1pct_min,100-year,1pct_plu,500-year
River Rch & RM=UNT 1027 IN LATR,Reach-1         ,15337
    1417    2101    2708    2550    3449    4664    5619
River Rch & RM=UNT 1027 IN LATR,Reach-1         ,6198
    2004    3020    3934    3741    5060    6843    8407
River Rch & RM=UNT 1027 IN LATR,Reach-1         ,4427
    2004    3020    3934    3741    5060    6843    8407
River Rch & RM=UNT 1027 IN LATR,Reach-1         ,1862
    2575    3925    5153    4935    6673    9025   11245
Boundary for River Rch & Prof#=UNT 1027 IN LATR,Reach-1         , 1
Up Type= 0
Dn Type= 3
Dn Slope=0.005
Boundary for River Rch & Prof#=UNT 1027 IN LATR,Reach-1         , 2
Up Type= 0
Dn Type= 3
Dn Slope=0.005
Boundary for River Rch & Prof#=UNT 1027 IN LATR,Reach-1         , 3
Up Type= 0
Dn Type= 3
Dn Slope=0.005
Boundary for River Rch & Prof#=UNT 1027 IN LATR,Reach-1         , 4
Up Type= 0
Dn Type= 3
Dn Slope=0.005
Boundary for River Rch & Prof#=UNT 1027 IN LATR,Reach-1         , 5
Up Type= 0
Dn Type= 3
Dn Slope=0.005
Boundary for River Rch & Prof#=UNT 1027 IN LATR,Reach-1         , 6
Up Type= 0
Dn Type= 3
Dn Slope=0.005
Boundary for River Rch & Prof#=UNT 1027 IN LATR,Reach-1         , 7
Up Type= 0
Dn Type= 3
Dn Slope=0.005
DSS Import GetInterval= 0
DSS Import GetPeak= 0
DSS Import FillOption= 0

--- UNT 0027 IN LATR.g01 (geometry) ---

Geom Title=Existing Conditions
Program Version=4.10

River Reach=UNT 1027 IN LATR,Reach-1
Reach XY= 30
      2963558.47     10099773.73      2963663.41     10100015.64
      2964118.54     10100418.35      2964286.15     10101169.71
      2964787.01     10101257.23      2965056.04     10101464.65
      2965014.34     10101850.58       2965427.9     10102123.81
      2965531.95     10102509.56       2965381.7     10102799.97
       2965433.8     10103183.85       2965986.6     10103614.65
      2965929.05     10103958.36      2966041.34     10104271.79
      2966848.46     10104988.73      2966849.94     10105438.14
      2967028.19     10106104.58      2966750.04     10106697.87
      2966895.28     10106890.01      2967263.08     10106960.81
      2967525.43     10107564.78      2967458.58     10107763.81
      2968527.74     10107915.29      2968799.39     10108402.88
       2969229.8     10108610.67      2969888.47     10108503.73
      2970046.36     10108849.74      2970435.07     10109010.44
      2970833.31     10109766.57      2971048.47     10109903.73

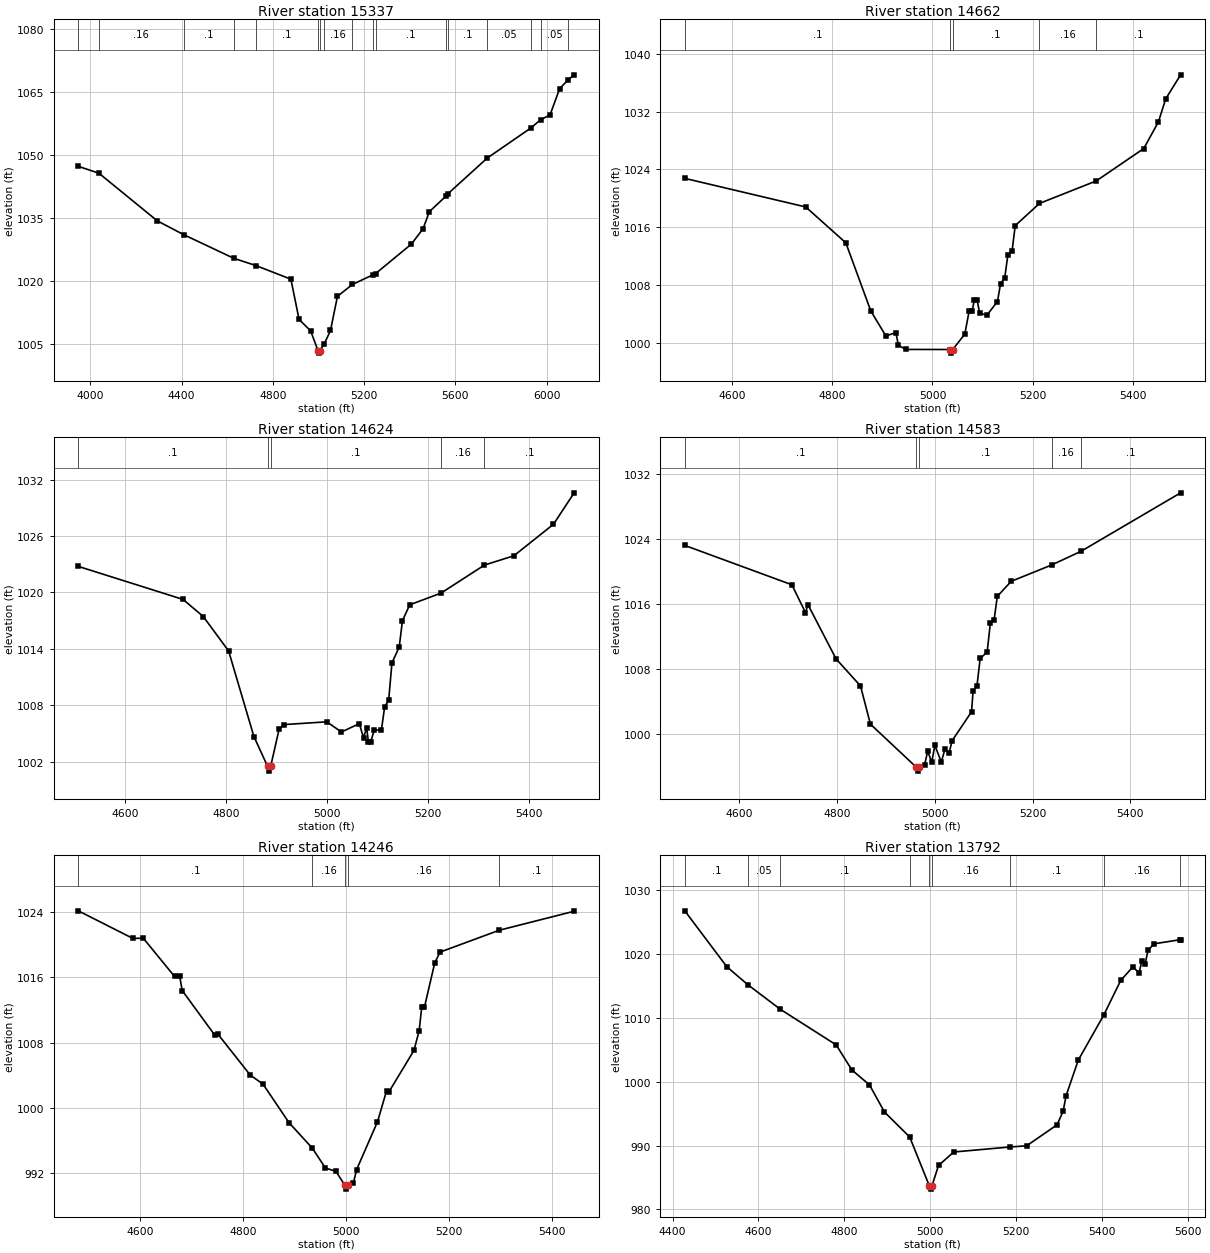
Type RM Length L Ch R = 1 ,15337   ,675,675,675
BEGIN DESCRIPTION:
UNT 1027 IN LATR 33.0
END DESCRIPTION:
XS GIS Cut Line= 4
      2962666.17     10100364.97      2963325.91     10099900.55
       2963820.7     10099800.72      2964544.47     10099332.66
#Sta/Elev= 30
  3947.2 1047.24  4037.5  1045.6  4293.3 1034.26    4409 1030.97  4628.9 1025.33
  4727.1 1023.58    4879 1020.36  4914.8 1010.78  4965.6 1008.05  4998.5 1003.25
  5001.2 1002.75  5004.5 1003.25  5024.8 1004.89  5052.5 1008.14  5083.1 1016.29
  5148.8  1019.1  5239.9 1021.44  5250.4  1021.7  5407.4 1028.73  5458.6  1032.4
  5485.9 1036.44  5557.9  1040.1  5565.5 1040.62  5739.8 1049.22  5930.8 1056.37
  5973.8 1058.35  6014.9 1059.48  6057.1 1065.73  6094.7 1067.89  6120.7 1069.04
#Mann= 17 ,-1 , 0
  3947.2      .1       0  4037.5     .16       0    4409      .1       0
  4628.9     .16       0  4727.1      .1       0  4998.5     .07       0
  5004.5      .1       0  5024.8     .16       0  5148.8      .1       0
  5239.9     .16       0  5250.4      .1       0  5557.9     .05       0
  5565.5      .1       0  5739.8     .05       0  5930.8      .1       0
  5973.8     .05       0  6094.7     .16       0
Bank Sta=4998.5,5004.5
XS Rating Curve= 0 ,0
Exp/Cntr=0.3,0.1

Type RM Length L Ch R = 1 ,14662   ,38,38,38
BEGIN DESCRIPTION:
Mapping XS 6734eb92
END DESCRIPTION:
XS GIS Cut Line= 4
      2963547.22     10100330.24      2964020.35     10100306.36
      2964107.16     10100243.43      2964350.22     10099913.56
#Sta/Elev= 30
  4505.1 1022.76  4746.7 1018.81  4826.8 1013.86  4876.8 1004.43  4906.9 1000.98
  4926.9 1001.45  4931.9  999.68  4946.9  999.12  5034.5  999.11  5037.3  998.61
  5040.5  999.11  5064.6 1001.24  5073.1 1004.38  5079.3 1004.44  5083.8 1006.02
    5089 1006.02  5094.3 1004.11  5108.9 1003.87  5129.8 1005.74    5136 1008.19
  5144.4 1009.04  5150.6 1012.18  5159.1 1012.78  5165.3 1016.23  5213.8  1019.3
  5327.3 1022.41  5422.1 1026.88  5451.4 1030.56    5466 1033.75  5495.8 1037.07
#Mann= 5 ,-1 , 0
  4505.1      .1       0  5034.5     .07       0  5040.5      .1       0
  5213.8     .16       0  5327.3      .1       0
Bank Sta=5034.5,5040.5
XS Rating Curve= 0 ,0
Exp/Cntr=0.3,0.1

Type RM Length L Ch R = 1 ,14624   ,41,41,41
BEGIN DESCRIPTION:
UNT 1027 IN LATR 32.0
END DESCRIPTION:
XS GIS Cut Line= 4
      2963571.58     10100366.69      2964045.53     10100335.44
      2964125.39     10100274.68       2964380.6      10099958.7
#Sta/Elev= 30
  4507.2 1022.77  4714.5 1019.26  4754.6 1017.44  4804.7 1013.78  4854.8 1004.68
  4881.9 1001.51  4884.7 1001.01  4887.9 1001.51  4904.9 1005.53    4915 1005.96
    4999 1006.25  5028.1 1005.17  5063.4 1006.06  5071.7 1004.56    5078 1005.62
  5081.3 1004.15  5086.3 1004.15  5092.8 1005.36  5107.2  1005.4  5113.6 1007.86
  5121.5 1008.53    5128 1012.51  5142.4  1014.2  5148.8    1017  5163.2 1018.69
  5225.1 1019.93  5311.1 1022.91  5369.4  1023.9  5447.8 1027.25  5488.7 1030.59
#Mann= 5 ,-1 , 0
  4507.2      .1       0  4881.9     .07       0  4887.9      .1       0
  5225.1     .16       0  5311.1      .1       0
Bank Sta=4881.9,4887.9
XS Rating Curve= 0 ,0
Exp/Cntr=0.3,0.1

Type RM Length L Ch R = 1 ,14583   ,337,337,337
BEGIN DESCRIPTION:
Mapping XS 71d46b2e
END DESCRIPTION:
XS GIS Cut Line= 4
      2963580.21     10100420.52      2964055.94     10100378.85
      2964142.75     10100312.87      2964417.08     10099984.72
#Sta/Elev= 30
  4488.5 1023.21  4707.6 1018.37  4735.4 1014.94  4740.4 1015.93  4797.9 1009.26
  4847.9 1005.93  4868.2 1001.23  4961.8  995.95  4964.6  995.45  4967.8  995.95
  4979.1  996.25  4985.4   997.9  4993.7  996.55    5000  998.63  5013.2  996.57
  5020.8  998.17    5029  997.64  5035.3  999.19  5075.1 1002.75  5078.3 1005.34
  5086.1 1005.88  5092.7 1009.31    5107 1010.09  5113.5 1013.62  5121.3 1014.08
  5127.8 1016.95  5156.4  1018.8  5238.7  1020.8  5299.1 1022.49  5502.8 1029.68
#Mann= 5 ,-1 , 0
  4488.5      .1       0  4961.8     .07       0  4967.8      .1       0
  5238.7     .16       0  5299.1      .1       0
Bank Sta=4961.8,4967.8
XS Rating Curve= 0 ,0
Exp/Cntr=0.3,0.1

Type RM Length L Ch R = 1 ,14246   ,454,454,454
BEGIN DESCRIPTION:
UNT 1027 IN LATR 31.0
END DESCRIPTION:
XS GIS Cut Line= 3
      2963623.69     10100759.05      2964331.98     10100651.42
      2964557.71     10100550.71
#Sta/Elev= 30
  4479.3 1024.15  4585.3 1020.77  4605.5  1020.8  4666.2 1016.12  4676.2 1016.16
  4681.2 1014.39  4744.9 1008.89  4749.9  1009.1  4813.5 1004.03  4838.1 1002.94
  4888.7  998.21  4934.2  995.08  4959.5  992.65  4979.8  992.26    4997  990.57
  4999.7  990.07    5003  990.57  5013.9  990.82  5020.2  992.47  5060.7  998.32
  5078.2 1002.09  5083.2 1002.01  5131.5 1007.05  5141.6 1009.45  5146.8 1012.42
  5151.9 1012.34  5171.9 1017.76  5182.1 1019.09  5297.1 1021.77  5442.9  1024.1
#Mann= 5 ,-1 , 0
  4479.3      .1       0  4934.2     .16       0    4997     .07       0
    5003     .16       0  5297.1      .1       0
Bank Sta=4997,5003
XS Rating Curve= 0 ,0
Exp/Cntr=0.3,0.1

Type RM Length L Ch R = 1 ,13792   ,461,461,461
BEGIN DESCRIPTION:
UNT 1027 IN LATR 30.0
END DESCRIPTION:
XS GIS Cut Line= 3
      2963727.82     10101321.55      2964370.18     10101061.14
       2964703.5     10100741.71
#Sta/Elev= 30
  4428.6 1026.79  4526.4 1018.03  4575.6  1015.2    4651 1011.36  4781.1 1005.78
  4817.8 1001.84  4858.7  999.51  4893.6  995.26  4952.4  991.34  4998.2  983.67
  5000.9  983.17  5004.2  983.67  5019.5  986.88  5055.1  988.99  5186.7  989.78
  5224.8  989.96  5295.6  993.25  5309.7  995.37  5316.6   997.8    5345 1003.39
  5404.1 1010.42    5444 1015.89  5472.3 1018.01  5486.5 1017.06  5493.4 1018.98
  5500.6 1018.41  5507.5 1020.62  5521.7 1021.62  5582.9 1022.27  5583.4 1022.27
#Mann= 9 ,-1 , 0
  4428.6      .1       0  4575.6     .05       0    4651      .1       0
  4952.4     .16       0  4998.2     .07       0  5004.2     .16       0
  5186.7      .1       0  5404.1     .16       0  5582.9      .1       0
Bank Sta=4998.2,5004.2
XS Rating Curve= 0 ,0
Exp/Cntr=0.3,0.1

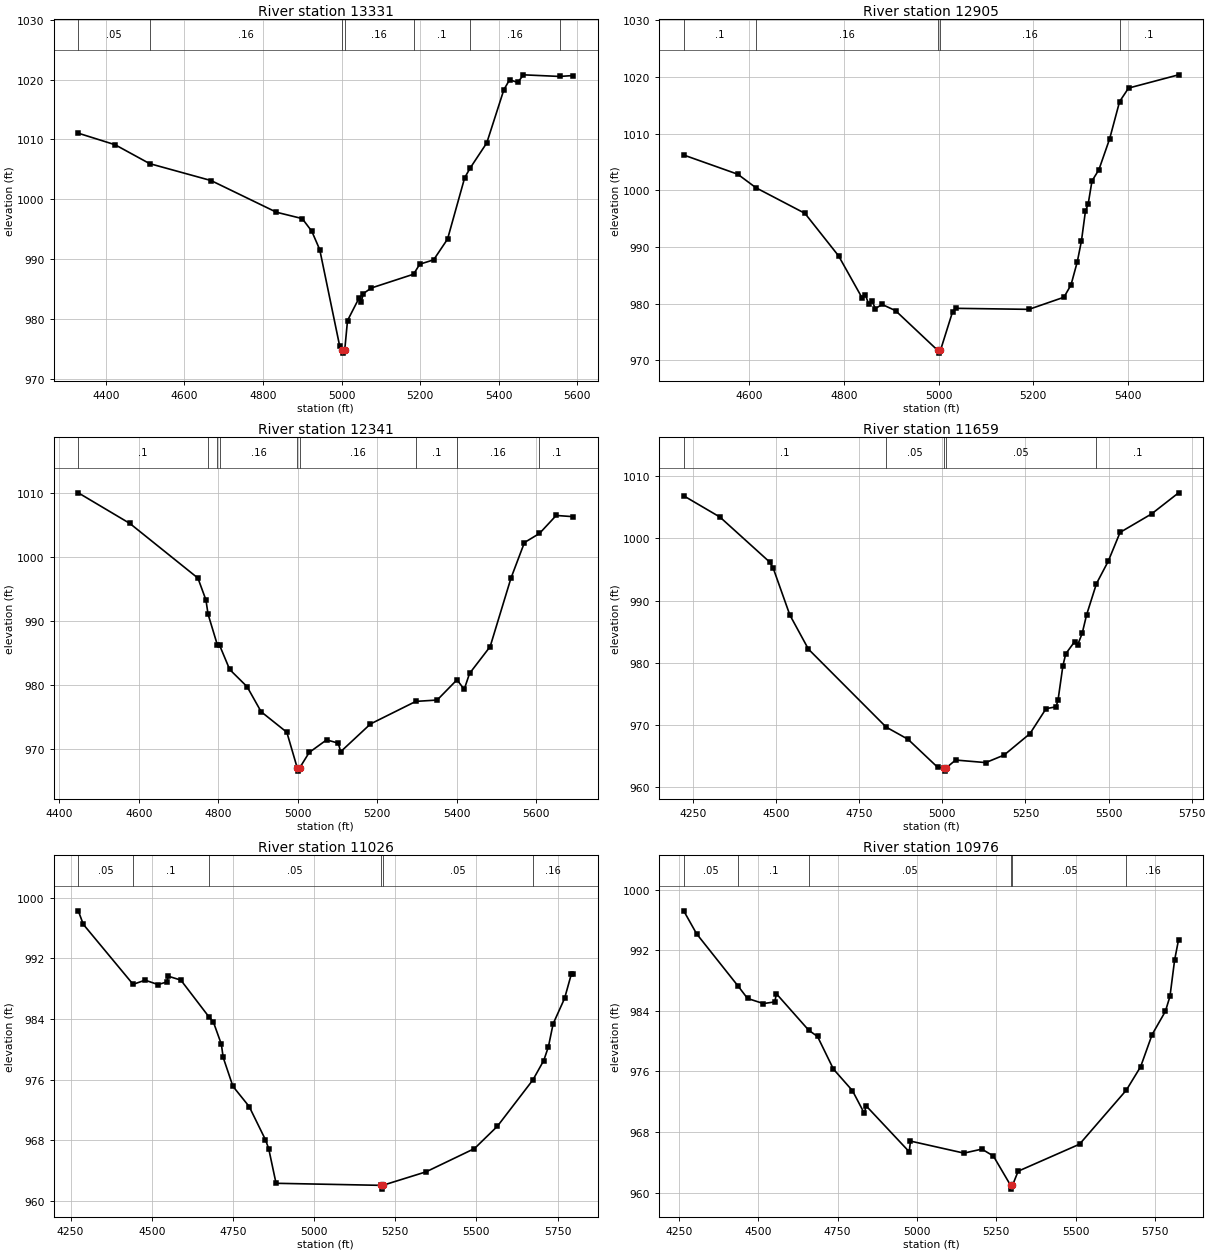
Type RM Length L Ch R = 1 ,13331   ,426,426,426
BEGIN DESCRIPTION:
UNT 1027 IN LATR 29.0
END DESCRIPTION:
XS GIS Cut Line= 4
      2964168.76      10101630.6      2964637.54       10101391.
      2964672.26     10101134.06      2964959.28     10100757.13
#Sta/Elev= 30
  4329.7 1011.03  4423.3  1009.1  4511.3 1005.94  4667.6 1003.11  4834.1  997.81
  4899.6  996.75    4924  994.63  4944.2  991.56  4994.7  975.52  5001.8  974.75
  5004.5  974.25  5007.8  974.75  5014.9  979.69  5044.9  983.54    5050  982.86
  5055.2  984.21  5075.4  985.14  5183.1  987.45  5198.7  989.12  5234.1  989.85
  5269.5  993.32  5313.1 1003.58    5327 1005.19  5369.3  1009.4  5412.9 1018.31
  5427.4 1019.96  5448.2 1019.52  5462.8 1020.79  5554.6 1020.52  5589.2 1020.67
#Mann= 7 ,-1 , 0
  4329.7     .05       0  4511.3     .16       0  5001.8     .07       0
  5007.8     .16       0  5183.1      .1       0    5327     .16       0
  5554.6      .1       0
Bank Sta=5001.8,5007.8
XS Rating Curve= 0 ,0
Exp/Cntr=0.3,0.1

Type RM Length L Ch R = 1 ,12905   ,564,564,564
BEGIN DESCRIPTION:
UNT 1027 IN LATR 28.0
END DESCRIPTION:
XS GIS Cut Line= 3
       2964658.4       10101825.      2965109.76     10101338.92
      2965453.46     10101175.74
#Sta/Elev= 30
  4462.5 1006.22  4576.5 1002.83  4614.9 1000.44  4718.2  995.92  4789.1  988.42
  4838.4  981.05  4845.8  981.53  4852.6  979.89    4860  980.38  4866.8   979.1
  4880.9  979.84  4909.3  978.74  4998.1  971.74  5000.9  971.24  5004.1  971.74
  5029.5  978.51  5036.8  979.15  5190.7  978.97  5264.5  981.11  5279.4  983.28
  5292.7  987.38  5301.5  991.09  5309.9  996.35  5315.5  997.51  5323.7 1001.65
  5338.2 1003.62  5360.9 1009.08  5381.9 1015.66  5400.8 1018.04  5506.3 1020.38
#Mann= 5 ,-1 , 0
  4462.5      .1       0  4614.9     .16       0  4998.1     .07       0
  5004.1     .16       0  5381.9      .1       0
Bank Sta=4998.1,5004.1
XS Rating Curve= 0 ,0
Exp/Cntr=0.3,0.1

Type RM Length L Ch R = 1 ,12341   ,682,682,682
BEGIN DESCRIPTION:
UNT 1027 IN LATR 27.0
END DESCRIPTION:
XS GIS Cut Line= 4
      2964609.72     10102130.59      2964960.46     10102085.44
      2965172.26     10101800.72      2965689.61     10101654.89
#Sta/Elev= 30
  4447.4 1010.09  4577.2  1005.3  4748.6  996.75  4768.8  993.33  4774.1  991.12
  4797.7  986.27    4803  986.27  4828.6  982.45  4872.4  979.76  4907.8  975.84
  4972.5  972.63  4998.7  967.05  5001.5  966.55  5004.7  967.05  5028.8  969.47
  5072.6  971.44  5101.9  970.93  5108.1  969.59  5183.1  973.93  5297.2  977.46
    5351  977.67  5400.9  980.84  5419.1  979.34  5432.5  981.83  5484.4  986.03
  5536.7  996.72  5570.7 1002.31  5608.5 1003.73  5650.7 1006.55  5693.4 1006.36
#Mann= 9 ,-1 , 0
  4447.4      .1       0  4774.1     .16       0  4797.7      .1       0
    4803     .16       0  4998.7     .07       0  5004.7     .16       0
  5297.2      .1       0  5400.9     .16       0  5608.5      .1       0
Bank Sta=4998.7,5004.7
XS Rating Curve= 0 ,0
Exp/Cntr=0.3,0.1

Type RM Length L Ch R = 1 ,11659   ,633,633,633
BEGIN DESCRIPTION:
UNT 1027 IN LATR 26.0
END DESCRIPTION:
XS GIS Cut Line= 4
      2964689.66     10102450.03      2965363.23     10102411.83
      2965769.48     10102279.89      2966084.48     10102054.89
#Sta/Elev= 30
  4221.8 1006.81  4330.8  1003.4    4481  996.15    4491  995.21  4541.1  987.68
  4597.1  982.19  4830.9  969.68  4896.5  967.73  4986.1  963.21    5005  963.11
  5007.7  962.61    5011  963.11  5039.9  964.39  5130.6  963.98  5185.8  965.19
  5263.6  968.63    5312  972.64  5341.8  972.93  5347.9  973.96  5362.7  979.54
  5371.3  981.45  5398.3  983.42  5406.9  982.85  5420.7  984.73    5434  987.71
  5463.7  992.72  5499.1  996.31  5534.7 1000.94  5629.3  1003.9  5710.7 1007.29
#Mann= 5 ,-1 , 0
  4221.8      .1       0  4830.9     .05       0    5005    .035       0
    5011     .05       0  5463.7      .1       0
Bank Sta=5005,5011
XS Rating Curve= 0 ,0
Exp/Cntr=0.3,0.1

Type RM Length L Ch R = 1 ,11026   ,50,50,50
BEGIN DESCRIPTION:
UNT 1027 IN LATR 25.0
END DESCRIPTION:
XS GIS Cut Line= 4
       2964693.1     10102995.17       2965385.8      10102953.5
        2965549.     10102884.06      2966062.85      10102481.3
#Sta/Elev= 30
  4273.8  998.27  4289.2  996.49  4442.6  988.57  4479.5  989.12  4519.6  988.54
  4546.1  988.88  4551.1  989.64  4589.7  989.13    4676  984.29  4689.9   983.6
  4714.5  980.66    4720  978.94    4750  975.12  4800.1  972.45  4850.2  968.07
  4860.2   966.9  4882.9  962.32  5205.3  962.05  5208.1  961.55  5211.3  962.05
  5344.8  963.83    5494   966.9  5564.5  969.84    5674  975.96  5707.4  978.52
  5721.8  980.34  5736.3  983.36  5771.6  986.72  5792.1  989.88    5798  989.88
#Mann= 6 ,-1 , 0
  4273.8     .05       0  4442.6      .1       0    4676     .05       0
  5205.3    .035       0  5211.3     .05       0    5674     .16       0
Bank Sta=5205.3,5211.3
XS Rating Curve= 0 ,0
Exp/Cntr=0.3,0.1

Type RM Length L Ch R = 1 ,10976   ,48,48,48
BEGIN DESCRIPTION:
UNT 1027 IN LATR 24.0
END DESCRIPTION:
XS GIS Cut Line= 4
      2964687.84     10103048.99      2965401.43     10102998.64
      2965557.68     10102927.46      2966093.83     10102521.44
#Sta/Elev= 30
  4265.2  997.24  4305.9   994.2  4437.2  987.26  4466.3  985.66  4516.4  984.98
  4552.3   985.2  4557.3  986.28  4659.3  981.45  4686.9  980.63    4737  976.32
  4797.1  973.46  4834.7  970.45  4839.7  971.48  4975.9  965.39  4979.9   966.8
  5148.4  965.21  5204.8  965.74  5241.1  964.83  5295.4  960.95  5298.1  960.45
  5301.4  960.95  5319.2  962.82  5512.7  966.39  5660.2  973.54  5705.2  976.63
  5741.5  980.89  5783.2  983.95  5797.7  985.94  5812.3  990.73  5824.8  993.44
#Mann= 6 ,-1 , 0
  4265.2     .05       0  4437.2      .1       0  4659.3     .05       0
  5295.4    .035       0  5301.4     .05       0  5660.2     .16       0
Bank Sta=5295.4,5301.4
XS Rating Curve= 0 ,0
Exp/Cntr=0.3,0.1

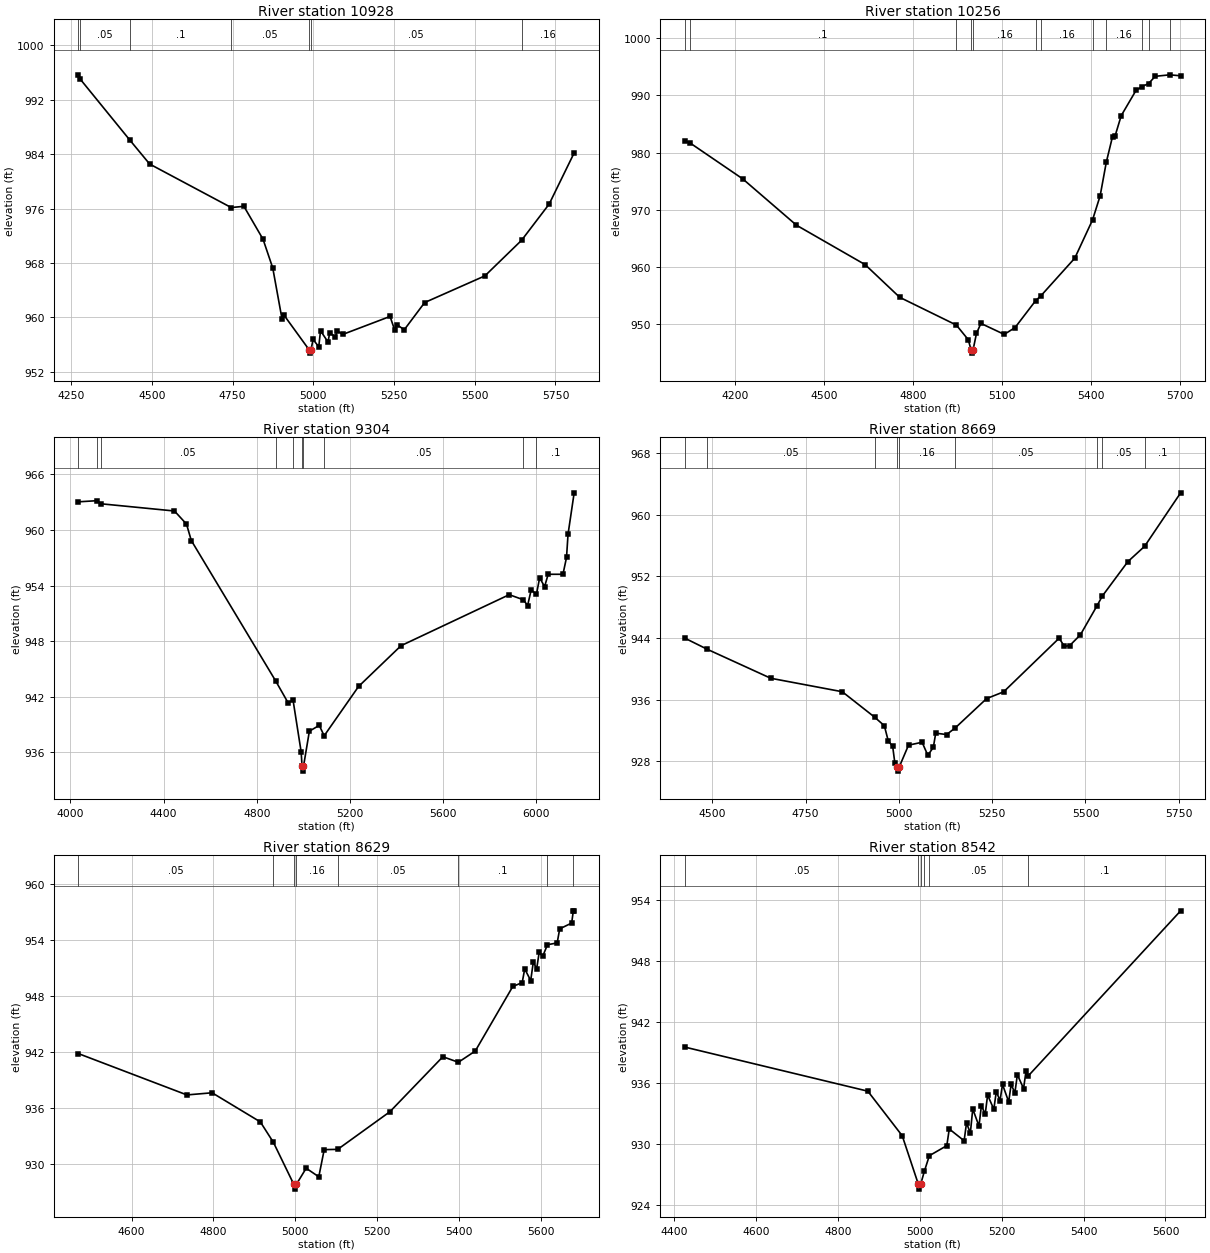
Type RM Length L Ch R = 1 ,10928   ,672,672,672
BEGIN DESCRIPTION:
UNT 1027 IN LATR 23.0
END DESCRIPTION:
XS GIS Cut Line= 4
      2964698.29     10103099.33      2965413.58     10103042.04
      2965583.72     10102963.92      2966090.69      10102588.9
#Sta/Elev= 30
  4272.5  995.65  4278.5  995.01    4432  986.06  4493.4  982.54  4745.9  976.15
  4785.2  976.33  4844.5  971.49  4874.6  967.26    4903  959.84    4908  960.43
    4987  955.26  4989.8  954.76    4993  955.26  4999.5  956.77    5017  955.69
  5022.5  958.05  5045.5   956.4    5051  957.73  5068.4  957.15  5073.9  958.04
  5091.4  957.51  5237.8  960.15  5252.4  958.11  5258.7  958.96  5281.7  958.19
  5344.9  962.19  5531.5  966.11  5645.1  971.34  5730.5  976.66  5807.9  984.18
#Mann= 7 ,-1 , 0
  4272.5      .1       0  4278.5     .05       0    4432      .1       0
  4745.9     .05       0    4987    .035       0    4993     .05       0
  5645.1     .16       0
Bank Sta=4987,4993
XS Rating Curve= 0 ,0
Exp/Cntr=0.3,0.1

Type RM Length L Ch R = 1 ,10256   ,952,952,952
BEGIN DESCRIPTION:
UNT 1027 IN LATR 22.0
END DESCRIPTION:
XS GIS Cut Line= 4
      2964934.46     10103697.42      2965620.18     10103623.64
       2966010.8     10103354.54      2966313.24     10102948.41
#Sta/Elev= 30
  4031.8  981.99  4048.2  981.72  4226.9  975.39    4408  967.28  4639.3  960.38
  4755.8  954.66  4946.7   949.8  4986.6  947.25  4996.7  945.39  4999.4  944.89
  5002.7  945.39  5014.5  948.35  5029.4  950.09    5108  948.17  5144.4  949.36
  5214.2   954.1  5230.2  954.85  5345.6  961.51  5405.4   968.2  5431.1  972.43
  5451.9  978.33  5472.8   982.8  5481.1  982.85    5502  986.45    5552  990.88
  5570.7  991.51  5594.1  992.07  5616.7  993.34  5665.6   993.6  5702.2  993.43
#Mann= 12 ,-1 , 0
  4031.8     .16       0  4048.2      .1       0  4946.7     .16       0
  4996.7     .07       0  5002.7     .16       0  5214.2      .1       0
  5230.2     .16       0  5405.4     .05       0  5451.9     .16       0
  5570.7     .05       0  5594.1      .1       0  5665.6     .05       0
Bank Sta=4996.7,5002.7
XS Rating Curve= 0 ,0
Exp/Cntr=0.3,0.1

Type RM Length L Ch R = 1 ,9304    ,635,635,635
BEGIN DESCRIPTION:
UNT 1027 IN LATR 21.0
END DESCRIPTION:
XS GIS Cut Line= 4
      2965168.75     10104174.84      2965980.42     10104383.19
      2966232.16     10104131.45      2966731.29     10103341.52
#Sta/Elev= 30
  4034.1  963.02  4112.2  963.14  4130.9  962.81  4446.8  962.03  4498.4  960.62
    4519  958.85    4881  943.72    4934  941.38    4956  941.61  4990.5  936.08
  4994.6  934.49  4997.3  933.99  5000.6  934.49  5025.9   938.3  5068.3  938.92
  5089.4   937.8  5237.2  943.12  5419.2  947.51  5883.8  953.01  5944.8  952.46
  5962.7  951.84    5978  953.53  6000.5  953.04  6014.4  954.83  6035.6  953.88
  6050.9  955.21  6114.4  955.21  6129.7  957.02  6136.2  959.52  6162.5  963.99
#Mann= 10 ,-1 , 0
  4034.1     .05       0  4112.2      .1       0  4130.9     .05       0
    4881      .1       0    4956     .16       0  4994.6     .07       0
  5000.6     .16       0  5089.4     .05       0  5944.8     .16       0
  6000.5      .1       0
Bank Sta=4994.6,5000.6
XS Rating Curve= 0 ,0
Exp/Cntr=0.3,0.1

Type RM Length L Ch R = 1 ,8669    ,40,40,40
BEGIN DESCRIPTION:
UNT 1027 IN LATR 20.0
END DESCRIPTION:
XS GIS Cut Line= 4
      2965995.19     10104857.14      2966518.62     10104695.69
      2966810.28     10104510.79      2967138.43     10104224.31
#Sta/Elev= 30
  4426.3  943.97  4487.1  942.51  4656.6  938.76  4848.3  937.01  4934.9  933.71
    4961   932.6  4971.4  930.65  4983.4   929.9  4989.3   927.7  4994.6   927.2
  4997.3   926.7  5000.6   927.2  5025.8  930.07  5062.2  930.45  5077.5  928.76
  5092.3  929.78  5098.7  931.63  5127.8  931.45    5151  932.31  5235.1  936.12
  5280.8     937  5429.4  943.96  5443.6   942.9  5457.9  943.01  5486.4   944.4
  5530.8  948.16  5545.1  949.43  5613.5   953.9  5658.4  955.89    5755  962.84
#Mann= 9 ,-1 , 0
  4426.3      .1       0  4487.1     .05       0  4934.9     .16       0
  4994.6     .07       0  5000.6     .16       0    5151     .05       0
  5530.8      .1       0  5545.1     .05       0  5658.4      .1       0
Bank Sta=4994.6,5000.6
XS Rating Curve= 0 ,0
Exp/Cntr=0.3,0.1

Type RM Length L Ch R = 1 ,8629    ,87,87,87
BEGIN DESCRIPTION:
UNT 1027 IN LATR 19.0
END DESCRIPTION:
XS GIS Cut Line= 4
      2966083.69     10104877.99      2966542.05     10104713.92
      2966844.14     10104526.42       2967138.4     10104305.07
#Sta/Elev= 30
    4470  941.86  4735.1  937.43  4796.6  937.66  4914.4  934.54  4946.4  932.34
  4996.2  927.84    4999  927.34  5002.2  927.84  5026.3  929.58  5057.1  928.66
  5070.3  931.57  5103.3   931.6  5230.7  935.63    5360  941.52  5397.9  940.93
  5439.1  942.13  5530.8  949.05  5553.7  949.46  5559.9  950.93  5574.5  949.68
  5580.8  951.65  5589.1  950.96  5595.3  952.72  5603.7  952.27  5615.4  953.52
  5639.1  953.71  5645.3  955.22  5674.5  955.84  5678.6  957.15  5680.6  957.15
#Mann= 8 ,-1 , 0
    4470     .05       0  4946.4     .16       0  4996.2     .07       0
  5002.2     .16       0  5103.3     .05       0  5397.9      .1       0
  5615.4     .05       0  5678.6      .1       0
Bank Sta=4996.2,5002.2
XS Rating Curve= 0 ,0
Exp/Cntr=0.3,0.1

Type RM Length L Ch R = 1 ,8542    ,28,28,28
BEGIN DESCRIPTION:
UNT 1027 IN LATR 17.0
END DESCRIPTION:
XS GIS Cut Line= 4
      2966109.75     10104958.71      2966601.95     10104773.81
      2966901.43      10104581.1       2967159.2      10104375.4
#Sta/Elev= 30
  4425.4  939.57  4872.7  935.23  4956.8  930.84    4996  926.09  4998.8  925.59
    5002  926.09  5010.9  927.36    5023  928.88  5065.7  929.87  5071.7  931.51
    5108  930.35  5113.9  932.11  5123.2   931.1  5129.1  933.48  5144.3   931.8
  5150.3  933.82  5159.5  932.95  5165.4  934.85  5180.6  933.45  5186.6  935.18
  5195.8  934.31  5201.8   935.9  5216.9  934.18  5222.9  935.89  5232.1  935.07
  5238.1  936.85  5253.3  935.49  5259.2  937.19  5264.7  936.73  5637.1  952.98
#Mann= 6 ,-1 , 0
  4425.4     .05       0    4996    .035       0    5002     .05       0
  5010.9     .16       0    5023     .05       0  5264.7      .1       0
Bank Sta=4996,5002
XS Rating Curve= 0 ,0
Exp/Cntr=0.3,0.1

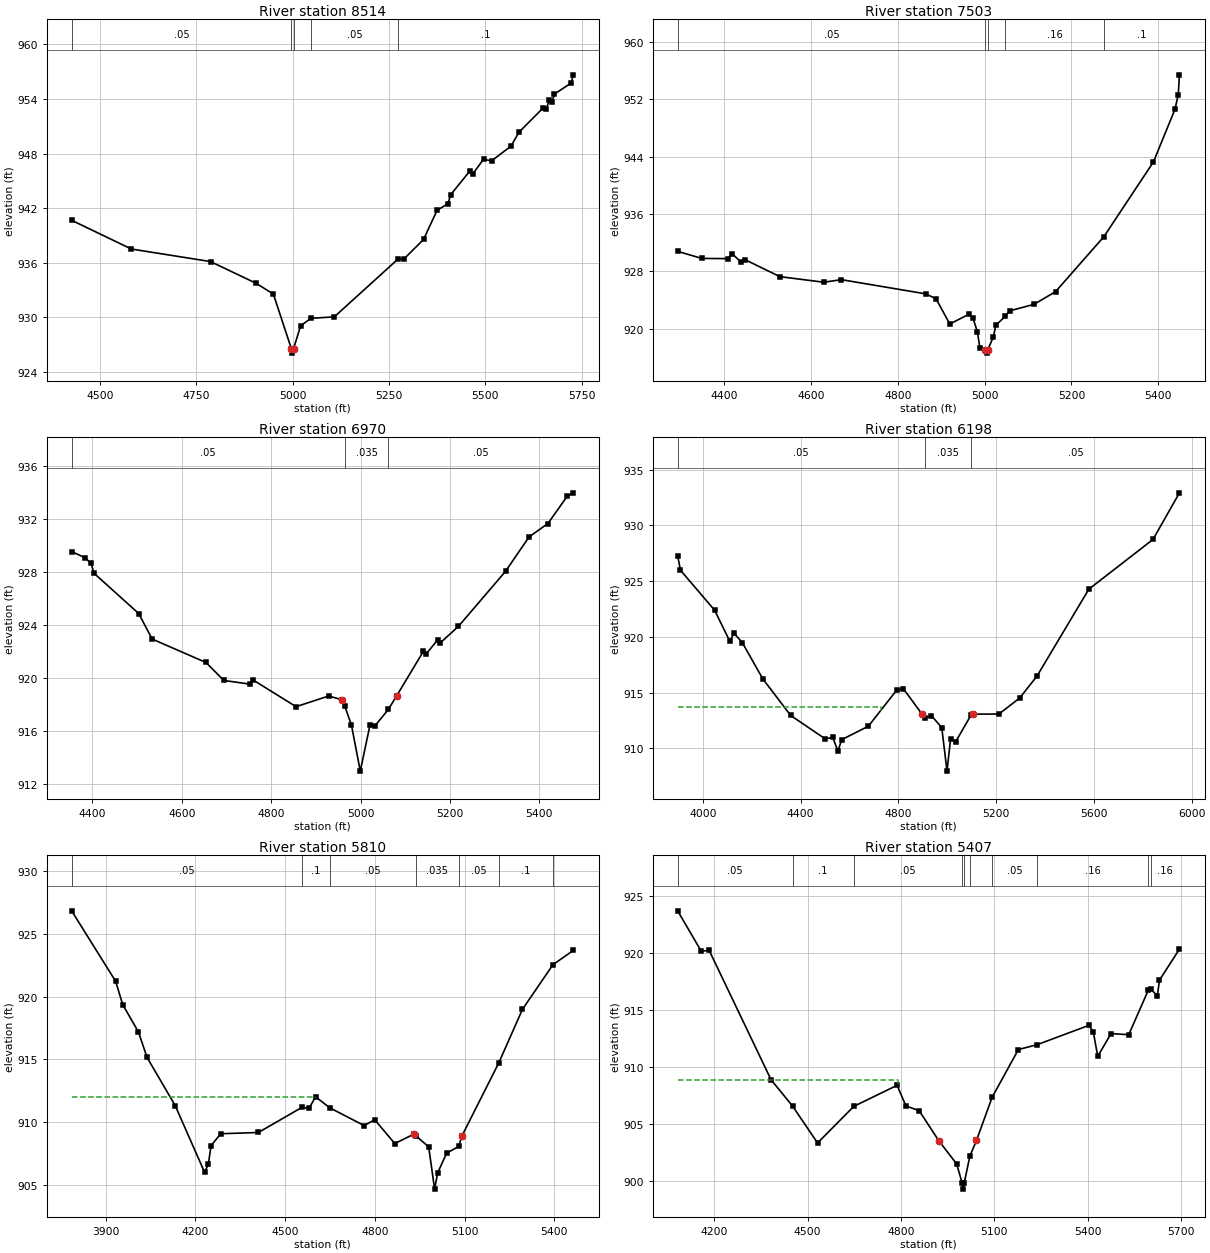
Type RM Length L Ch R = 1 ,8514    ,1011,1011,1011
BEGIN DESCRIPTION:
UNT 1027 IN LATR 18.0
END DESCRIPTION:
XS GIS Cut Line= 4
      2966133.17     10104987.36      2966620.18     10104794.65
      2966940.49     10104586.31      2967239.95     10104325.91
#Sta/Elev= 30
  4426.2  940.66  4581.3   937.5  4786.8  936.12  4905.1  933.73  4949.9  932.55
  4996.5  926.55  4999.3  926.05  5002.5  926.55  5020.6  929.05  5047.3  929.88
  5108.2  930.04  5273.1  936.38  5289.4  936.43  5339.8  938.55  5374.9  941.76
  5403.4  942.49    5410  943.46  5460.4   946.1    5467  945.72  5495.5  947.37
  5516.4   947.2  5566.7  948.81  5587.6  950.35  5651.2  953.06  5658.8  952.85
  5665.5  953.89  5673.1  953.68  5679.7  954.55  5722.4  955.74  5728.9  956.66
#Mann= 5 ,-1 , 0
  4426.2     .05       0  4996.5     .07       0  5002.5     .05       0
  5047.3     .05       0  5273.1      .1       0
Bank Sta=4996.5,5002.5
XS Rating Curve= 0 ,0
Exp/Cntr=0.3,0.1

Type RM Length L Ch R = 1 ,7503    ,533,533,533
BEGIN DESCRIPTION:
UNT 1027 IN LATR 16.0
END DESCRIPTION:
XS GIS Cut Line= 3
      2966283.34     10105761.66      2966734.76     10105718.26
      2967398.09     10105488.48
#Sta/Elev= 30
  4293.3   930.8  4348.7  929.81    4409  929.78    4419  930.45  4439.1  929.31
  4449.1  929.62  4528.7  927.27    4630  926.49  4670.2  926.85  4864.7  924.87
  4888.3  924.18    4920  920.67  4963.4  922.01    4973  921.55  4983.5  919.58
  4989.3  917.32  5001.7  917.11  5004.5  916.61  5007.7  917.11  5020.4  918.89
  5025.9   920.5  5048.2  921.76  5057.6   922.5  5113.9  923.41  5163.5  925.18
  5274.8  932.84    5389  943.27  5438.6  950.62    5446  952.63  5448.8   955.4
#Mann= 5 ,-1 , 0
  4293.3     .05       0  5001.7    .035       0  5007.7     .05       0
  5048.2     .16       0  5274.8      .1       0
Bank Sta=5001.7,5007.7
XS Rating Curve= 0 ,0
Exp/Cntr=0.3,0.1

Type RM Length L Ch R = 1 ,6970    ,772,772,772
BEGIN DESCRIPTION:
UNT 1027 IN LATR 15.0
END DESCRIPTION:
XS GIS Cut Line= 4
      2966378.86     10106152.28      2966847.61     10106113.22
      2967147.09     10106191.35      2967472.61     10106082.84
#Sta/Elev= 30
  4353.3  929.55    4383  929.09  4397.1  928.65  4403.1  927.92  4503.4  924.87
  4533.5  922.94  4653.9  921.17  4694.1  919.81  4753.3  919.53  4758.3  919.87
  4855.6  917.83  4928.9  918.64  4958.9  918.34  4964.2  917.91  4979.6  916.43
  4999.3  912.96  5020.9  916.43  5031.2  916.34  5062.3  917.63  5080.5  918.64
  5140.7  922.02  5145.9  921.78  5172.3  922.87  5177.6  922.63    5219   923.9
  5324.4  928.06  5377.1  930.66  5419.2  931.67  5462.2  933.72  5476.3  933.99
#Mann= 3 ,-1 , 0
  4353.3     .05       0  4964.2    .035       0  5062.3     .05       0
Bank Sta=4958.9,5080.5
XS Rating Curve= 0 ,0
Exp/Cntr=0.3,0.1

Type RM Length L Ch R = 1 ,6198    ,388,388,388
BEGIN DESCRIPTION:
UNT 1027 IN LATR 14.0
END DESCRIPTION:
XS GIS Cut Line= 4
      2966370.17     10107818.96      2966522.09     10107280.76
       2966739.1     10106937.87      2967463.93     10106126.24
#Sta/Elev= 30
    3897  927.27  3908.4  925.97  4047.9  922.39  4110.2  919.61  4127.9  920.32
  4161.9  919.46  4245.5  916.22  4359.6  912.94  4501.1  910.84  4531.6  910.98
  4552.8  909.75  4568.1  910.77  4677.4  911.98  4792.7   915.2  4819.8  915.36
 4897.73  913.04  4907.4  912.71    4935  912.93  4977.6  911.86  4999.1  907.95
  5013.5   910.8  5034.4  910.58    5098     913  5105.5  913.06  5211.7  913.07
  5296.6  914.51  5367.2  916.47  5579.5  924.27    5842  928.73  5950.2  932.91
#Mann= 3 ,-1 , 0
    3897     .05       0  4907.4    .035       0    5098     .05       0
#XS Ineff= 2 , 0
         4727.27  913.67
Permanent Ineff=
       T       T
Bank Sta=4897.73,5105.5
XS Rating Curve= 0 ,0
Exp/Cntr=0.3,0.1

Type RM Length L Ch R = 1 ,5810    ,403,403,403
BEGIN DESCRIPTION:
UNT 1027 IN LATR 13.0
END DESCRIPTION:
XS GIS Cut Line= 5
      2966604.56     10107962.15      2966843.27     10107406.62
      2967177.47     10107063.74      2967207.85     10106707.84
      2967393.96     10106560.69
#Sta/Elev= 30
  3786.1  926.81  3933.3  921.21  3956.9  919.36  4009.4  917.19  4038.4  915.16
  4132.6  911.33  4230.6  906.04  4243.1  906.66  4252.4  908.16  4284.8   909.1
  4410.5   909.2  4556.6   911.2  4580.3  911.12  4601.6  912.04  4649.4  911.16
  4764.2  909.75  4799.6  910.21  4866.7  908.32  4929.8  909.06  4937.4  908.93
    4980  908.06  4999.8   904.7  5010.1     906  5040.2  907.56  5080.3  908.09
  5090.4  908.89    5214  914.71  5293.7  918.99  5395.5  922.53    5464  923.67
#Mann= 7 ,-1 , 0
  3786.1     .05       0  4556.6      .1       0  4649.4     .05       0
  4937.4    .035       0  5080.3     .05       0    5214      .1       0
  5395.5     .05       0
#XS Ineff= 2 , 0
         4598.86  912.02
Permanent Ineff=
       T       T
Bank Sta=4929.8,5090.4
XS Rating Curve= 0 ,0
Exp/Cntr=0.3,0.1

Type RM Length L Ch R = 1 ,5407    ,188,188,188
BEGIN DESCRIPTION:
Mapping XS ca69ce56
END DESCRIPTION:
XS GIS Cut Line= 3
      2966897.35       10108043.      2967123.05     10107457.04
      2967856.57     10106801.64
#Sta/Elev= 30
  4082.9  923.69    4159  920.13  4183.7  920.24  4382.8  908.87  4451.9  906.56
  4532.2  903.32  4648.5  906.53  4787.6  908.38    4816  906.57  4858.6  906.15
  4922.2  903.49    4979  901.48  4996.9  899.77  4999.7  899.27  5002.9  899.77
  5021.5  902.18  5042.6  903.54  5092.7  907.32  5177.2  911.52    5237  911.94
  5403.7  913.64  5417.9  913.05  5432.1  910.92  5474.8  912.92  5531.6  912.82
  5594.8  916.75  5601.8  916.84  5623.6  916.23  5630.3  917.61  5694.5  920.33
#Mann= 10 ,-1 , 0
  4082.9     .05       0  4451.9      .1       0  4648.5     .05       0
  4996.9    .035       0  5002.9     .05       0  5021.5     .16       0
  5092.7     .05       0    5237     .16       0  5594.8     .05       0
  5601.8     .16       0
#XS Ineff= 2 , 0
         4789.25  908.82
Permanent Ineff=
       T       T
Bank Sta=4922.2,5042.6
XS Rating Curve= 0 ,0
Exp/Cntr=0.3,0.1

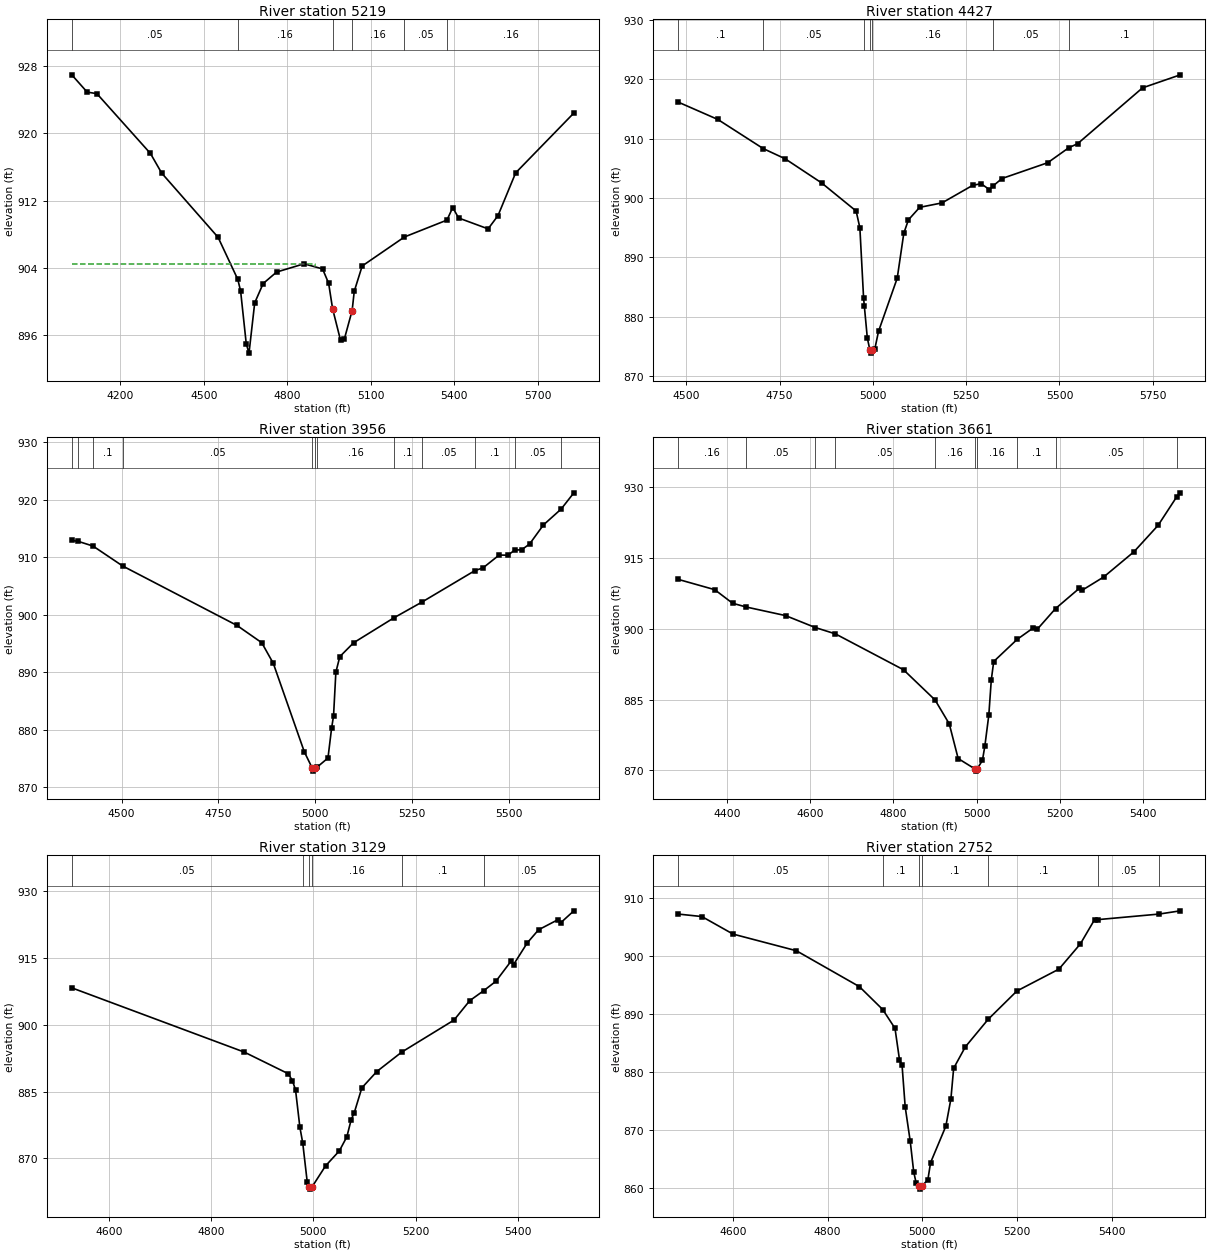
Type RM Length L Ch R = 1 ,5219    ,792,792,792
BEGIN DESCRIPTION:
UNT 1027 IN LATR 11.0
END DESCRIPTION:
XS GIS Cut Line= 4
      2967164.44     10108352.84        2967299.     10107528.15
      2967576.78      10107285.1      2967988.13     10106847.76
#Sta/Elev= 30
  4025.1   926.9  4080.5  924.85  4115.4  924.67  4307.9  917.58  4348.4  915.25
  4551.1  907.64    4622  902.65  4632.1  901.28  4652.4  895.02  4662.3  893.91
  4682.8  899.87  4713.2  902.16  4761.5  903.52  4860.4   904.5  4926.8  903.89
  4948.6  902.19  4962.9  899.16  4991.4  895.43  5005.6  895.64  5033.1  898.96
  5040.7  901.24  5069.2  904.24  5221.2  907.68    5374  909.68  5394.8  911.17
  5415.9  909.93  5521.9  908.64  5557.5  910.21    5621  915.28  5830.2  922.37
#Mann= 6 ,-1 , 0
  4025.1     .05       0    4622     .16       0  4962.9     .07       0
  5033.1     .16       0  5221.2     .05       0    5374     .16       0
#XS Ineff= 2 , 0
         4899.59  904.45
Permanent Ineff=
       T       T
Bank Sta=4962.9,5033.1
XS Rating Curve= 0 ,0
Exp/Cntr=0.3,0.1

Type RM Length L Ch R = 1 ,4427    ,471,471,471
BEGIN DESCRIPTION:
UNT 1027 IN LATR 10.0
END DESCRIPTION:
XS GIS Cut Line= 3
      2967825.91     10108339.83      2967860.63      10107575.9
      2968116.71     10107055.06
#Sta/Elev= 30
  4478.6  916.13  4584.8  913.21  4706.1  908.32    4765   906.6  4862.7  902.54
  4955.2  897.81  4965.2  894.99  4975.2  883.15  4977.2  881.81  4985.2  876.43
  4992.2  874.41    4995  873.91  4998.2  874.41  5005.2   874.6  5015.2  877.58
  5065.3  886.52  5082.9  894.07  5095.3  896.33  5125.4  898.43  5185.4  899.18
  5267.4  902.13  5289.9  902.41  5312.4  901.41  5321.8  902.02    5346  903.28
  5468.6  905.94  5525.4  908.48  5548.3  909.12  5722.5  918.53  5823.7  920.72
#Mann= 7 ,-1 , 0
  4478.6      .1       0  4706.1     .05       0  4977.2     .16       0
  4992.2     .07       0  4998.2     .16       0  5321.8     .05       0
  5525.4      .1       0
Bank Sta=4992.2,4998.2
XS Rating Curve= 0 ,0
Exp/Cntr=0.3,0.1

Type RM Length L Ch R = 1 ,3956    ,295,295,295
BEGIN DESCRIPTION:
UNT 1027 IN LATR 9.0
END DESCRIPTION:
XS GIS Cut Line= 4
       2967977.8     10108383.21      2968290.32     10107992.56
      2968381.46     10107519.47      2968576.79     10107272.05
#Sta/Elev= 30
  4371.2   912.9  4388.2  912.72  4426.1  911.91  4502.6  908.45    4798  898.12
    4862  895.12  4891.9  891.53  4972.1  876.15  4992.7   873.3  4995.5   872.8
  4998.7   873.3  5004.9  873.48  5033.2  875.08  5042.5  880.24  5047.6  882.41
  5053.6     890  5063.8   892.7  5099.5  895.11  5203.6  899.44  5275.4  902.15
    5413  907.65  5433.9  908.12  5475.5  910.35  5498.1  910.32  5516.1  911.23
  5533.3  911.25  5554.1  912.26  5589.9  915.58  5635.7  918.34  5668.5  921.16
#Mann= 12 ,-1 , 0
  4371.2      .1       0  4388.2     .16       0  4426.1      .1       0
  4502.6     .05       0  4992.7    .035       0  4998.7     .05       0
  5004.9     .16       0  5203.6      .1       0  5275.4     .05       0
    5413      .1       0  5516.1     .05       0  5635.7      .1       0
Bank Sta=4992.7,4998.7
XS Rating Curve= 0 ,0
Exp/Cntr=0.3,0.1

Type RM Length L Ch R = 1 ,3661    ,532,532,532
BEGIN DESCRIPTION:
UNT 1027 IN LATR 8.0
END DESCRIPTION:
XS GIS Cut Line= 3
       2968073.3     10108452.64      2968502.99     10108096.73
      2968836.63     10107537.78
#Sta/Elev= 30
  4281.7   910.5  4369.5  908.32  4412.5  905.44  4445.4  904.64  4540.1  902.82
  4611.6  900.29  4660.2  898.94  4824.1  891.33  4900.1  884.92  4934.3  879.85
  4955.7   872.5  4995.5  870.33  4998.3  869.83  5001.5  870.33  5014.1  872.09
  5019.9  875.11  5029.5  881.71  5035.5  889.19  5041.3  893.08  5097.8  897.78
  5136.7  900.22  5145.9  899.89  5190.2  904.31  5247.6  908.62  5253.4  908.15
    5306     911  5378.9  916.35  5437.1  921.96  5482.2  928.05  5490.6  928.86
#Mann= 10 ,-1 , 0
  4281.7     .16       0  4445.4     .05       0  4611.6      .1       0
  4660.2     .05       0  4900.1     .16       0  4995.5     .07       0
  5001.5     .16       0  5097.8      .1       0  5190.2     .05       0
  5482.2      .1       0
Bank Sta=4995.5,5001.5
XS Rating Curve= 0 ,0
Exp/Cntr=0.3,0.1

Type RM Length L Ch R = 1 ,3129    ,377,377,377
BEGIN DESCRIPTION:
UNT 1027 IN LATR 7.0
END DESCRIPTION:
XS GIS Cut Line= 3
      2968537.69     10108795.55      2968915.32     10108279.02
       2968989.1     10107944.82
#Sta/Elev= 30
  4527.5  908.31  4864.8  893.88  4950.9  889.02    4959  887.49  4965.2  885.38
  4973.7     877  4979.3  873.46  4988.1  864.66  4991.5  863.59  4994.3  863.09
  4997.5  863.59  5023.9  868.31  5050.9  871.68  5065.6  874.85    5074  878.67
  5080.2   880.3  5094.9  885.84  5124.2  889.51  5172.9  893.87  5275.2  901.07
  5305.9  905.42  5333.5  907.69  5357.1  909.78  5386.7  914.29  5391.8  913.55
  5418.5  918.41  5440.6  921.35  5479.2  923.66  5484.3  922.97  5509.6  925.61
#Mann= 6 ,-1 , 0
  4527.5     .05       0  4979.3     .16       0  4991.5     .07       0
  4997.5     .16       0  5172.9      .1       0  5333.5     .05       0
Bank Sta=4991.5,4997.5
XS Rating Curve= 0 ,0
Exp/Cntr=0.3,0.1

Type RM Length L Ch R = 1 ,2752    ,890,890,890
BEGIN DESCRIPTION:
UNT 1027 IN LATR 6.0
END DESCRIPTION:
XS GIS Cut Line= 3
      2968963.06     10109060.28      2969240.84     10108344.12
      2969262.54     10108053.37
#Sta/Elev= 30
  4484.8  907.24  4534.7  906.81  4600.5  903.78    4734  900.91  4867.2   894.7
  4916.5  890.74  4942.3   887.5  4951.8  882.07  4957.2  881.13  4963.8  873.94
  4974.5  867.96  4981.8   862.7  4987.1  860.72  4992.9  860.22  4995.7  859.72
  4998.9  860.22  5011.7  861.35  5017.4   864.3  5049.6  870.59  5060.3  875.31
  5066.1   880.6  5090.7  884.29  5139.2  889.08  5199.6  893.95  5288.3  897.73
  5333.6  902.09  5363.6  906.29  5371.8  906.29  5499.7  907.24  5544.5   907.8
#Mann= 7 ,-1 , 0
  4484.8     .05       0  4916.5      .1       0  4992.9     .07       0
  4998.9      .1       0  5139.2      .1       0  5371.8     .05       0
  5499.7      .1       0
Bank Sta=4992.9,4998.9
XS Rating Curve= 0 ,0
Exp/Cntr=0.3,0.1