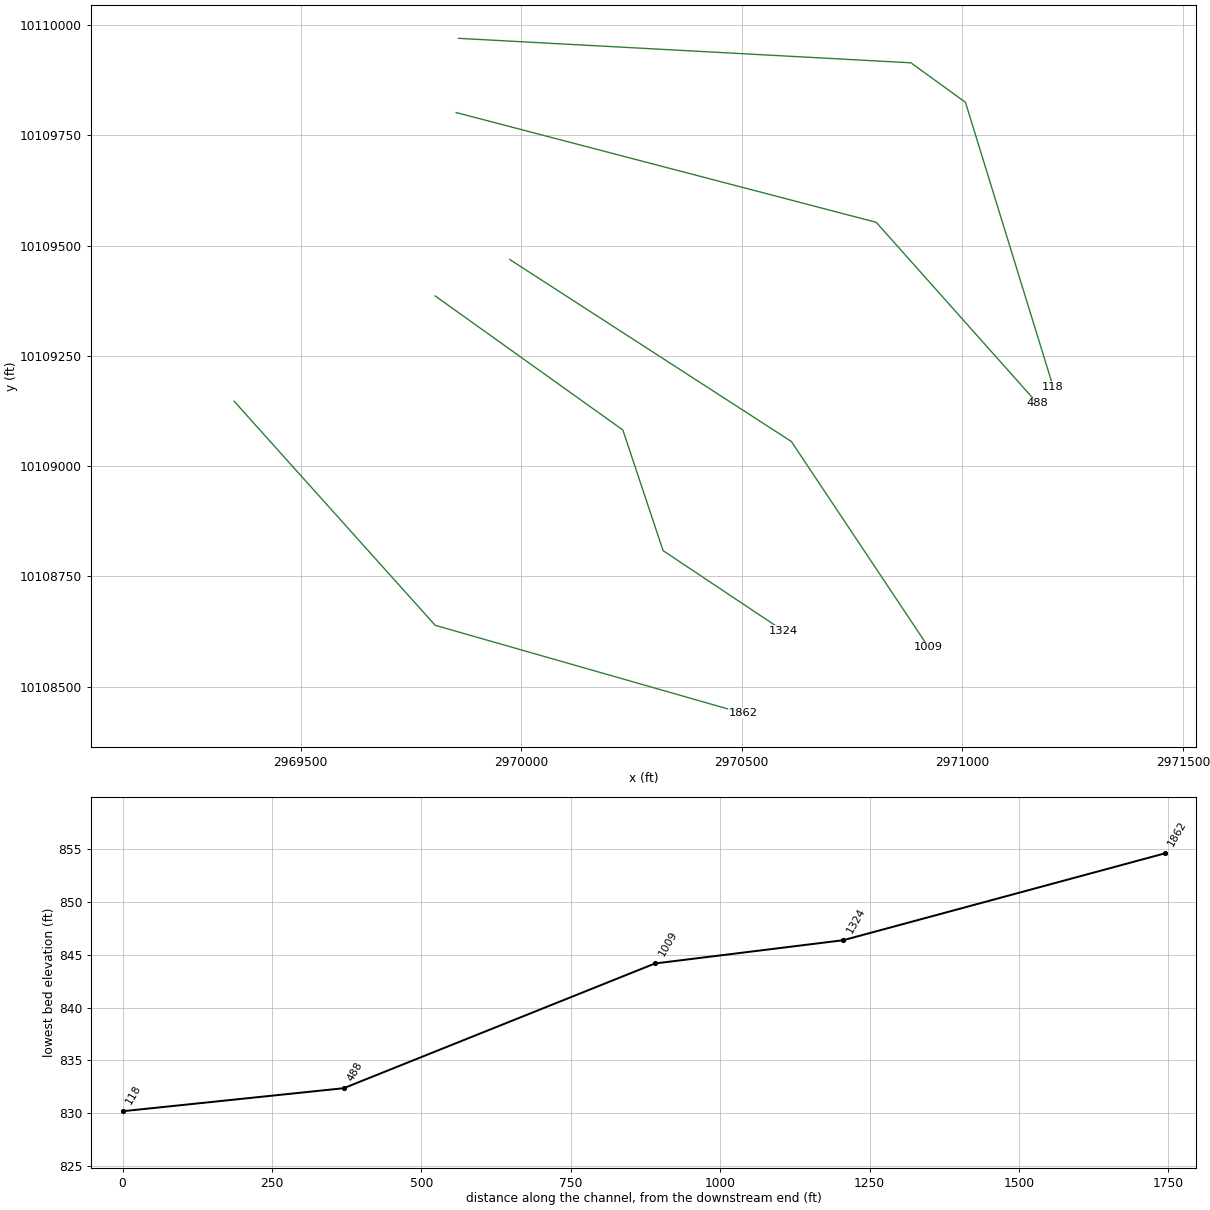
HEC-RAS study UNT 0027 IN LATR.prj: UNT 1027 IN LATR Base Level Engineering

--- UNT 0027 IN LATR.g01 (geometry) --- (continued)

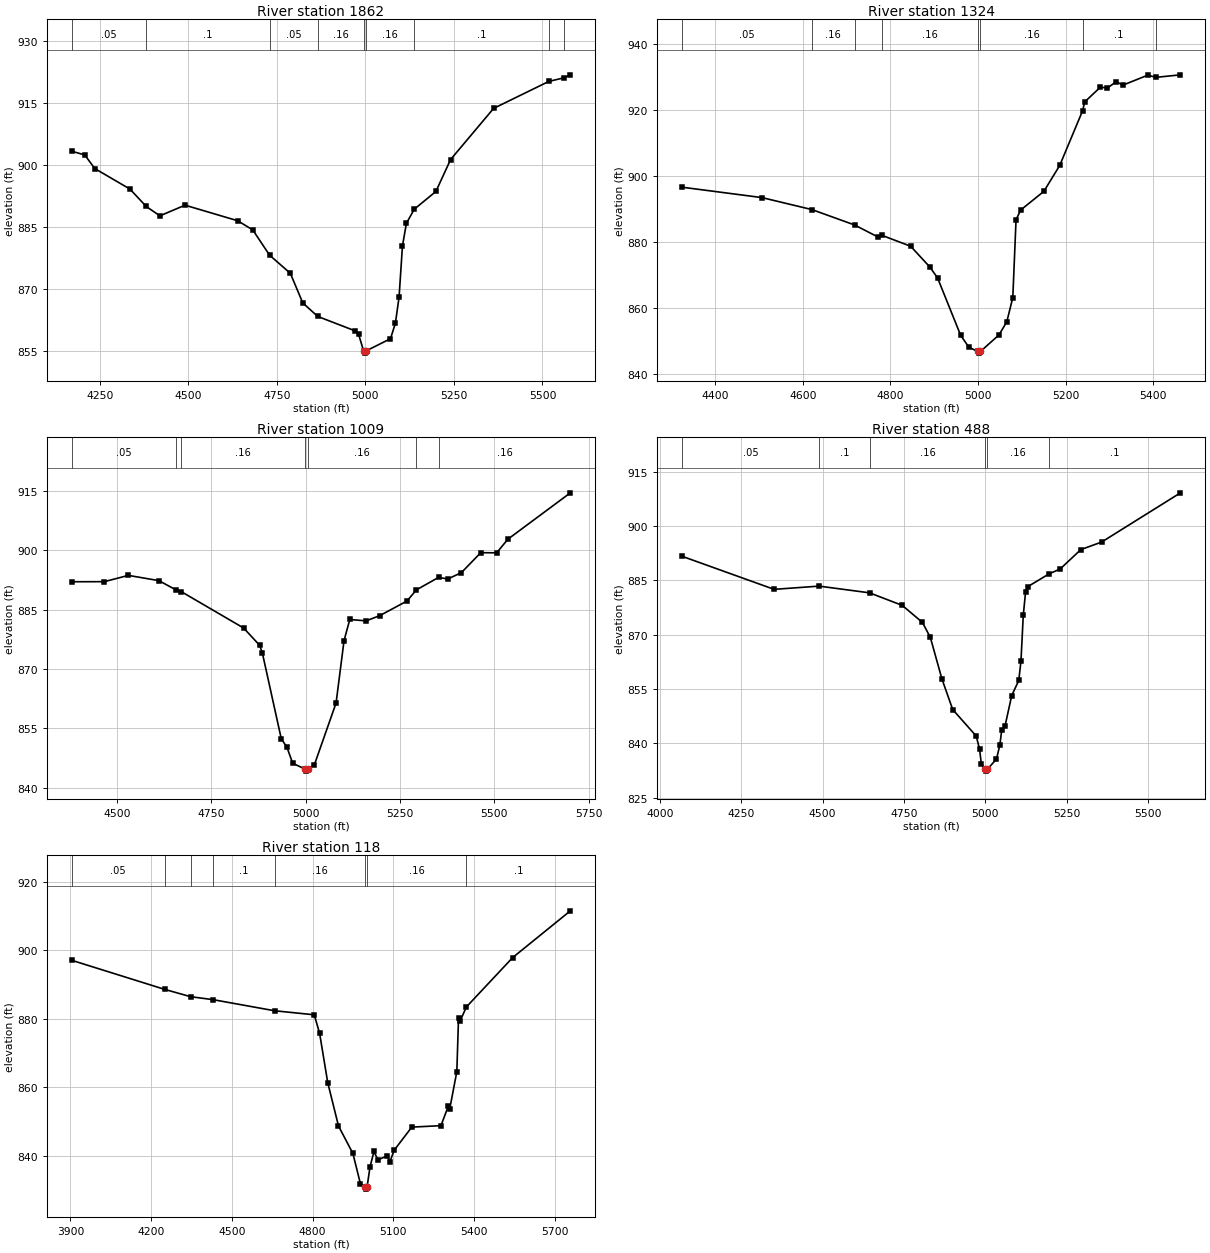
Type RM Length L Ch R = 1 ,1862    ,538,538,538
BEGIN DESCRIPTION:
UNT 1027 IN LATR 4.0
END DESCRIPTION:
XS GIS Cut Line= 3
      2969349.35     10109147.07      2969805.07     10108639.26
      2970503.71     10108439.65
#Sta/Elev= 30
    4170  903.45  4207.1  902.55  4235.5  899.25  4334.9  894.28  4380.9  890.07
  4419.4  887.81  4490.4  890.39  4639.2  886.62  4681.8   884.4  4729.2   878.3
  4787.9   873.9  4823.1  866.72  4865.5  863.46  4970.2     860  4980.6  859.16
    4995  855.09  4997.8  854.59    5001  855.09  5070.8  858.08  5084.6  861.82
    5095  868.12  5104.6  880.55  5115.8  886.01    5138  889.42    5199   893.7
  5240.6  901.44  5362.1  913.81  5518.2  920.34    5560  921.19  5578.9  921.93
#Mann= 9 ,-1 , 0
    4170     .05       0  4380.9      .1       0  4729.2     .05       0
  4865.5     .16       0    4995     .07       0    5001     .16       0
    5138      .1       0  5518.2     .16       0    5560      .1       0
Bank Sta=4995,5001
XS Rating Curve= 0 ,0
Exp/Cntr=0.3,0.1

Type RM Length L Ch R = 1 ,1324    ,315,315,315
BEGIN DESCRIPTION:
UNT 1027 IN LATR 3.0
END DESCRIPTION:
XS GIS Cut Line= 4
      2969805.05     10109385.81      2970230.42     10109081.97
      2970321.57     10108808.53      2970594.26     10108626.74
#Sta/Elev= 30
  4323.7  896.71    4507  893.54  4621.1   889.9  4718.4  885.24  4771.2  881.63
  4780.9  882.09  4846.4  878.79  4889.9  872.53  4907.8  869.19  4960.5  851.79
  4979.4  848.14  4999.7  846.87  5002.4  846.37  5005.7  846.87    5048  851.89
  5065.9  855.88  5079.6  863.24    5087  886.83  5097.6  889.77  5150.6  895.45
  5186.7  903.29  5238.9  919.87  5243.8  922.56  5279.8  927.08  5294.9  926.74
  5315.9   928.7  5330.9  927.65    5388  930.69  5406.2  930.01  5462.4  930.78
#Mann= 8 ,-1 , 0
  4323.7     .05       0  4621.1     .16       0  4718.4      .1       0
  4780.9     .16       0  4999.7     .07       0  5005.7     .16       0
  5238.9      .1       0  5406.2     .16       0
Bank Sta=4999.7,5005.7
XS Rating Curve= 0 ,0
Exp/Cntr=0.3,0.1

Type RM Length L Ch R = 1 ,1009    ,521,521,521
BEGIN DESCRIPTION:
UNT 1027 IN LATR 2.0
END DESCRIPTION:
XS GIS Cut Line= 3
      2969974.31     10109468.28      2970612.37     10109055.93
      2970923.66     10108588.98
#Sta/Elev= 30
  4380.2  892.09    4467  892.11  4530.4   893.7  4611.4  892.37  4657.1     890
  4670.8  889.58  4835.8  880.38    4878  876.03  4885.2  874.14  4935.4  852.39
  4950.6  850.18  4965.8  846.15  4999.1  844.67  5001.8  844.17  5005.1  844.67
  5023.2  845.79  5080.6  861.41  5101.7  877.18  5116.9  882.54  5160.2  882.19
  5196.3  883.52  5268.4  887.21  5293.2  890.03  5352.1  893.19  5376.6  892.79
  5412.6   894.4  5463.7  899.44  5505.8  899.41  5535.8  902.87  5701.1  914.59
#Mann= 7 ,-1 , 0
  4380.2     .05       0  4657.1      .1       0  4670.8     .16       0
  4999.1     .07       0  5005.1     .16       0  5293.2      .1       0
  5352.1     .16       0
Bank Sta=4999.1,5005.1
XS Rating Curve= 0 ,0
Exp/Cntr=0.3,0.1

Type RM Length L Ch R = 1 ,488     ,370,370,370
BEGIN DESCRIPTION:
Mapping XS 3a1ffefd
END DESCRIPTION:
XS GIS Cut Line= 3
      2969852.58     10109801.53      2970804.72     10109552.76
      2971169.83     10109142.91
#Sta/Elev= 30
  4066.9  891.69  4350.9  882.53  4489.1  883.42  4644.2  881.57  4744.8   878.1
  4806.8   873.4  4831.1  869.26  4866.4  857.89  4899.8  849.36  4972.2  842.03
  4982.5  838.36  4987.8  834.35  5000.2  832.86  5002.9  832.36  5006.2  832.86
  5034.2  835.67  5044.5  839.45  5050.4  843.61  5060.3  844.69  5081.2  853.22
  5102.9  857.39  5109.6  862.72  5116.7  875.34  5123.8  881.83  5130.5  883.27
  5196.3  886.82    5230  888.14  5293.6   893.5  5357.7  895.59  5599.9  909.17
#Mann= 6 ,-1 , 0
  4066.9     .05       0  4489.1      .1       0  4644.2     .16       0
  5000.2     .07       0  5006.2     .16       0  5196.3      .1       0
Bank Sta=5000.2,5006.2
XS Rating Curve= 0 ,0
Exp/Cntr=0.3,0.1

Type RM Length L Ch R = 1 ,118     ,0,0,0
BEGIN DESCRIPTION:
UNT 1027 IN LATR 1.0
END DESCRIPTION:
XS GIS Cut Line= 4
      2969857.89     10109969.78      2970883.47      10109914.3
      2971006.97     10109824.81      2971205.65     10109180.43
#Sta/Elev= 30
  3904.3  897.08    4251  888.55  4346.7  886.43  4430.3  885.56  4659.3  882.31
  4806.2  881.14  4826.2   875.7  4856.3  861.33  4896.3  848.64  4949.9   840.6
  4977.9  831.72  4996.3  830.68    4999  830.18  5002.3  830.68  5013.4  836.64
  5028.1  841.19  5042.8  838.75  5078.4  839.92  5087.1  838.12  5103.3  841.55
  5168.7  848.31  5277.1  848.73  5304.6  854.44  5309.8  853.62  5336.2  864.55
  5342.5  880.22  5347.7  879.22  5371.7  883.43  5543.7  897.86  5758.2  911.53
#Mann= 8 ,-1 , 0
  3904.3     .05       0    4251      .1       0  4346.7     .05       0
  4430.3      .1       0  4659.3     .16       0  4996.3     .07       0
  5002.3     .16       0  5371.7      .1       0
Bank Sta=4996.3,5002.3
XS Rating Curve= 0 ,0
Exp/Cntr=0.3,0.1

Chan Stop Cuts=-1
Use User Specified Reach Order=0
Composite Channel Slope=5