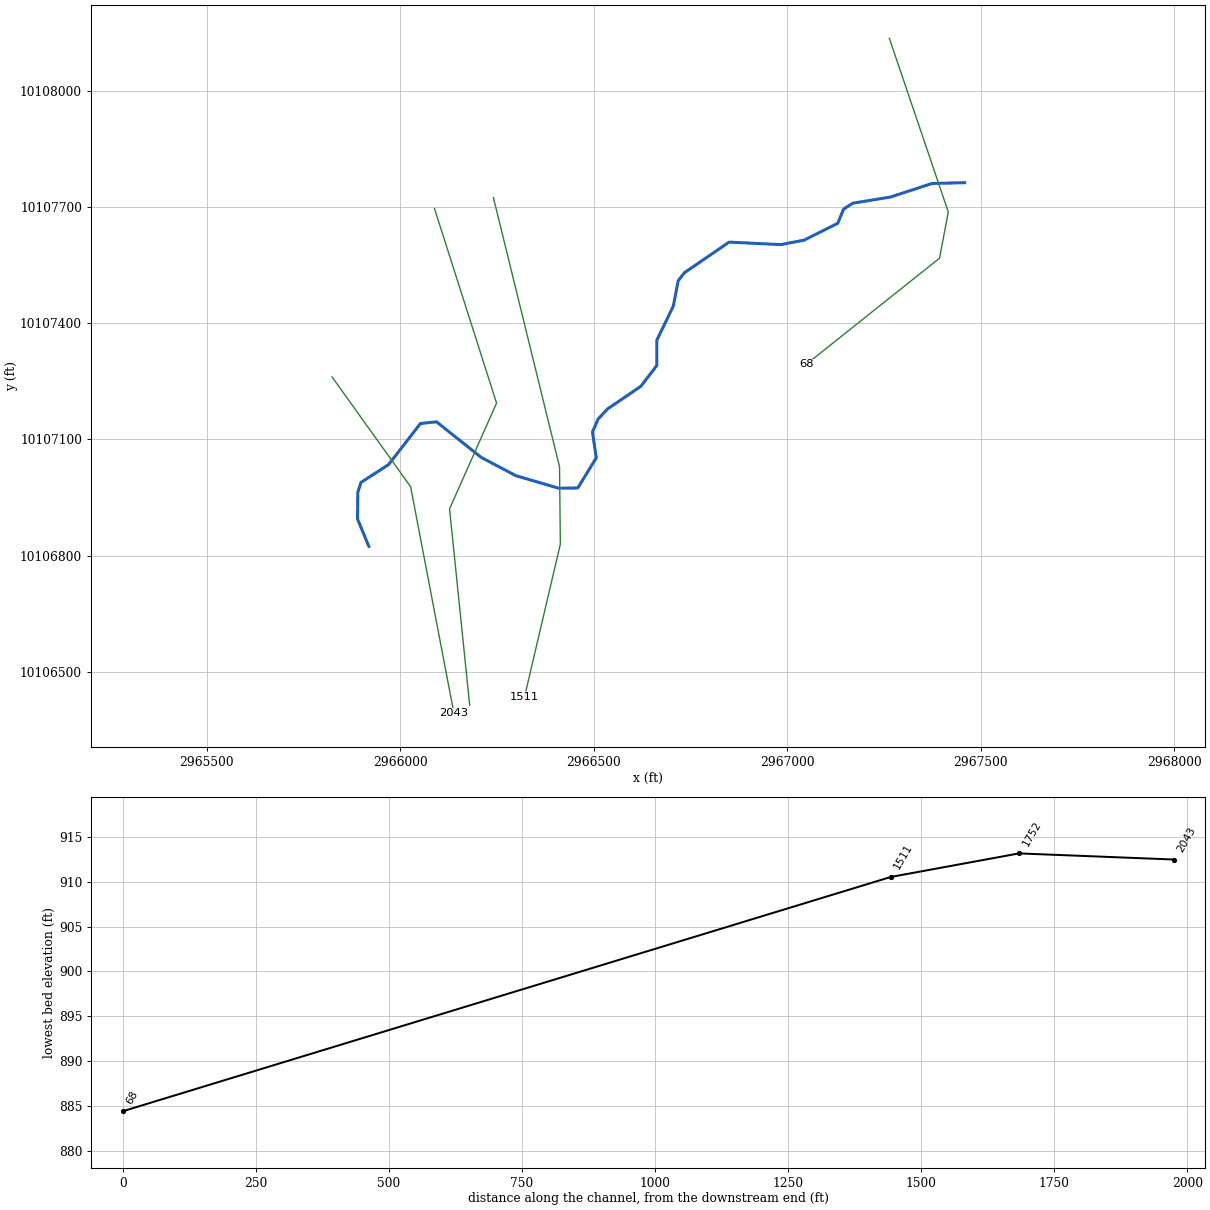
--- UNT 0028 IN LATR.prj (project) ---

Proj Title=UNT 1028 IN LATR Base Level Engineering
Current Plan=p01
Default Exp/Contr=0.3,0.1
English Units
Geom File=g01
Flow File=f01
Plan File=p01
BEGIN DESCRIPTION:
UNT 1028 IN LATR
END DESCRIPTION:

--- UNT 0028 IN LATR.p01 (plan) ---

Plan Title=Multiple Run
Short Identifier=Multiple
Geom File=g01
Flow File=f01
Subcritical Flow
K Sum by GR= 0
Std Step Tol= 0.01
Critical Tol= 0.01
Num of Std Step Trials= 20
Max Error Tol= 0.3
Flow Tol Ratio= 0.001
Split Flow NTrial= 30
Split Flow Tol= 0.02
Split Flow Ratio= 0.02
Log Output Level= 0
Friction Slope Method= 1
Unsteady Friction Slope Method= 2
Unsteady Bridges Friction Slope Method= 1
Parabolic Critical Depth
Global Vel Dist=  1 , 1 , 1
Global Log Level= 0
CheckData=True
Encroach Param= -1, 0, 0, 0
BEGIN DESCRIPTION:
Multiple Run
END DESCRIPTION:

--- UNT 0028 IN LATR.f01 (steady flow) ---

Flow Title=Multiple
Number of Profiles=7
Profile Names=10-year,25-year,50-year,1pct_min,100-year,1pct_plu,500-year
River Rch & RM= UNT 1028 IN LATR,Reach-1,2043
     787    1127    1419    1308    1769    2393    2760
Boundary for River Rch & Prof#=UNT 1028 IN LATR,Reach-1,1
Up Type=0
Dn Type=3
Dn Slope=0.005
Boundary for River Rch & Prof#=UNT 1028 IN LATR,Reach-1,2
Up Type=0
Dn Type=3
Dn Slope=0.005
Boundary for River Rch & Prof#=UNT 1028 IN LATR,Reach-1,3
Up Type=0
Dn Type=3
Dn Slope=0.005
Boundary for River Rch & Prof#=UNT 1028 IN LATR,Reach-1,4
Up Type=0
Dn Type=3
Dn Slope=0.005
Boundary for River Rch & Prof#=UNT 1028 IN LATR,Reach-1,5
Up Type=0
Dn Type=3
Dn Slope=0.005
Boundary for River Rch & Prof#=UNT 1028 IN LATR,Reach-1,6
Up Type=0
Dn Type=3
Dn Slope=0.005
Boundary for River Rch & Prof#=UNT 1028 IN LATR,Reach-1,7
Up Type=0
Dn Type=3
Dn Slope=0.005

--- UNT 0028 IN LATR.g01 (geometry) ---

Geom Title=Existing Conditions

River Reach=UNT 1028 IN LATR,Reach-1
Reach XY= 30
      2965918.47     10106823.73      2965889.28     10106894.33
      2965889.96     10106962.88      2965898.21     10106988.92
      2965969.55     10107034.94      2966051.85     10107141.26
      2966093.52     10107145.61      2966208.97     10107053.59
      2966298.81     10107006.28      2966408.62     10106974.16
      2966458.54     10106974.60      2966506.28     10107052.29
      2966496.63     10107119.45      2966511.09     10107152.73
      2966535.58     10107178.92      2966621.64     10107237.43
      2966662.87     10107291.32      2966663.00     10107356.75
      2966705.54     10107444.94      2966718.08     10107510.19
      2966734.14     10107531.02      2966849.80     10107610.20
      2966983.43     10107603.74      2967043.54     10107615.34
      2967130.56     10107658.86      2967145.55     10107695.41
      2967169.39     10107710.76      2967267.17     10107726.84
      2967374.26     10107761.81      2967458.58     10107763.81

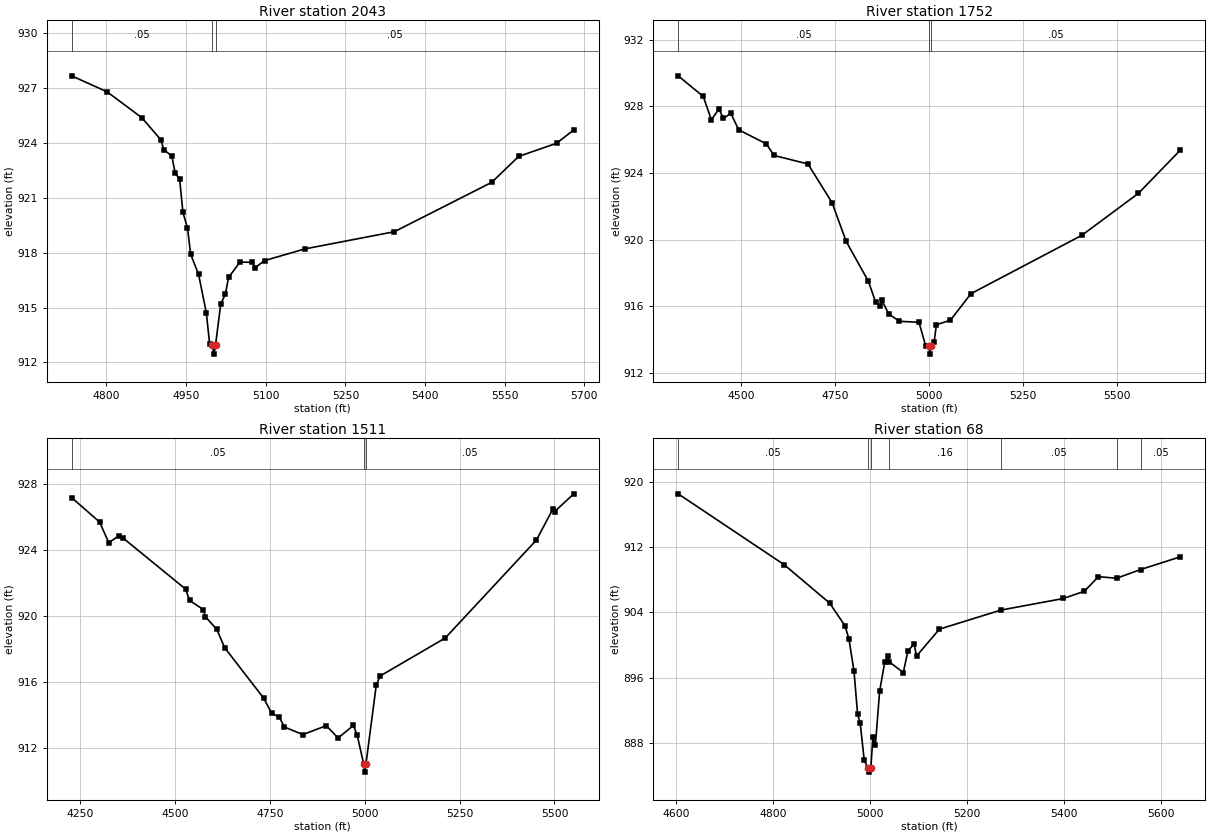
Type RM Length L Ch R = 1,2043,291,291,291
BEGIN DESCRIPTION:
UNT 1028 IN LATR 2.0
END DESCRIPTION:
XS GIS Cut Line= 3
      2965823.40     10107261.69      2966026.53     10106977.83
      2966138.51     10106391.89
#Sta/Elev= 30
  4734.5  927.68  4801.5  926.80  4866.6  925.39  4902.2  924.19  4908.4  923.63
  4923.1  923.29  4929.3  922.38  4937.9  922.01  4944.0  920.22  4952.6  919.35
  4958.7  917.91  4973.5  916.82  4988.2  914.70  4994.4  912.98  4999.5  912.95
  5002.3  912.45  5005.5  912.95  5015.3  915.20  5023.9  915.72  5030.0  916.65
  5051.7  917.49  5074.2  917.47  5080.4  917.19  5097.9  917.57  5174.0  918.21
  5342.3  919.15  5525.5  921.85  5576.4  923.27  5647.7  923.99  5680.1  924.72
#Mann=3,-1,0
  4734.5    0.05       0  4999.5   0.035       0  5005.5    0.05       0
Bank Sta=4999.5,5005.5
Exp/Cntr=0.3,0.1

Type RM Length L Ch R = 1,1752,241,241,241
BEGIN DESCRIPTION:
UNT 1028 IN LATR 1.0
END DESCRIPTION:
XS GIS Cut Line= 4
      2966088.06     10107697.43      2966248.65     10107193.95
      2966127.12     10106920.51      2966179.21     10106412.68
#Sta/Elev= 30
  4331.4  929.83  4398.3  928.59  4419.8  927.19  4440.2  927.84  4452.0  927.27
  4471.7  927.58  4492.7  926.59  4566.2  925.75  4587.2  925.05  4677.3  924.54
  4741.7  922.21  4779.2  919.89  4838.3  917.50  4857.4  916.27  4869.1  916.00
  4874.6  916.35  4892.4  915.54  4921.1  915.10  4973.1  915.04  4990.9  913.64
  4999.4  913.63  5002.1  913.13  5005.4  913.63  5013.3  913.83  5019.6  914.89
  5057.1  915.17  5111.8  916.76  5407.2  920.26  5558.0  922.78  5669.6  925.37
#Mann=3,-1,0
  4331.4    0.05       0  4999.4   0.035       0  5005.4    0.05       0
Bank Sta=4999.4,5005.4
Exp/Cntr=0.3,0.1

Type RM Length L Ch R = 1,1511,1443,1443,1443
BEGIN DESCRIPTION:
Mapping XS 8058b4ee
END DESCRIPTION:
XS GIS Cut Line= 4
      2966240.54     10107725.12      2966411.43     10107029.18
      2966413.49     10106829.45      2966320.83     10106434.11
#Sta/Elev= 30
  4228.4  927.17  4301.9  925.69  4326.1  924.44  4353.4  924.86  4362.5  924.74
  4528.4  921.62  4539.0  920.93  4575.5  920.37  4580.6  919.94  4610.8  919.17
  4631.4  918.06  4734.4  914.99  4755.0  914.09  4775.6  913.84  4788.4  913.25
  4837.4  912.79  4899.1  913.33  4930.0  912.58  4970.5  913.34  4980.5  912.74
  4997.5  911.01  5000.2  910.51  5003.5  911.01  5030.5  915.77  5040.5  916.34
  5212.3  918.65  5452.6  924.60  5495.1  926.45  5500.2  926.32  5550.8  927.40
#Mann=3,-1,0
  4228.4    0.05       0  4997.5   0.035       0  5003.5    0.05       0
Bank Sta=4997.5,5003.5
Exp/Cntr=0.3,0.1

Type RM Length L Ch R = 1,68,0,0,0
BEGIN DESCRIPTION:
UNT 1028 IN LATR 3.0
END DESCRIPTION:
XS GIS Cut Line= 4
      2967263.87     10108137.00      2967416.26     10107688.08
      2967393.61     10107568.66      2967049.76     10107294.82
#Sta/Elev= 30
  4604.2  918.52  4822.4  909.86  4916.6  905.14  4948.0  902.38  4956.2  900.79
  4966.7  896.81  4974.1  891.55  4979.4  890.46  4987.8  885.92  4995.4  884.96
  4998.1  884.46  5001.4  884.96  5005.5  888.72  5010.8  887.76  5019.5  894.36
  5030.1  897.94  5036.9  898.69  5039.7  897.94  5068.3  896.65  5077.9  899.30
  5090.5  900.14  5095.6  898.67  5142.8  901.96  5269.5  904.29  5398.4  905.71
  5441.7  906.60  5470.5  908.38  5508.0  908.19  5557.4  909.25  5639.4  910.81
#Mann=7,-1,0
  4604.2    0.05       0  4995.4   0.035       0  5001.4    0.05       0
  5039.7    0.16       0  5269.5    0.05       0  5508.0     0.1       0
  5557.4    0.05       0
Bank Sta=4995.4,5001.4
Exp/Cntr=0.3,0.1

Chan Stop Cuts=-1