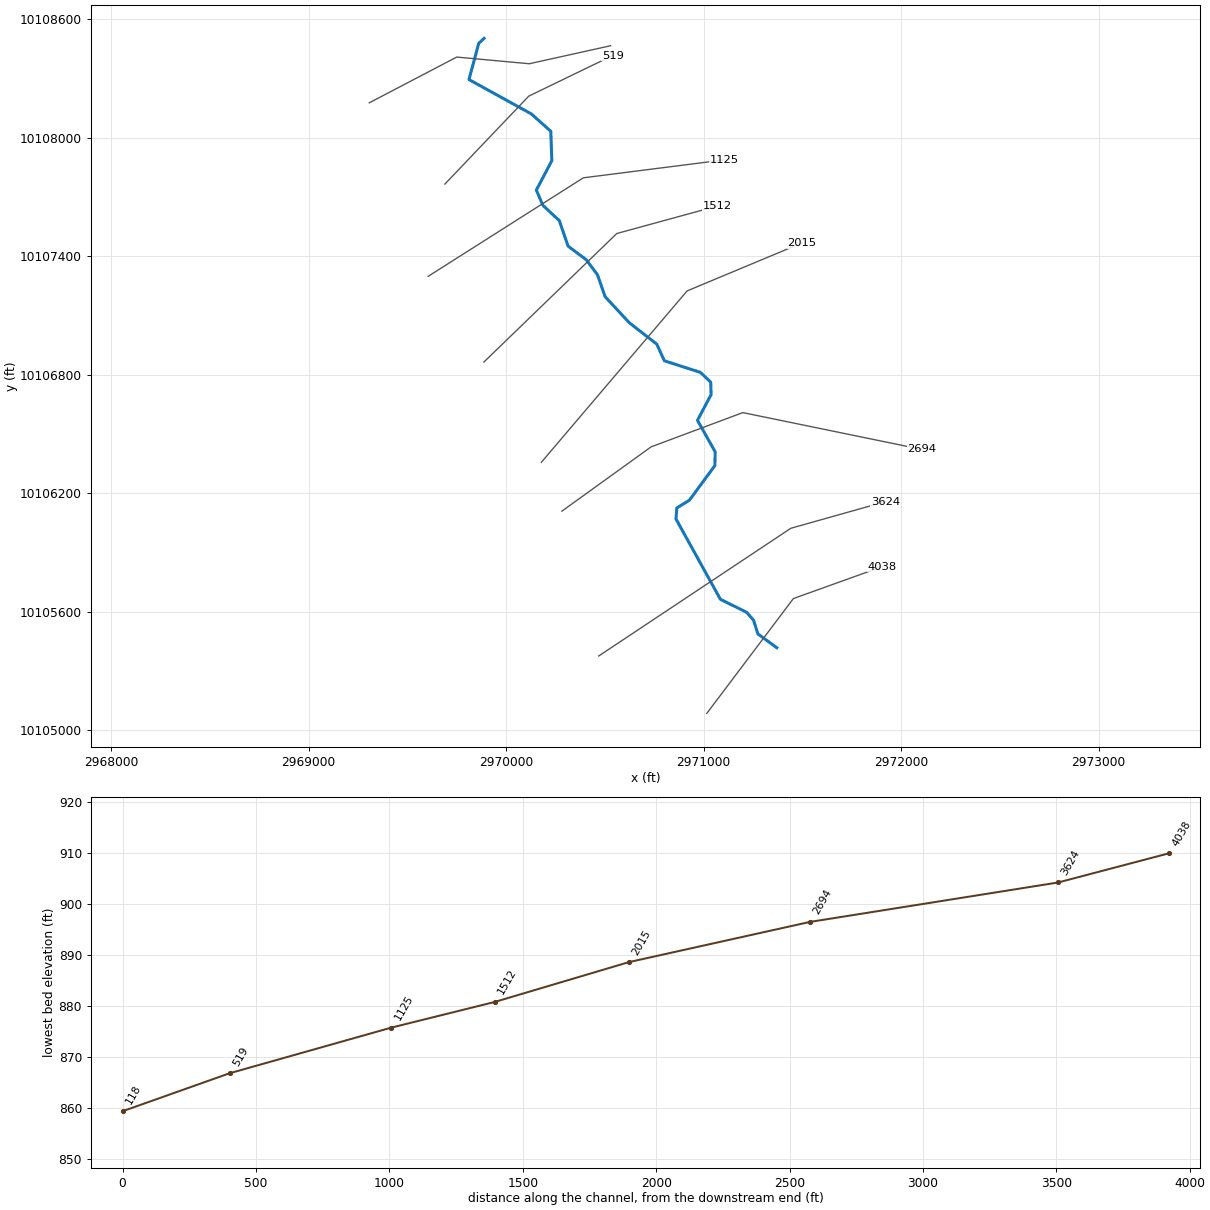
--- UNT 0029 IN LATR.prj (project) ---

Proj Title=UNT 1029 IN LATR Base Level Engineering
Current Plan=p01
Default Exp/Contr=0.3,0.1
English Units
Geom File=g01
Flow File=f01
Plan File=p01
Y Axis Title=Elevation
X Axis Title(PF)=Main Channel Distance
X Axis Title(XS)=Station
BEGIN DESCRIPTION:
UNT 1029 IN LATR
END DESCRIPTION:
DSS Export Rating Curves= 0
DSS Export Rating Curve Sorted= 0
DSS Export Volume Flow Curves= 0
DXF OffsetX= 0
DXF OffsetY= 0
DXF ScaleX= 1
DXF ScaleY= 10

--- UNT 0029 IN LATR.p01 (plan) ---

Plan Title=Multiple Run
Short Identifier=Multiple
Geom File=g01
Flow File=f01
Subcritical Flow
K Sum by GR= 0
Std Step Tol= 0.01
Critical Tol= 0.01
Num of Std Step Trials= 20
Max Error Tol= 0.3
Flow Tol Ratio= 0.001
Split Flow NTrial= 30
Split Flow Tol= 0.02
Split Flow Ratio= 0.02
Log Output Level= 0
Friction Slope Method= 1
Unsteady Friction Slope Method= 2
Unsteady Bridges Friction Slope Method= 1
Parabolic Critical Depth
Global Vel Dist=  1 , 1 , 1
Global Log Level= 0
CheckData=True
Encroach Param= -1, 0, 0, 0
BEGIN DESCRIPTION:
Multiple Run
END DESCRIPTION:

--- UNT 0029 IN LATR.f01 (steady flow) ---

Flow Title=Multiple
Number of Profiles=7
Profile Names=10-year,25-year,50-year,1pct_min,100-year,1pct_plu,500-year
River Rch & RM= UNT 1029 IN LATR,Reach-1,4038
     716    1020    1279    1175    1589    2149    2459
River Rch & RM= UNT 1029 IN LATR,Reach-1,2694
     888    1279    1617    1495    2022    2735    3176
Boundary for River Rch & Prof#=UNT 1029 IN LATR,Reach-1,1
Up Type=0
Dn Type=3
Dn Slope=0.005
Boundary for River Rch & Prof#=UNT 1029 IN LATR,Reach-1,2
Up Type=0
Dn Type=3
Dn Slope=0.005
Boundary for River Rch & Prof#=UNT 1029 IN LATR,Reach-1,3
Up Type=0
Dn Type=3
Dn Slope=0.005
Boundary for River Rch & Prof#=UNT 1029 IN LATR,Reach-1,4
Up Type=0
Dn Type=3
Dn Slope=0.005
Boundary for River Rch & Prof#=UNT 1029 IN LATR,Reach-1,5
Up Type=0
Dn Type=3
Dn Slope=0.005
Boundary for River Rch & Prof#=UNT 1029 IN LATR,Reach-1,6
Up Type=0
Dn Type=3
Dn Slope=0.005
Boundary for River Rch & Prof#=UNT 1029 IN LATR,Reach-1,7
Up Type=0
Dn Type=3
Dn Slope=0.005

--- UNT 0029 IN LATR.g01 (geometry) ---

Geom Title=Existing Conditions
Program Version=4.10

River Reach=UNT 1029 IN LATR,Reach-1
Reach XY= 30
      2971370.16     10105417.19      2971274.65     10105486.84
      2971252.64     10105556.21      2971217.73     10105596.38
      2971084.61      10105662.7      2970859.93     10106069.43
      2970864.19       10106125.       2970927.7     10106164.02
      2971056.89     10106339.59      2971058.42     10106409.02
      2970968.77     10106568.98      2971037.82      10106699.3
      2971035.69     10106762.42      2970983.54     10106811.82
      2970801.29     10106870.33      2970762.95      10106954.7
      2970624.17     10107062.61      2970501.05     10107195.41
      2970462.69     10107306.06      2970405.88     10107382.18
      2970313.82     10107451.11       2970269.3     10107580.58
      2970186.34     10107657.53      2970153.05     10107734.92
      2970231.47      10107884.1      2970226.27      10108032.9
      2970127.42     10108121.11      2969812.09     10108294.82
      2969861.33     10108478.01      2969888.47     10108503.73

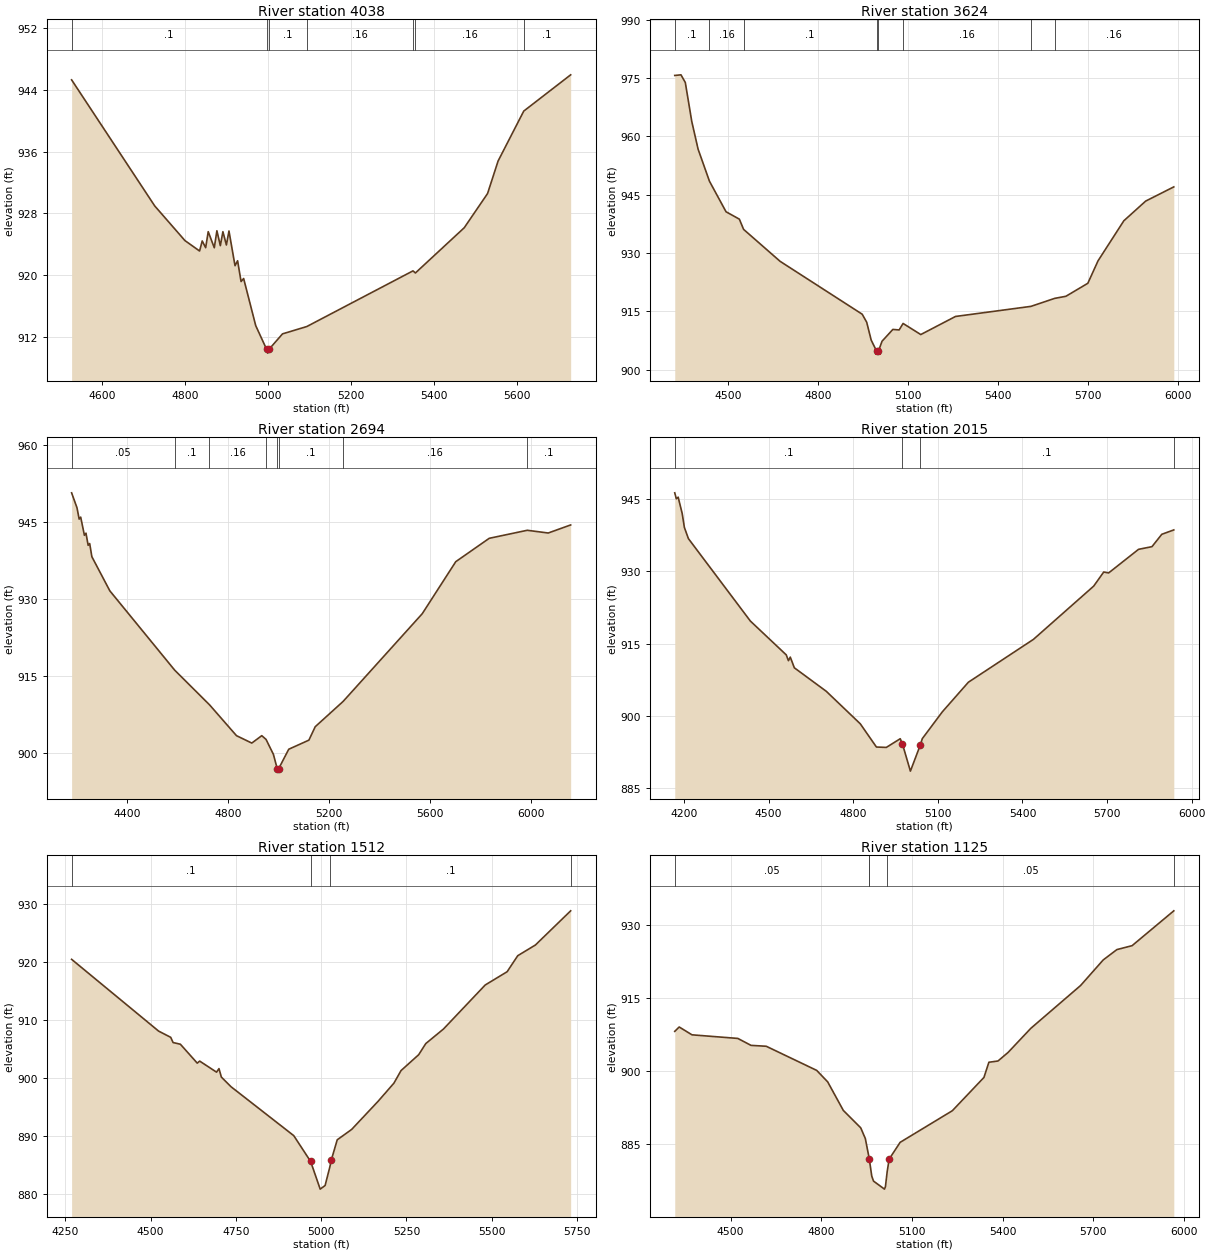
Type RM Length L Ch R = 1 ,4038    ,414,414,414
BEGIN DESCRIPTION:
UNT 1029 IN LATR 9.0
END DESCRIPTION:
XS GIS Cut Line= 3
      2971015.99     10105084.55      2971454.38     10105666.17
      2971901.38     10105826.75
#Sta/Elev= 30
  4526.9  945.28  4727.3  928.97  4800.1  924.49  4835.5  923.14  4841.8  924.44
  4850.1  923.57  4856.3  925.64  4870.9  923.56  4877.2  925.76  4885.5  923.83
  4891.7  925.64  4900.1  923.92  4906.3  925.73  4920.9  921.24  4927.1  921.88
  4935.5  919.19  4941.7  919.58  4970.8  913.49    4997  910.43  4999.7  909.93
    5003  910.43  5035.4  912.42    5094  913.37    5350  920.57  5355.9   920.3
  5473.6  926.15  5529.8  930.57  5555.2  934.78  5617.1  941.24  5730.2  945.93
#Mann= 7 ,-1 , 0
  4526.9      .1       0    4997     .07       0    5003      .1       0
    5094     .16       0    5350      .1       0  5355.9     .16       0
  5617.1      .1       0
Bank Sta=4997,5003
XS Rating Curve= 0 ,0
Exp/Cntr=0.3,0.1

Type RM Length L Ch R = 1 ,3624    ,930,930,930
BEGIN DESCRIPTION:
UNT 1029 IN LATR 8.0
END DESCRIPTION:
XS GIS Cut Line= 3
      2970469.13     10105375.37      2971441.36     10106022.08
      2971918.79     10106156.62
#Sta/Elev= 30
  4323.2  975.71  4343.9  975.87  4358.4  973.89  4379.9  963.87    4401  956.74
  4438.9  948.48  4494.2  940.61  4538.6  938.71  4552.7  936.08  4674.5  927.85
  4948.1  914.24  4963.1  912.17  4978.1  907.57  4996.2  904.72  4998.9  904.22
  5002.2  904.72  5014.2  907.28  5050.3  910.32  5071.3  910.19  5084.4  911.86
  5143.4     909  5259.2  913.66  5510.8  916.26  5589.9  918.32  5627.1  918.85
  5700.3   922.2  5734.3  927.98  5820.3  938.29  5893.1  943.36  5986.9  947.02
#Mann= 8 ,-1 , 0
  4323.2      .1       0  4438.9     .16       0  4552.7      .1       0
  4996.2     .07       0  5002.2      .1       0  5084.4     .16       0
  5510.8      .1       0  5589.9     .16       0
Bank Sta=4996.2,5002.2
XS Rating Curve= 0 ,0
Exp/Cntr=0.3,0.1

Type RM Length L Ch R = 1 ,2694    ,679,679,679
BEGIN DESCRIPTION:
UNT 1029 IN LATR 6.0
END DESCRIPTION:
XS GIS Cut Line= 4
      2970282.52     10106108.89      2970733.89      10106434.4
       2971198.3     10106608.01      2972104.42     10106421.59
#Sta/Elev= 30
  4180.3  950.64  4201.6  947.73  4210.2  945.53  4216.3  945.91    4231  942.38
  4237.2  942.79  4245.8  940.43  4251.9  940.77  4260.5  938.21  4331.7  931.57
  4588.7  916.13  4726.5   909.4  4833.6  903.38  4894.2  901.94  4933.8  903.38
  4950.7  902.65  4979.8  899.75  4994.9  896.98  4997.7  896.48  5000.9  896.98
  5040.6  900.74  5120.5  902.51  5145.5  905.12  5256.2  910.05  5569.7  927.12
  5702.4  937.24  5835.1  941.79  5985.7  943.35  6068.7  942.82  6157.7  944.39
#Mann= 8 ,-1 , 0
  4180.3     .05       0  4588.7      .1       0  4726.5     .16       0
  4950.7      .1       0  4994.9     .07       0  5000.9      .1       0
  5256.2     .16       0  5985.7      .1       0
Bank Sta=4994.9,5000.9
XS Rating Curve= 0 ,0
Exp/Cntr=0.3,0.1

Type RM Length L Ch R = 1 ,2015    ,503,503,503
BEGIN DESCRIPTION:
UNT 1029 IN LATR 4.0
END DESCRIPTION:
XS GIS Cut Line= 3
      2970178.34     10106356.27      2970916.18     10107224.33
      2971497.77     10107467.38
#Sta/Elev= 30
  4167.1  946.21  4172.7  944.97  4179.2  945.31  4193.5  941.93  4201.2  939.05
  4215.5  936.73  4435.2  919.66  4562.5  912.65  4570.3  911.45  4576.8  912.19
  4591.1  909.98  4704.2  905.12    4825  898.38  4882.2  893.57  4917.3  893.49
  4966.7  895.29  4974.4  894.23  5002.7  888.58  5038.1  894.03  5044.7  895.29
  5116.1  900.87  5208.3  906.99  5438.9  915.86  5652.6  926.89  5688.2  929.81
  5705.6  929.62  5811.7  934.51  5859.3  935.06  5894.1  937.62  5936.7  938.53
#Mann= 4 ,-1 , 0
  4167.1      .1       0  4974.4     .05       0  5038.1      .1       0
  5936.7     .16       0
Bank Sta=4974.4,5038.1
XS Rating Curve= 0 ,0
Exp/Cntr=0.3,0.1

Type RM Length L Ch R = 1 ,1512    ,387,387,387
BEGIN DESCRIPTION:
UNT 1029 IN LATR 3.0
END DESCRIPTION:
XS GIS Cut Line= 3
       2969887.5     10106864.06      2970560.28     10107515.13
       2971068.1     10107654.02
#Sta/Elev= 30
  4268.7   920.5  4523.7  908.09  4559.2  907.01  4566.1  906.11  4587.5  905.82
  4636.9  902.55  4644.1   902.9  4693.5  900.99  4700.6   901.6  4707.6  900.14
  4735.9  898.47  4919.8  890.01  4969.2  885.55  4997.3  880.76  5011.7  881.39
  5025.8  884.65    5030  885.82  5047.2  889.29  5089.6  891.09  5167.3  895.97
  5213.4  899.09  5234.2  901.26    5286  904.01  5306.7  905.93  5358.6  908.45
  5480.9  916.06  5545.2  918.36  5576.3  921.13  5628.1  922.98  5731.4  928.89
#Mann= 4 ,-1 , 0
  4268.7      .1       0  4969.2     .05       0  5025.8      .1       0
  5731.4     .16       0
Bank Sta=4969.2,5030
XS Rating Curve= 0 ,0
Exp/Cntr=0.3,0.1

Type RM Length L Ch R = 1 ,1125    ,606,606,606
BEGIN DESCRIPTION:
UNT 1029 IN LATR 2.0
END DESCRIPTION:
XS GIS Cut Line= 3
      2969605.41     10107298.11      2970391.01     10107797.25
      2971105.29     10107888.16
#Sta/Elev= 30
  4315.6  908.16  4330.3  909.06  4372.6  907.45  4524.2  906.71    4568  905.28
  4618.2   905.1  4785.1  900.14  4821.5  897.78  4873.2  891.91  4930.8  888.33
    4946  886.13    4959  881.98  4967.2  878.42  4973.1  877.38  5009.3  875.73
  5012.5  876.23  5018.2  879.28  5024.8   881.9  5061.2  885.35  5233.9  891.85
  5338.4  898.69  5354.7  901.81  5384.9  902.07  5418.4  903.84  5493.2  908.77
  5658.1  917.59    5733  922.85  5778.1  924.97  5828.5  925.78  5966.4  932.94
#Mann= 5 ,-1 , 0
  4315.6     .05       0    4959     .16       0    4959    .035       0
  5018.2     .05       0  5966.4      .1       0
Bank Sta=4959,5024.8
XS Rating Curve= 0 ,0
Exp/Cntr=0.3,0.1

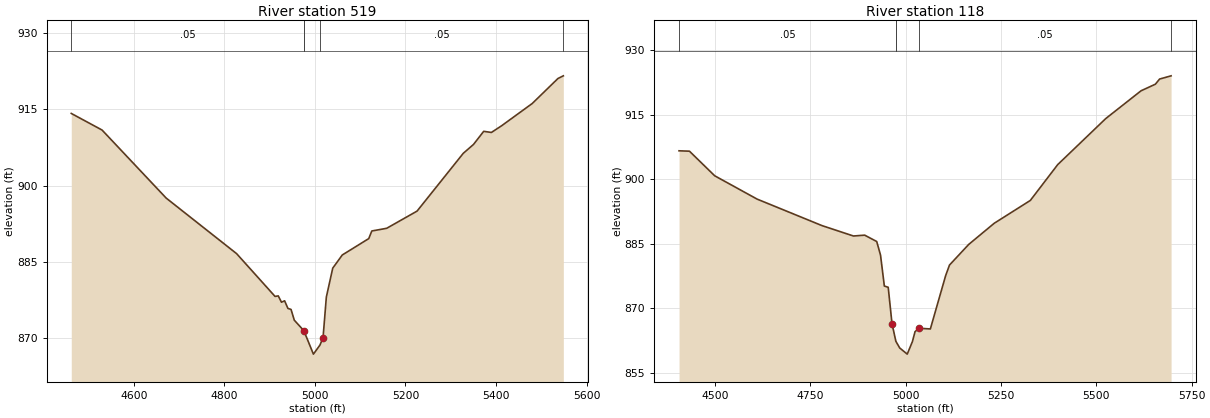
Type RM Length L Ch R = 1 ,519     ,401,401,401
BEGIN DESCRIPTION:
Mapping XS a4af0a79
END DESCRIPTION:
XS GIS Cut Line= 3
      2969690.17      10107765.6      2970114.68     10108210.94
      2970539.19     10108416.69
#Sta/Elev= 30
  4461.8  914.21  4529.9  910.93  4671.4  897.53  4827.1  886.57    4912  878.14
    4919  878.25  4926.2     877  4933.1  877.28  4940.4  875.78  4947.3  875.58
  4954.5  873.46  4975.6  871.39  4996.7  866.77  5011.1  868.54    5018  870.02
  5025.3  878.02  5039.4  883.71  5060.5  886.31    5119  889.54  5125.7  891.04
  5158.6  891.57  5225.7  894.96  5327.8  906.35  5350.3  908.09  5372.9  910.68
  5389.9  910.46  5412.5  911.78  5480.2  916.17  5536.9  921.09  5548.8  921.62
#Mann= 5 ,-1 , 0
  4461.8     .05       0  4975.6     .16       0  4975.6    .035       0
  5011.1     .05       0  5548.8      .1       0
Bank Sta=4975.6,5018
XS Rating Curve= 0 ,0
Exp/Cntr=0.3,0.1

Type RM Length L Ch R = 1 ,118     ,0,0,0
BEGIN DESCRIPTION:
UNT 1029 IN LATR 1.0
END DESCRIPTION:
XS GIS Cut Line= 4
      2969307.38     10108177.09       2969750.1     10108408.86
      2970117.28       10108375.      2970528.75     10108466.15
#Sta/Elev= 30
  4406.2  906.59  4433.5   906.5  4499.7  900.78  4610.6  895.37  4780.9   889.2
  4863.5  886.78  4892.8  886.98  4924.4   885.5  4934.4  882.34  4944.4  875.15
  4954.5  874.86  4964.5   866.4  4974.6  862.31  4984.6  860.76  5004.4  859.32
    5018  862.24  5024.8  864.53  5034.8  865.34    5065  865.17  5105.1  877.57
  5115.2  880.03  5165.4  884.81  5232.4  889.74  5327.1  895.05  5398.8  903.37
  5524.9  914.09  5617.3  920.54  5654.8  922.07    5666  923.27  5696.1  924.02
#Mann= 5 ,-1 , 0
  4406.2     .05       0  4974.6     .16       0  4974.6    .035       0
  5034.8     .05       0  5696.1     .16       0
Bank Sta=4964.5,5034.8
XS Rating Curve= 0 ,0
Exp/Cntr=0.3,0.1

Chan Stop Cuts=-1
Use User Specified Reach Order=0
Composite Channel Slope=5