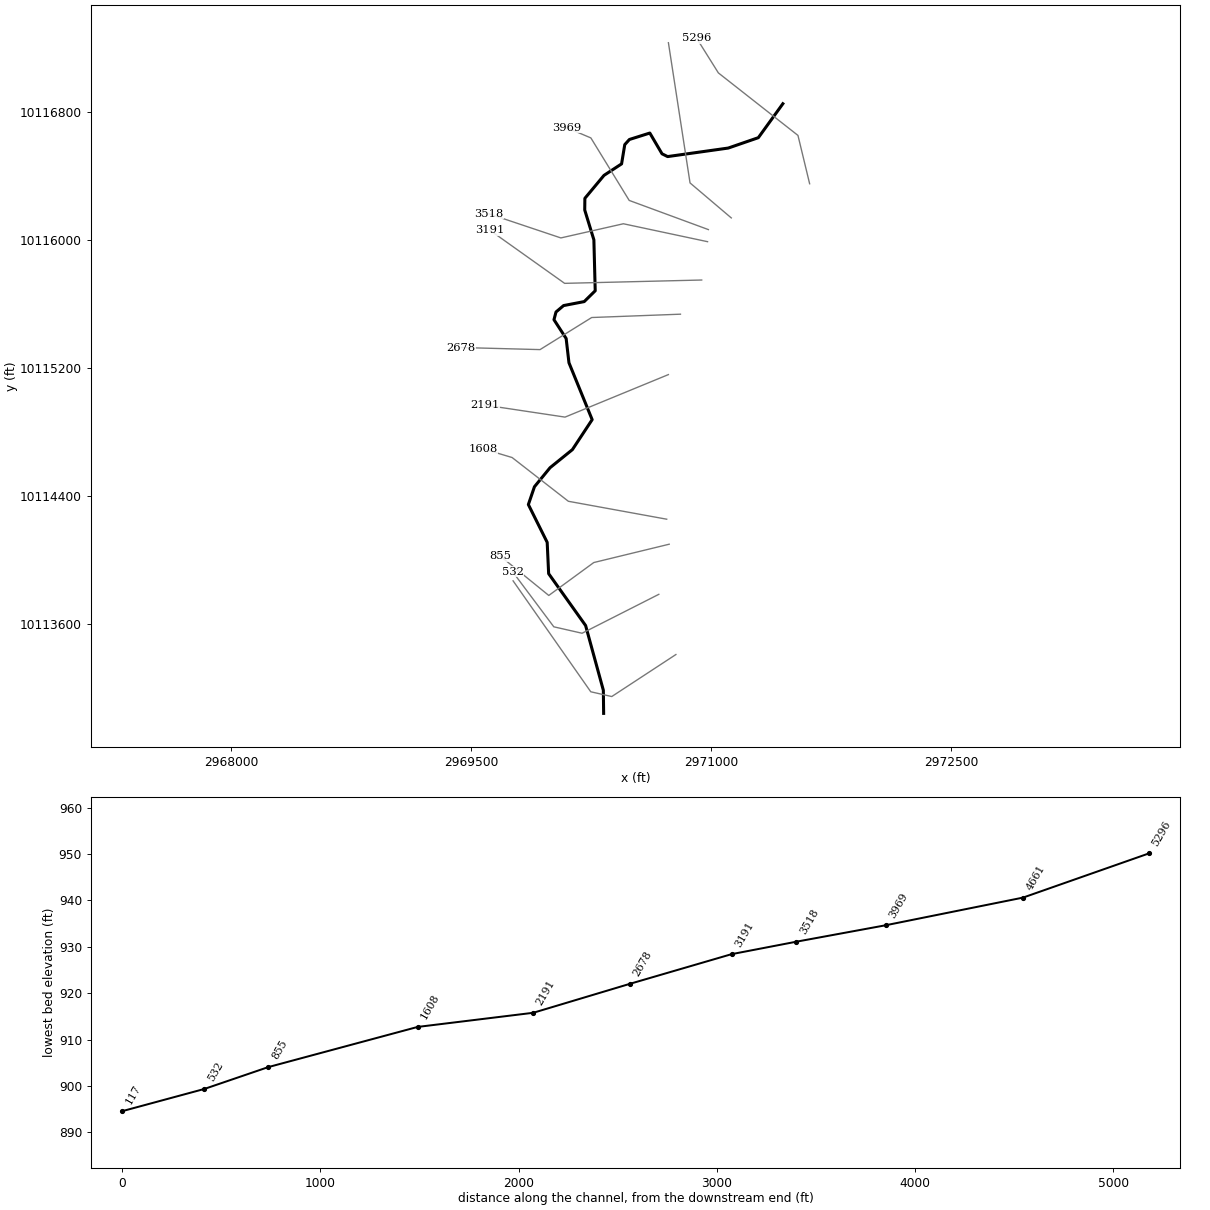
--- UNT 0031 IN LATR.prj (project) ---

Proj Title=UNT 1031 IN LATR Base Level Engineering
Current Plan=p01
Default Exp/Contr=0.3,0.1
English Units
Geom File=g01
Flow File=f01
Plan File=p01
BEGIN DESCRIPTION:
UNT 1031 IN LATR
END DESCRIPTION:

--- UNT 0031 IN LATR.p01 (plan) ---

Plan Title=Multiple Run
Short Identifier=Multiple
Geom File=g01
Flow File=f01
Subcritical Flow
K Sum by GR= 0
Std Step Tol= 0.01
Critical Tol= 0.01
Num of Std Step Trials= 20
Max Error Tol= 0.3
Flow Tol Ratio= 0.001
Split Flow NTrial= 30
Split Flow Tol= 0.02
Split Flow Ratio= 0.02
Log Output Level= 0
Friction Slope Method= 1
Unsteady Friction Slope Method= 2
Unsteady Bridges Friction Slope Method= 1
Parabolic Critical Depth
Global Vel Dist=  1 , 1 , 1
Global Log Level= 0
CheckData=True
Encroach Param= -1, 0, 0, 0
BEGIN DESCRIPTION:
Multiple Run
END DESCRIPTION:

--- UNT 0031 IN LATR.f01 (steady flow) ---

Flow Title=Multiple
Number of Profiles=7
Profile Names=10-year,25-year,50-year,1pct_min,100-year,1pct_plu,500-year
River Rch & RM= UNT 1031 IN LATR,Reach-1,5296
    1021    1492    1905    1780    2407    3255    3857
Boundary for River Rch & Prof#=UNT 1031 IN LATR,Reach-1,1
Up Type=0
Dn Type=3
Dn Slope=0.005
Boundary for River Rch & Prof#=UNT 1031 IN LATR,Reach-1,2
Up Type=0
Dn Type=3
Dn Slope=0.005
Boundary for River Rch & Prof#=UNT 1031 IN LATR,Reach-1,3
Up Type=0
Dn Type=3
Dn Slope=0.005
Boundary for River Rch & Prof#=UNT 1031 IN LATR,Reach-1,4
Up Type=0
Dn Type=3
Dn Slope=0.005
Boundary for River Rch & Prof#=UNT 1031 IN LATR,Reach-1,5
Up Type=0
Dn Type=3
Dn Slope=0.005
Boundary for River Rch & Prof#=UNT 1031 IN LATR,Reach-1,6
Up Type=0
Dn Type=3
Dn Slope=0.005
Boundary for River Rch & Prof#=UNT 1031 IN LATR,Reach-1,7
Up Type=0
Dn Type=3
Dn Slope=0.005

--- UNT 0031 IN LATR.g01 (geometry) ---

Geom Title=Existing Conditions

River Reach=UNT 1031 IN LATR,Reach-1
Reach XY= 30
      2971448.47     10116853.73      2971295.27     10116641.59
      2971107.23     10116576.72      2970728.26     10116523.45
      2970693.32     10116540.81      2970617.12     10116670.53
      2970489.51     10116630.28      2970460.48     10116598.19
      2970440.58     10116477.81      2970330.75     10116406.08
      2970211.16     10116262.52      2970210.27     10116189.62
      2970267.44     10116003.22      2970275.81     10115684.84
      2970207.13     10115617.19      2970078.16     10115592.29
      2970030.74     10115552.22      2970018.08     10115503.98
      2970094.16     10115386.55      2970111.66     10115235.09
      2970256.71     10114879.43      2970133.22     10114692.06
      2969993.64     10114579.09      2969896.01     10114460.03
      2969858.01     10114348.73      2969975.66     10114112.57
      2969984.76     10113916.91      2970215.80     10113592.63
      2970326.63     10113188.13      2970328.47     10113043.73

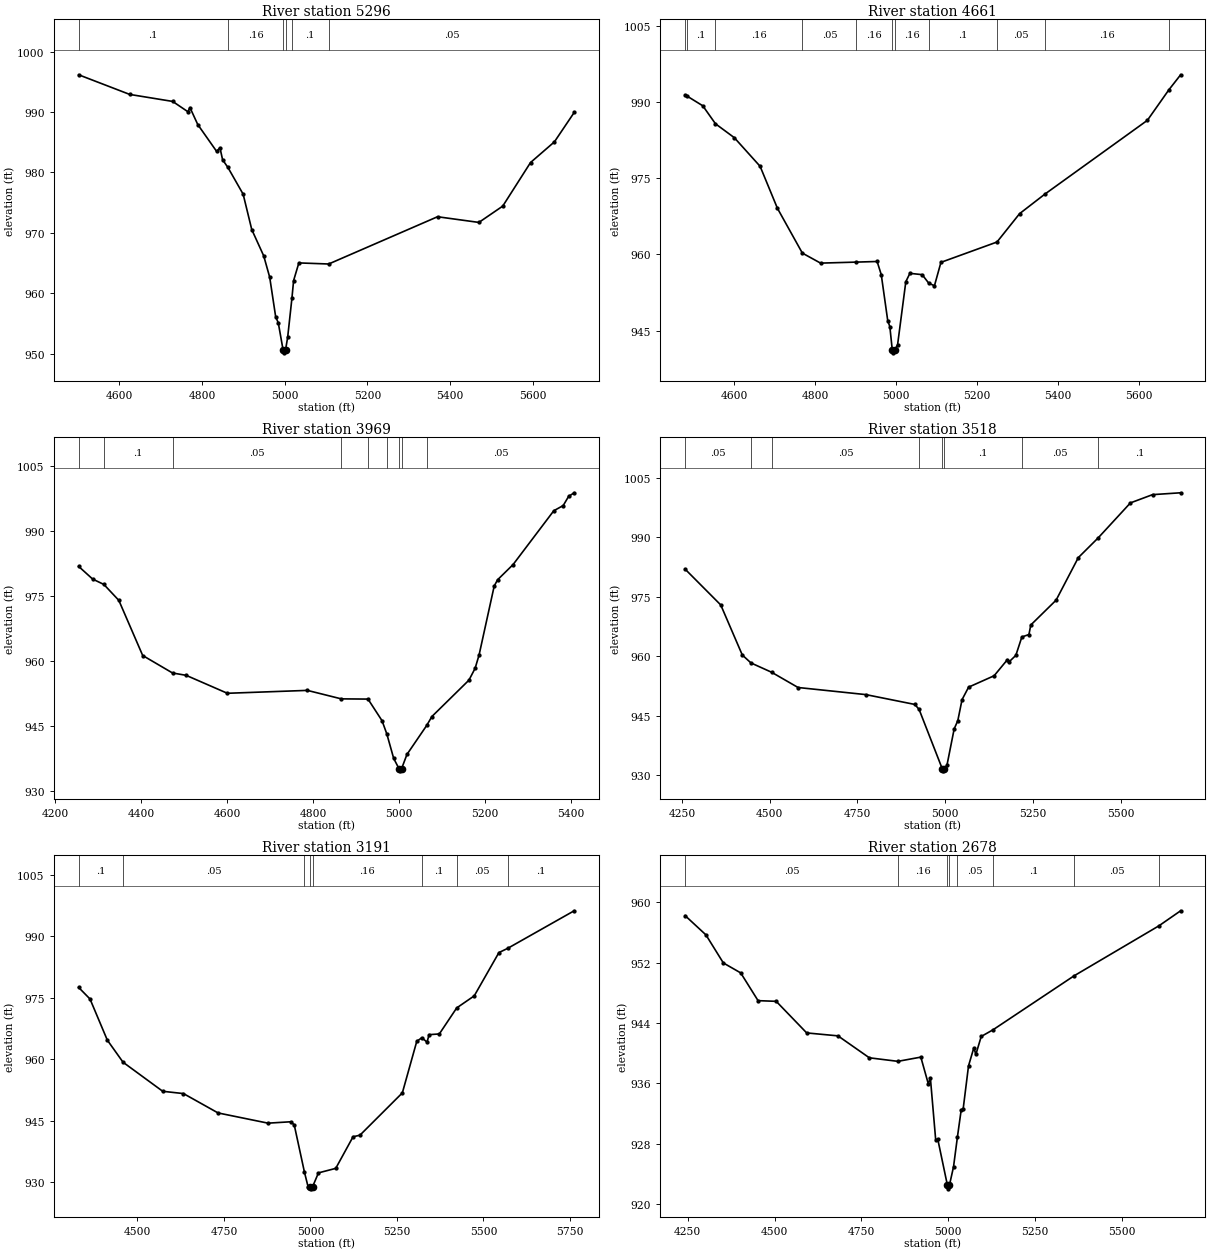
Type RM Length L Ch R = 1,5296,635,635,635
BEGIN DESCRIPTION:
UNT 1031 IN LATR 10.0
END DESCRIPTION:
XS GIS Cut Line= 4
      2971615.83     10116353.63      2971542.92     10116655.67
      2971045.53     10117046.29      2970910.12     10117262.42
#Sta/Elev= 30
  4501.8  996.16  4625.3  992.91  4729.2  991.75  4765.9  990.05  4771.0  990.73
  4789.9  987.92  4835.5  983.48  4843.5  984.09  4849.9  982.10  4862.8  980.82
  4899.6  976.40  4920.4  970.55  4949.3  966.20  4963.8  962.66  4978.2  956.13
  4984.6  955.10  4996.1  950.65  4998.8  950.15  5002.1  950.65  5007.2  952.70
  5017.5  959.16  5021.6  962.11  5034.3  965.03  5106.4  964.85  5369.6  972.67
  5469.6  971.73  5527.3  974.43  5594.5  981.64  5652.2  985.06  5700.0  989.92
#Mann=6,-1,0
  4501.8     0.1       0  4862.8    0.16       0  4996.1    0.07       0
  5002.1    0.16       0  5017.5     0.1       0  5106.4    0.05       0
Bank Sta=4996.1,5002.1
Exp/Cntr=0.3,0.1

Type RM Length L Ch R = 1,4661,692,692,692
BEGIN DESCRIPTION:
UNT 1031 IN LATR 9.0
END DESCRIPTION:
XS GIS Cut Line= 3
      2971126.25     10116140.04      2970868.44     10116358.79
      2970733.24     10117235.01
#Sta/Elev= 30
  4478.1  991.34  4482.7  991.14  4521.8  989.22  4553.2  985.68  4599.8  982.94
  4663.5  977.31  4706.3  969.05  4767.9  960.24  4812.9  958.27  4901.5  958.47
  4952.7  958.59  4962.9  956.00  4979.0  946.90  4984.1  945.79  4990.2  941.12
  4993.0  940.62  4996.2  941.12  5003.3  942.24  5023.6  954.62  5033.7  956.26
  5064.0  956.00  5080.6  954.29  5094.4  953.83  5110.4  958.42  5248.9  962.42
  5304.8  968.00  5367.4  971.85  5620.6  986.36  5673.6  992.35  5702.8  995.32
#Mann=11,-1,0
  4478.1    0.16       0  4482.7     0.1       0  4553.2    0.16       0
  4767.9    0.05       0  4901.5    0.16       0  4990.2    0.07       0
  4996.2    0.16       0  5080.6     0.1       0  5248.9    0.05       0
  5367.4    0.16       0  5673.6     0.1       0
Bank Sta=4990.2,4996.2
Exp/Cntr=0.3,0.1

Type RM Length L Ch R = 1,3969,451,451,451
BEGIN DESCRIPTION:
UNT 1031 IN LATR 8.0
END DESCRIPTION:
XS GIS Cut Line= 4
      2970983.06     10116067.11      2970488.23     10116249.42
      2970248.65     10116640.04      2970094.97     10116705.17
#Sta/Elev= 30
  4254.5  981.90  4287.1  978.97  4313.2  977.73  4348.0  974.05  4403.5  961.31
  4472.9  957.27  4504.5  956.73  4600.4  952.58  4786.4  953.25  4865.4  951.29
  4927.5  951.24  4960.1  946.25  4971.2  943.21  4987.2  937.54  4999.6  935.16
  5002.4  934.66  5005.6  935.16  5018.1  938.45  5064.2  945.17  5076.1  947.21
  5162.3  955.62  5176.7  958.37  5185.8  961.42  5221.0  977.35  5228.8  978.80
  5264.9  982.32  5359.6  994.76  5381.5  995.96  5394.1  998.08  5407.0  998.91
#Mann=9,-1,0
  4254.5    0.05       0  4313.2     0.1       0  4472.9    0.05       0
  4865.4     0.1       0  4927.5    0.05       0  4971.2     0.1       0
  4999.6    0.07       0  5005.6     0.1       0  5064.2    0.05       0
Bank Sta=4999.6,5005.6
Exp/Cntr=0.3,0.1

Type RM Length L Ch R = 1,3518,327,327,327
BEGIN DESCRIPTION:
UNT 1031 IN LATR 7.0
END DESCRIPTION:
XS GIS Cut Line= 4
      2970977.85     10115991.60      2970451.78     10116103.59
      2970061.15     10116015.04      2969612.02     10116165.62
#Sta/Elev= 30
  4259.0  981.94  4360.6  972.91  4422.0  960.30  4446.7  958.30  4505.8  955.94
  4580.9  952.11  4774.1  950.32  4913.7  947.84  4925.8  946.59  4991.9  931.61
  4994.6  931.11  4997.9  931.61  5005.3  932.56  5025.8  941.69  5036.1  943.75
  5048.2  949.05  5066.9  952.20  5139.6  955.07  5177.6  959.14  5182.7  958.61
  5201.5  960.21  5218.6  964.84  5238.8  965.46  5244.1  967.86  5316.2  974.12
  5379.5  984.84  5436.5  989.85  5528.0  998.63  5591.1 1000.71  5671.1 1001.18
#Mann=8,-1,0
  4259.0    0.05       0  4446.7     0.1       0  4505.8    0.05       0
  4925.8     0.1       0  4991.9    0.07       0  4997.9     0.1       0
  5218.6    0.05       0  5436.5     0.1       0
Bank Sta=4991.9,4997.9
Exp/Cntr=0.3,0.1

Type RM Length L Ch R = 1,3191,513,513,513
BEGIN DESCRIPTION:
UNT 1031 IN LATR 6.0
END DESCRIPTION:
XS GIS Cut Line= 3
      2970941.37     10115752.02      2970084.59     10115731.19
      2969615.85     10116064.51
#Sta/Elev= 30
  4330.1  977.52  4363.0  974.69  4413.0  964.67  4458.5  959.28  4573.1  952.20
  4633.1  951.64  4733.1  946.92  4877.5  944.43  4943.2  944.77  4953.2  944.02
  4982.8  932.47  4993.2  928.94  5000.2  928.92  5003.0  928.42  5006.2  928.92
  5023.2  932.31  5073.2  933.41  5123.2  941.11  5143.2  941.50  5265.7  951.81
  5307.4  964.38  5322.1  965.26  5337.0  964.17  5343.1  966.00  5372.6  966.18
  5422.8  972.52  5473.5  975.46  5544.8  986.01  5570.1  987.04  5762.3  996.20
#Mann=8,-1,0
  4330.1     0.1       0  4458.5    0.05       0  4982.8    0.16       0
  5000.2    0.07       0  5006.2    0.16       0  5322.1     0.1       0
  5422.8    0.05       0  5570.1     0.1       0
Bank Sta=5000.2,5006.2
Exp/Cntr=0.3,0.1

Type RM Length L Ch R = 1,2678,487,487,487
BEGIN DESCRIPTION:
UNT 1031 IN LATR 5.0
END DESCRIPTION:
XS GIS Cut Line= 4
      2970808.55     10115538.48      2970253.86     10115517.65
      2969930.94     10115317.13      2969438.71     10115330.15
#Sta/Elev= 30
  4242.2  958.26  4302.3  955.70  4352.4  951.98  4402.4  950.66  4452.4  946.98
  4504.7  946.89  4592.5  942.70  4682.6  942.31  4773.0  939.40  4855.2  938.93
  4921.3  939.49  4942.9  935.94  4948.8  936.75  4964.2  928.47  4970.1  928.61
  4997.8  922.52  5000.6  922.02  5003.8  922.52  5015.5  924.94  5026.9  928.95
  5037.4  932.42  5043.3  932.62  5058.7  938.33  5074.0  940.72  5079.9  939.85
  5095.3  942.23  5129.5  943.12  5362.4  950.26  5607.1  956.90  5669.8  958.90
#Mann=8,-1,0
  4242.2    0.05       0  4855.2    0.16       0  4997.8    0.07       0
  5003.8    0.16       0  5026.9    0.05       0  5129.5     0.1       0
  5362.4    0.05       0  5607.1     0.1       0
Bank Sta=4997.8,5003.8
Exp/Cntr=0.3,0.1

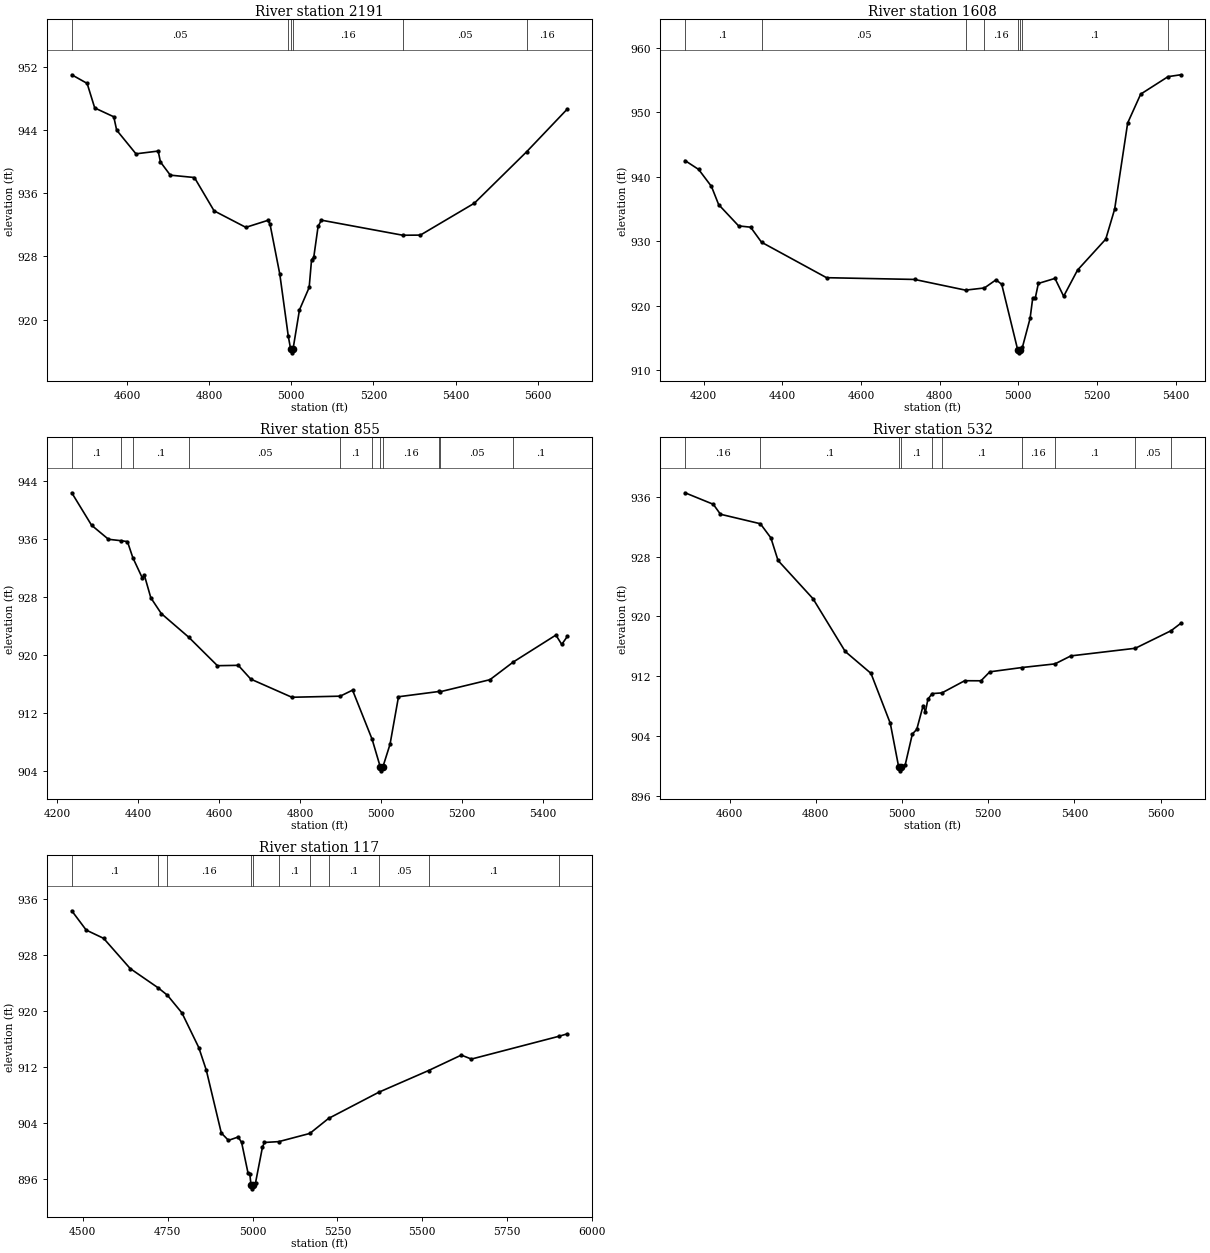
Type RM Length L Ch R = 1,2191,583,583,583
BEGIN DESCRIPTION:
UNT 1031 IN LATR 4.0
END DESCRIPTION:
XS GIS Cut Line= 3
      2970733.06     10115160.89      2970087.19     10114895.25
      2969584.60     10114970.77
#Sta/Elev= 30
  4465.6  950.99  4503.0  949.90  4521.5  946.79  4567.9  945.67  4574.9  943.98
  4621.9  940.98  4676.0  941.33  4681.5  939.95  4705.5  938.28  4764.2  937.98
  4812.1  933.76  4889.4  931.67  4942.7  932.55  4948.1  932.12  4972.1  925.74
  4992.8  917.87  4998.4  916.28  5001.2  915.78  5004.4  916.28  5020.0  921.22
  5043.6  924.06  5049.4  927.57  5054.8  927.89  5065.3  931.78  5073.3  932.58
  5271.7  930.67  5314.4  930.69  5445.8  934.73  5573.0  941.24  5672.2  946.66
#Mann=6,-1,0
  4465.6    0.05       0  4992.8    0.16       0  4998.4    0.07       0
  5004.4    0.16       0  5271.7    0.05       0  5573.0    0.16       0
Bank Sta=4998.4,5004.4
Exp/Cntr=0.3,0.1

Type RM Length L Ch R = 1,1608,753,753,753
BEGIN DESCRIPTION:
UNT 1031 IN LATR 3.0
END DESCRIPTION:
XS GIS Cut Line= 4
      2970722.57     10114257.24      2970108.03     10114369.21
      2969756.46     10114642.65      2969574.13     10114697.35
#Sta/Elev= 30
  4152.3  942.54  4187.0  941.16  4219.5  938.53  4237.8  935.71  4288.6  932.41
  4319.1  932.21  4346.8  929.88  4512.2  924.38  4735.9  924.11  4865.6  922.45
  4913.7  922.79  4943.2  924.05  4957.7  923.35  4998.2  913.23  5000.9  912.73
  5004.2  913.23  5010.4  913.61  5029.8  918.06  5036.5  921.20  5042.8  921.16
  5050.9  923.49  5093.1  924.27  5115.2  921.50  5150.5  925.56  5222.3  930.36
  5244.9  935.01  5278.0  948.37  5311.1  952.84  5380.7  955.55  5412.7  955.84
#Mann=8,-1,0
  4152.3     0.1       0  4346.8    0.05       0  4865.6     0.1       0
  4913.7    0.16       0  4998.2    0.07       0  5004.2    0.16       0
  5010.4     0.1       0  5380.7    0.05       0
Bank Sta=4998.2,5004.2
Exp/Cntr=0.3,0.1

Type RM Length L Ch R = 1,855,323,323,323
BEGIN DESCRIPTION:
UNT 1031 IN LATR 2.0
END DESCRIPTION:
XS GIS Cut Line= 4
      2970738.20     10114100.97      2970266.88     10113986.40
      2969985.63     10113780.67      2969682.18     10114027.06
#Sta/Elev= 30
  4235.9  942.39  4284.8  937.92  4326.6  935.98  4358.7  935.78  4373.5  935.66
  4386.7  933.46  4410.1  930.66  4415.2  931.05  4431.2  927.92  4457.0  925.75
  4524.6  922.50  4595.8  918.56  4647.3  918.61  4678.2  916.71  4779.7  914.21
  4899.1  914.36  4929.6  915.19  4978.0  908.41  4998.3  904.57  5001.1  904.07
  5004.3  904.57  5022.2  907.73  5043.1  914.28  5143.7  915.01  5146.8  914.98
  5269.0  916.63  5327.0  919.08  5432.0  922.78  5446.4  921.49  5460.3  922.60
#Mann=11,-1,0
  4235.9     0.1       0  4358.7    0.16       0  4386.7     0.1       0
  4524.6    0.05       0  4899.1     0.1       0  4978.0    0.16       0
  4998.3    0.07       0  5004.3    0.16       0  5143.7     0.1       0
  5146.8    0.05       0  5327.0     0.1       0
Bank Sta=4998.3,5004.3
Exp/Cntr=0.3,0.1

Type RM Length L Ch R = 1,532,415,415,415
BEGIN DESCRIPTION:
Mapping XS b8e97a31
END DESCRIPTION:
XS GIS Cut Line= 4
      2970673.26     10113787.72      2970193.76     10113544.48
      2970017.01     10113584.73      2969758.94     10113929.99
#Sta/Elev= 30
  4496.7  936.53  4562.3  934.99  4578.9  933.66  4671.5  932.39  4695.9  930.50
  4712.5  927.48  4793.6  922.37  4868.4  915.31  4928.2  912.38  4973.0  905.70
  4992.5  899.85  4995.2  899.35  4998.5  899.85  5007.6  900.15  5024.2  904.28
  5034.4  904.89  5049.2  908.08  5054.4  907.21  5060.3  908.93  5070.1  909.68
  5092.8  909.77  5145.6  911.40  5183.4  911.39  5203.9  912.59  5277.9  913.16
  5355.1  913.65  5392.0  914.72  5541.6  915.74  5624.6  918.09  5646.7  919.06
#Mann=10,-1,0
  4496.7    0.16       0  4671.5     0.1       0  4992.5    0.07       0
  4998.5     0.1       0  5070.1    0.05       0  5092.8     0.1       0
  5277.9    0.16       0  5355.1     0.1       0  5541.6    0.05       0
  5624.6     0.1       0
Bank Sta=4992.5,4998.5
Exp/Cntr=0.3,0.1

Type RM Length L Ch R = 1,117,0,0,0
BEGIN DESCRIPTION:
UNT 1031 IN LATR 1.0
END DESCRIPTION:
XS GIS Cut Line= 4
      2970780.03     10113411.48      2970379.27     10113148.97
      2970248.01     10113178.72      2969762.50     10113872.06
#Sta/Elev= 30
  4467.3  934.30  4509.9  931.54  4561.2  930.36  4639.5  926.04  4722.3  923.27
  4749.1  922.23  4791.9  919.70  4841.5  914.75  4863.7  911.51  4907.9  902.53
  4929.0  901.48  4957.5  901.96  4967.7  901.19  4986.8  896.76  4992.0  896.64
  4995.5  895.05  4998.2  894.55  5001.5  895.05  5008.7  895.41  5029.2  900.53
  5035.1  901.18  5077.3  901.30  5168.7  902.47  5223.7  904.61  5371.9  908.36
  5518.4  911.46  5615.0  913.67  5644.7  913.10  5904.2  916.38  5927.4  916.71
#Mann=11,-1,0
  4467.3     0.1       0  4722.3    0.05       0  4749.1    0.16       0
  4995.5    0.07       0  5001.5    0.16       0  5077.3     0.1       0
  5168.7    0.16       0  5223.7     0.1       0  5371.9    0.05       0
  5518.4     0.1       0  5904.2    0.05       0
Bank Sta=4995.5,5001.5
Exp/Cntr=0.3,0.1

Chan Stop Cuts=-1