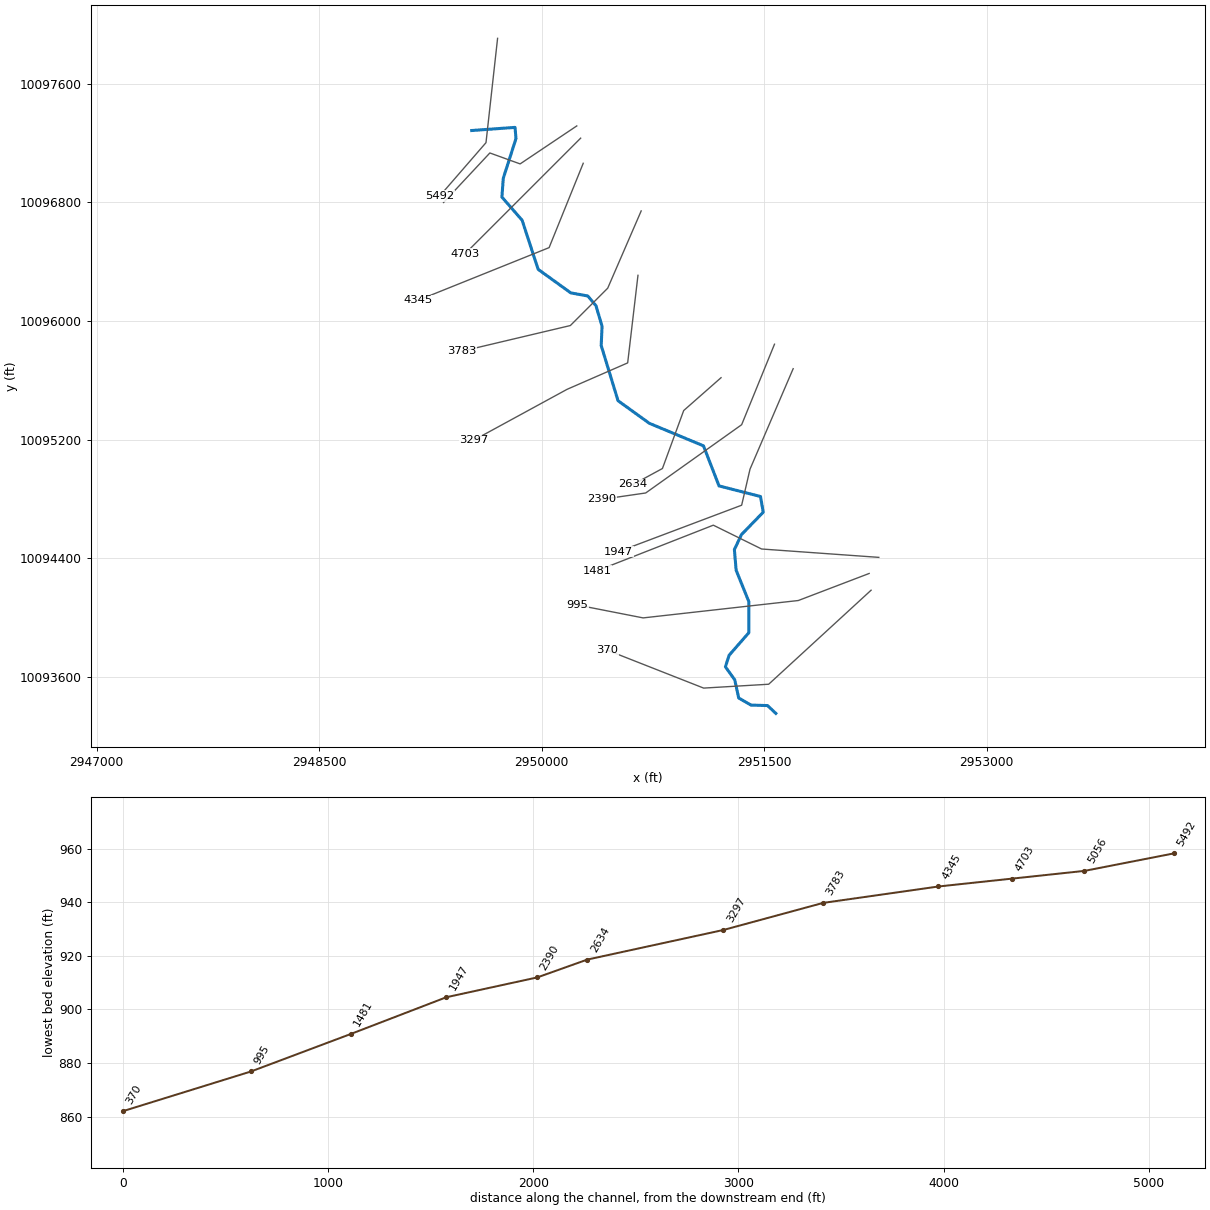
--- UNT 0032 IN LATR.prj (project) ---

Proj Title=UNT 1032 IN LATR Base Level Engineering
Current Plan=p01
Default Exp/Contr=0.3,0.1
English Units
Geom File=g01
Flow File=f01
Plan File=p01
BEGIN DESCRIPTION:
UNT 1032 IN LATR
END DESCRIPTION:

--- UNT 0032 IN LATR.p01 (plan) ---

Plan Title=Multiple Run
Short Identifier=Multiple
Geom File=g01
Flow File=f01
Subcritical Flow
K Sum by GR= 0
Std Step Tol= 0.01
Critical Tol= 0.01
Num of Std Step Trials= 20
Max Error Tol= 0.3
Flow Tol Ratio= 0.001
Split Flow NTrial= 30
Split Flow Tol= 0.02
Split Flow Ratio= 0.02
Log Output Level= 0
Friction Slope Method= 1
Unsteady Friction Slope Method= 2
Unsteady Bridges Friction Slope Method= 1
Parabolic Critical Depth
Global Vel Dist=  1 , 1 , 1
Global Log Level= 0
CheckData=True
Encroach Param= -1, 0, 0, 0
BEGIN DESCRIPTION:
Multiple Run
END DESCRIPTION:

--- UNT 0032 IN LATR.f01 (steady flow) ---

Flow Title=Multiple
Number of Profiles=7
Profile Names=10-year,25-year,50-year,1pct_min,100-year,1pct_plu,500-year
River Rch & RM= UNT 1032 IN LATR,Reach-1,5492
    1475    2195    2836    2677    3621    4896    5928
Boundary for River Rch & Prof#=UNT 1032 IN LATR,Reach-1,1
Up Type=0
Dn Type=3
Dn Slope=0.005
Boundary for River Rch & Prof#=UNT 1032 IN LATR,Reach-1,2
Up Type=0
Dn Type=3
Dn Slope=0.005
Boundary for River Rch & Prof#=UNT 1032 IN LATR,Reach-1,3
Up Type=0
Dn Type=3
Dn Slope=0.005
Boundary for River Rch & Prof#=UNT 1032 IN LATR,Reach-1,4
Up Type=0
Dn Type=3
Dn Slope=0.005
Boundary for River Rch & Prof#=UNT 1032 IN LATR,Reach-1,5
Up Type=0
Dn Type=3
Dn Slope=0.005
Boundary for River Rch & Prof#=UNT 1032 IN LATR,Reach-1,6
Up Type=0
Dn Type=3
Dn Slope=0.005
Boundary for River Rch & Prof#=UNT 1032 IN LATR,Reach-1,7
Up Type=0
Dn Type=3
Dn Slope=0.005

--- UNT 0032 IN LATR.g01 (geometry) ---

Geom Title=Existing Conditions

River Reach=UNT 1032 IN LATR,Reach-1
Reach XY= 30
      2949528.47     10097283.73      2949820.53     10097304.85
      2949826.83     10097229.36      2949741.44     10096962.49
      2949731.94     10096835.28      2949868.38     10096678.71
      2949976.29     10096347.91      2950196.16     10096189.45
      2950311.05     10096168.49      2950365.96     10096102.75
      2950407.13     10095964.31      2950401.20     10095834.91
      2950514.63     10095462.58      2950725.81     10095310.20
      2951090.44     10095158.58      2951195.50     10094888.37
      2951474.97     10094817.04      2951493.37     10094711.24
      2951346.79     10094560.33      2951298.85     10094459.29
      2951310.84     10094319.72      2951396.55     10094107.93
      2951396.64     10093899.50      2951263.27     10093746.73
      2951238.44     10093668.99      2951301.20     10093581.58
      2951328.11     10093458.87      2951410.73     10093411.18
      2951522.12     10093407.91      2951578.32     10093355.30

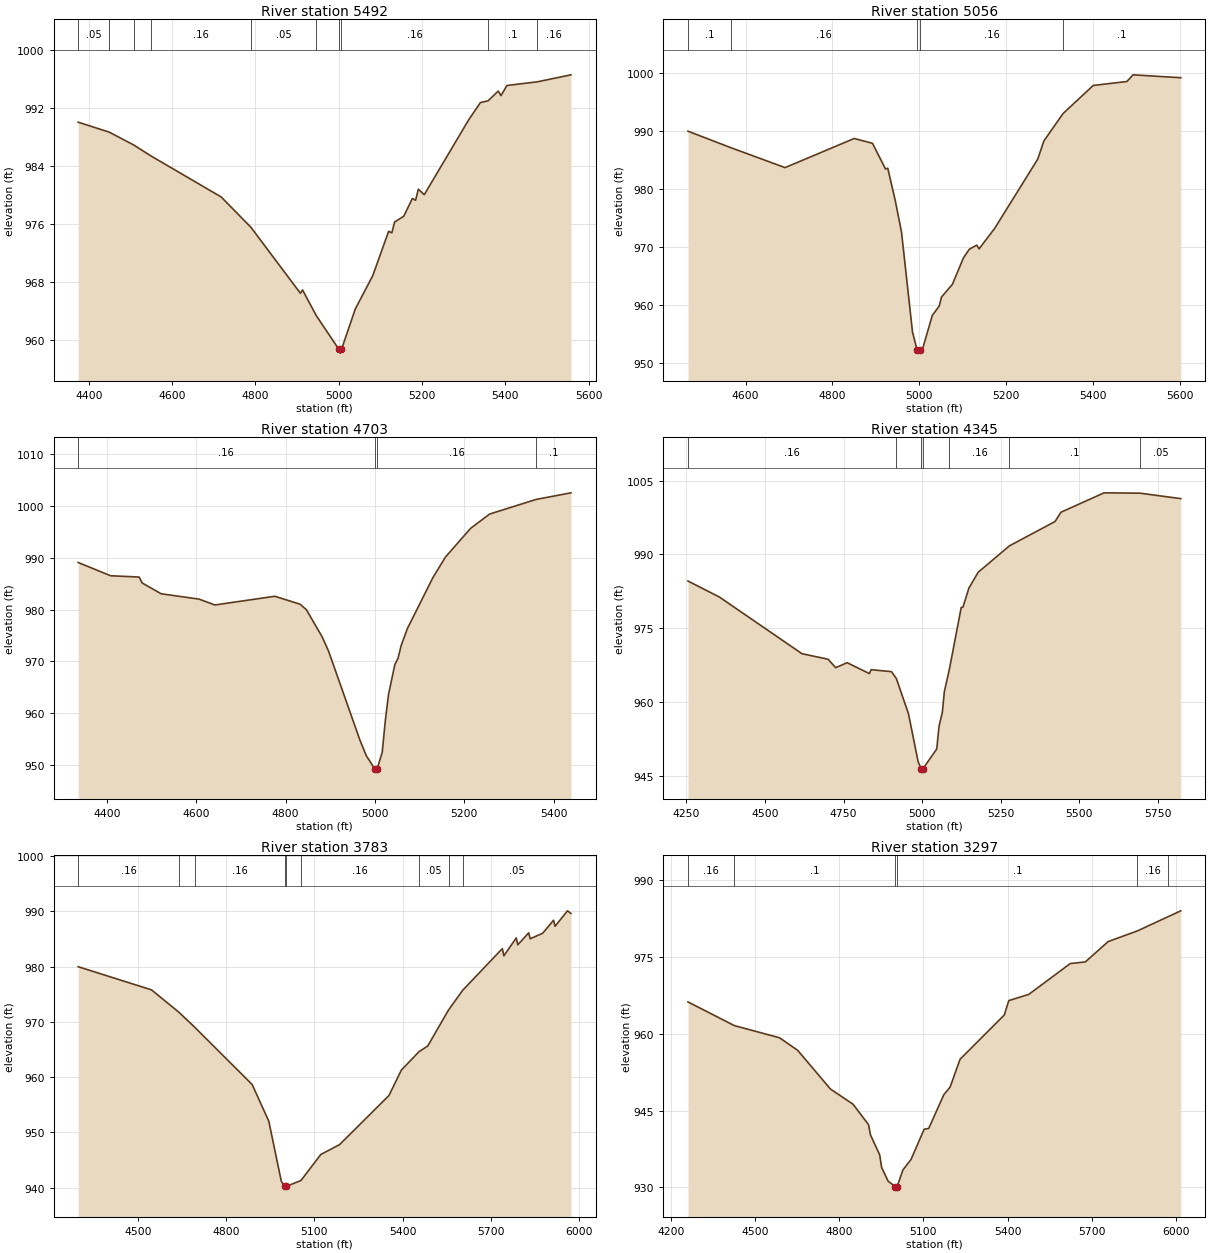
Type RM Length L Ch R = 1,5492,436,436,436
BEGIN DESCRIPTION:
UNT 1032 IN LATR 12.0
END DESCRIPTION:
XS GIS Cut Line= 3
      2949702.87     10097905.02      2949624.75     10097201.90
      2949312.87     10096842.37
#Sta/Elev= 30
  4374.4  990.05  4449.2  988.67  4508.6  986.88  4548.6  985.42  4717.8  979.75
  4789.7  975.54  4908.1  966.48  4913.2  966.94  4946.3  963.40  5000.7  958.74
  5003.5  958.24  5006.7  958.74  5039.8  964.31  5081.9  968.92  5120.0  975.02
  5127.7  974.81  5134.3  976.30  5156.2  977.09  5177.0  979.54  5184.7  979.30
  5191.3  980.82  5205.5  980.06  5311.9  990.35  5340.4  992.75  5358.7  992.99
  5383.2  994.33  5389.8  993.71  5404.0  995.10  5477.1  995.61  5557.8  996.57
#Mann=10,-1,0
  4374.4    0.05       0  4449.2    0.16       0  4508.6    0.05       0
  4548.6    0.16       0  4789.7    0.05       0  4946.3    0.16       0
  5000.7    0.07       0  5006.7    0.16       0  5358.7     0.1       0
  5477.1    0.16       0
Bank Sta=5000.7,5006.7
Exp/Cntr=0.3,0.1

Type RM Length L Ch R = 1,5056,353,353,353
BEGIN DESCRIPTION:
UNT 1032 IN LATR 11.0
END DESCRIPTION:
XS GIS Cut Line= 4
      2950236.69     10097314.72      2949854.78     10097058.67
      2949650.79     10097132.45      2949338.54     10096798.52
#Sta/Elev= 30
  4467.5  990.03  4565.4  987.20  4690.9  983.74  4850.0  988.77  4892.0  987.94
  4922.0  983.50  4927.2  983.63  4944.7  977.95  4958.8  972.62  4984.1  955.36
  4994.8  952.21  4997.6  951.71  5000.8  952.21  5008.5  952.75  5029.7  958.23
  5045.4  959.82  5051.0  961.41  5076.0  963.60  5101.4  968.17  5114.8  969.64
  5132.0  970.36  5137.3  969.71  5173.1  973.24  5272.3  985.21  5286.5  988.35
  5330.4  993.06  5399.8  997.92  5477.5  998.61  5491.6  999.76  5601.4  999.26
#Mann=5,-1,0
  4467.5     0.1       0  4565.4    0.16       0  4994.8    0.07       0
  5000.8    0.16       0  5330.4     0.1       0
Bank Sta=4994.8,5000.8
Exp/Cntr=0.3,0.1

Type RM Length L Ch R = 1,4703,358,358,358
BEGIN DESCRIPTION:
UNT 1032 IN LATR 10.0
END DESCRIPTION:
XS GIS Cut Line= 2
      2950262.77     10097232.28      2949482.48     10096451.99
#Sta/Elev= 30
  4335.4  989.10  4408.1  986.54  4471.8  986.29  4478.8  985.14  4521.3  983.06
  4606.1  982.03  4641.5  980.90  4775.8  982.58  4832.4  981.04  4846.5  979.98
  4881.9  974.72  4896.0  972.01  4966.7  954.72  4980.9  951.75  4999.1  949.32
  5001.8  948.82  5005.1  949.32  5016.2  952.43  5023.3  958.65  5030.4  963.64
  5044.5  969.38  5051.6  970.60  5058.7  973.08  5072.8  976.38  5129.4  986.12
  5157.7  990.14  5214.2  995.69  5256.7  998.45  5360.6 1001.27  5438.9 1002.55
#Mann=4,-1,0
  4335.4    0.16       0  4999.1    0.07       0  5005.1    0.16       0
  5360.6     0.1       0
Bank Sta=4999.1,5005.1
Exp/Cntr=0.3,0.1

Type RM Length L Ch R = 1,4345,562,562,562
BEGIN DESCRIPTION:
UNT 1032 IN LATR 9.0
END DESCRIPTION:
XS GIS Cut Line= 3
      2950280.12     10097062.98      2950050.09     10096494.43
      2949164.94     10096138.63
#Sta/Elev= 30
  4255.1  984.58  4354.8  981.33  4617.6  969.79  4700.7  968.66  4724.8  966.94
  4761.3  967.96  4832.1  965.74  4837.5  966.54  4902.5  966.13  4917.9  964.72
  4956.4  957.56  4987.1  947.80  4996.5  946.39  4999.3  945.89  5002.5  946.39
  5046.3  950.40  5053.4  954.97  5064.2  957.92  5070.5  962.08  5086.5  966.63
  5124.2  979.22  5129.6  979.25  5148.4  983.12  5178.0  986.36  5277.2  991.73
  5422.6  996.69  5441.4  998.58  5578.5 1002.53  5692.5 1002.46  5822.4 1001.35
#Mann=7,-1,0
  4255.1    0.16       0  4917.9     0.1       0  4996.5    0.07       0
  5002.5     0.1       0  5086.5    0.16       0  5277.2     0.1       0
  5692.5    0.05       0
Bank Sta=4996.5,5002.5
Exp/Cntr=0.3,0.1

Type RM Length L Ch R = 1,3783,486,486,486
BEGIN DESCRIPTION:
UNT 1032 IN LATR 8.0
END DESCRIPTION:
XS GIS Cut Line= 4
      2950670.75     10096741.83      2950445.06     10096220.99
      2950193.32     10095969.26      2949461.68     10095796.09
#Sta/Elev= 30
  4297.0  979.97  4546.4  975.78  4639.2  971.75  4692.8  969.05  4888.6  958.67
  4945.1  952.04  4987.6  941.19  4998.7  940.26  5001.5  939.76  5004.7  940.26
  5054.4  941.32  5121.9  946.02  5185.6  947.80  5353.6  956.68  5395.9  961.28
  5455.9  964.61  5485.6  965.64  5556.3  972.15  5604.4  975.71  5739.1  983.24
  5744.3  981.94  5786.5  985.17  5791.7  983.93  5828.8  986.09  5833.9  985.02
  5876.2  986.01  5913.3  988.37  5918.4  987.28  5960.7  990.07  5972.5  989.60
#Mann=9,-1,0
  4297.0    0.16       0  4639.2     0.1       0  4692.8    0.16       0
  4998.7    0.07       0  5004.7    0.16       0  5054.4    0.16       0
  5455.9    0.05       0  5556.3     0.1       0  5604.4    0.05       0
Bank Sta=4998.7,5004.7
Exp/Cntr=0.3,0.1

Type RM Length L Ch R = 1,3297,663,663,663
BEGIN DESCRIPTION:
UNT 1032 IN LATR 7.0
END DESCRIPTION:
XS GIS Cut Line= 4
      2950649.06     10096307.84      2950579.61     10095717.52
      2950171.62     10095539.57      2949542.88     10095197.01
#Sta/Elev= 30
  4261.6  966.23  4426.5  961.61  4587.9  959.22  4652.6  956.76  4769.2  949.20
  4849.7  946.24  4904.7  942.26  4911.8  940.24  4944.5  936.35  4951.5  933.88
  4974.9  931.17  5000.8  930.15  5003.5  929.65  5006.8  930.15  5027.2  933.40
  5056.1  935.44  5102.9  941.36  5119.1  941.50  5173.1  948.11  5195.4  949.59
  5230.9  955.03  5388.3  963.67  5404.4  966.49  5475.6  967.70  5623.5  973.73
  5676.9  974.04  5758.6  978.03  5862.4  980.10  5970.1  982.84  6017.1  984.03
#Mann=6,-1,0
  4261.6    0.16       0  4426.5     0.1       0  5000.8    0.07       0
  5006.8     0.1       0  5862.4    0.16       0  5970.1     0.1       0
Bank Sta=5000.8,5006.8
Exp/Cntr=0.3,0.1

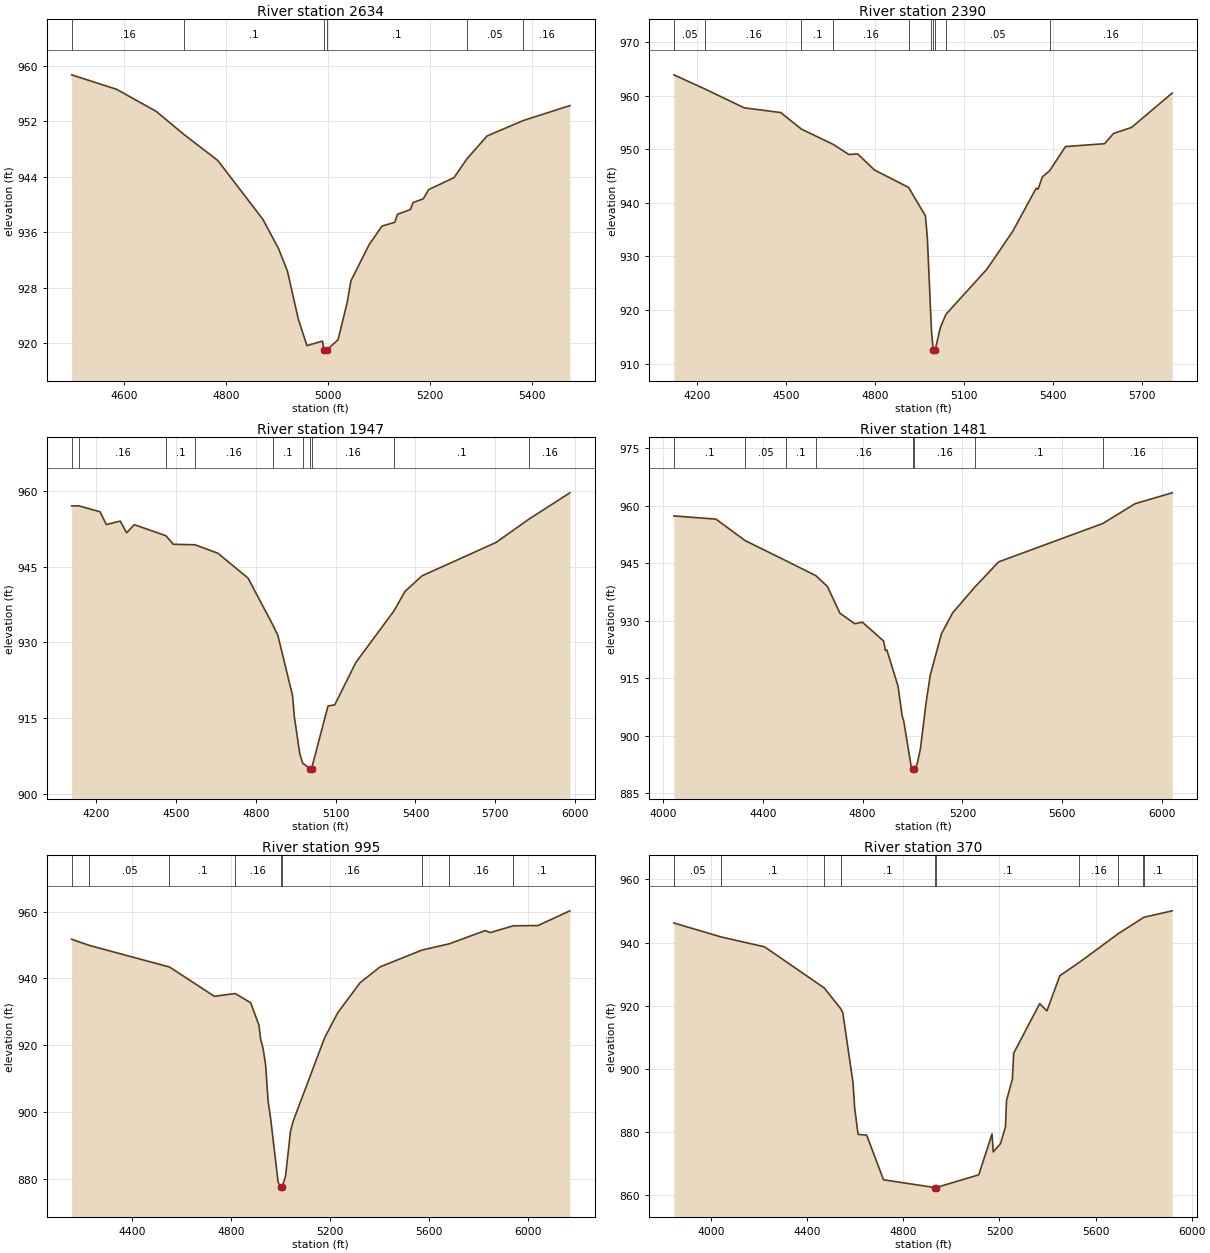
Type RM Length L Ch R = 1,2634,244,244,244
BEGIN DESCRIPTION:
UNT 1032 IN LATR 6.0
END DESCRIPTION:
XS GIS Cut Line= 4
      2951208.95     10095617.70      2950957.21     10095396.34
      2950813.98     10095005.71      2950615.74     10094897.97
#Sta/Elev= 30
  4497.4  958.68  4585.6  956.60  4663.5  953.41  4717.0  950.13  4784.0  946.35
  4872.6  937.85  4903.1  933.66  4920.6  930.42  4941.9  923.49  4958.8  919.68
  4989.3  920.33  4992.2  919.10  4994.9  918.60  4998.2  919.10  5019.8  920.52
  5037.8  925.92  5045.0  929.00  5080.8  934.23  5106.0  936.90  5131.1  937.44
  5136.5  938.60  5161.6  939.28  5167.0  940.29  5186.8  940.82  5197.5  942.15
  5247.1  943.87  5272.5  946.58  5311.9  949.87  5382.3  952.08  5474.3  954.25
#Mann=6,-1,0
  4497.4    0.16       0  4717.0     0.1       0  4992.2    0.07       0
  4998.2     0.1       0  5272.5    0.05       0  5382.3    0.16       0
Bank Sta=4992.2,4998.2
Exp/Cntr=0.3,0.1

Type RM Length L Ch R = 1,2390,443,443,443
BEGIN DESCRIPTION:
UNT 1032 IN LATR 5.0
END DESCRIPTION:
XS GIS Cut Line= 4
      2951569.19     10095843.40      2951347.84     10095300.85
      2950701.13     10094840.78      2950402.57     10094797.51
#Sta/Elev= 30
  4121.9  963.90  4228.1  961.22  4359.1  957.74  4482.3  956.86  4552.3  953.76
  4660.4  950.89  4712.4  949.02  4741.9  949.14  4798.5  946.14  4914.1  942.87
  4970.6  937.56  4977.1  933.51  4989.4  918.16  4991.5  915.72  4997.1  912.44
  4999.9  911.94  5003.1  912.44  5021.0  916.72  5040.1  919.20  5178.4  927.64
  5264.5  934.61  5344.5  942.74  5350.6  942.55  5365.4  944.86  5389.5  945.98
  5443.4  950.51  5574.9  951.04  5605.3  952.95  5665.9  954.07  5803.2  960.49
#Mann=10,-1,0
  4121.9    0.05       0  4228.1    0.16       0  4552.3     0.1       0
  4660.4    0.16       0  4914.1    0.05       0  4989.4     0.1       0
  4997.1    0.07       0  5003.1     0.1       0  5040.1    0.05       0
  5389.5    0.16       0
Bank Sta=4997.1,5003.1
Exp/Cntr=0.3,0.1

Type RM Length L Ch R = 1,1947,466,466,466
BEGIN DESCRIPTION:
UNT 1032 IN LATR 4.0
END DESCRIPTION:
XS GIS Cut Line= 4
      2951695.06     10095678.45      2951404.26     10095001.37
      2951347.84     10094758.32      2950518.88     10094445.83
#Sta/Elev= 30
  4107.9  957.02  4135.3  957.03  4214.9  955.86  4238.4  953.33  4291.0  954.02
  4314.5  951.70  4343.5  953.31  4462.3  951.12  4490.3  949.43  4571.3  949.33
  4657.2  947.67  4771.1  942.73  4864.7  933.41  4883.4  931.33  4938.3  919.45
  4945.0  915.28  4965.6  907.91  4976.6  906.10  5003.6  905.04  5006.4  904.54
  5009.6  905.04  5071.4  917.43  5096.6  917.65  5176.0  926.04  5319.8  936.29
  5360.8  940.11  5424.9  943.19  5702.8  949.79  5827.4  954.44  5980.2  959.61
#Mann=10,-1,0
  4107.9    0.05       0  4135.3    0.16       0  4462.3     0.1       0
  4571.3    0.16       0  4864.7     0.1       0  4976.6    0.16       0
  5003.6    0.07       0  5009.6    0.16       0  5319.8     0.1       0
  5827.4    0.16       0
Bank Sta=5003.6,5009.6
Exp/Cntr=0.3,0.1

Type RM Length L Ch R = 1,1481,486,486,486
BEGIN DESCRIPTION:
UNT 1032 IN LATR 3.0
END DESCRIPTION:
XS GIS Cut Line= 4
      2952272.29     10094406.76      2951482.38     10094463.18
      2951156.86     10094623.77      2950372.36     10094316.04
#Sta/Elev= 30
  4043.3  957.36  4212.0  956.52  4329.1  950.92  4493.1  945.66  4612.6  941.77
  4658.7  938.97  4708.8  932.00  4768.4  929.25  4799.0  929.65  4884.2  924.74
  4891.4  922.26  4896.9  922.44  4941.8  913.00  4958.7  905.10  4964.3  904.05
  4995.7  891.57  5000.6  891.31  5003.4  890.81  5006.6  891.31  5018.0  892.56
  5031.7  896.64  5054.1  908.52  5071.0  915.78  5115.9  926.62  5160.8  932.08
  5249.3  938.77  5345.2  945.38  5762.7  955.38  5893.0  960.57  6040.9  963.38
#Mann=8,-1,0
  4043.3     0.1       0  4329.1    0.05       0  4493.1     0.1       0
  4612.6    0.16       0  5000.6    0.07       0  5006.6    0.16       0
  5249.3     0.1       0  5762.7    0.16       0
Bank Sta=5000.6,5006.6
Exp/Cntr=0.3,0.1

Type RM Length L Ch R = 1,995,625,625,625
BEGIN DESCRIPTION:
UNT 1032 IN LATR 2.0
END DESCRIPTION:
XS GIS Cut Line= 4
      2952207.23     10094298.26      2951729.78     10094115.96
      2950683.77     10093998.77      2950242.30     10094085.33
#Sta/Elev= 30
  4154.7  951.76  4226.6  949.89  4550.3  943.42  4731.6  934.65  4815.9  935.47
  4878.4  932.71  4912.0  925.94  4918.7  921.75  4928.7  918.93  4938.8  914.00
  4948.8  903.22  4958.9  898.10  4989.1  878.98  4999.2  877.32  5001.9  876.82
  5005.2  877.32  5019.3  880.70  5039.4  894.20  5049.5  897.09  5177.5  922.26
  5230.6  929.74  5321.2  938.77  5401.7  943.48  5571.2  948.51  5680.7  950.38
  5826.4  954.35  5846.0  953.75  5939.5  955.78  6039.6  955.86  6168.2  960.27
#Mann=9,-1,0
  4154.7     0.1       0  4226.6    0.05       0  4550.3     0.1       0
  4815.9    0.16       0  4999.2    0.07       0  5005.2    0.16       0
  5571.2     0.1       0  5680.7    0.16       0  5939.5     0.1       0
Bank Sta=4999.2,5005.2
Exp/Cntr=0.3,0.1

Type RM Length L Ch R = 1,370,0,0,0
BEGIN DESCRIPTION:
UNT 1032 IN LATR 1.0
END DESCRIPTION:
XS GIS Cut Line= 4
      2952220.24     10094185.41      2951530.13     10093551.72
      2951091.76     10093525.68      2950442.07     10093781.22
#Sta/Elev= 30
  3844.7  946.21  4041.3  941.78  4222.3  938.65  4470.6  925.64  4539.2  919.08
  4547.9  917.78  4590.4  895.63  4597.2  887.67  4611.4  879.31  4647.1  879.06
  4717.4  864.94  4930.5  862.48  4933.3  861.98  4936.5  862.48  5113.9  866.51
  5169.1  879.46  5174.1  873.76  5204.0  876.34  5224.9  881.67  5229.4  890.05
  5253.8  896.81  5259.2  905.02  5367.5  920.68  5397.3  918.38  5451.5  929.54
  5531.2  933.68  5694.7  942.83  5798.3  947.86  5802.5  948.03  5918.9  950.05
#Mann=10,-1,0
  3844.7    0.05       0  4041.3     0.1       0  4470.6    0.16       0
  4539.2     0.1       0  4930.5    0.07       0  4936.5     0.1       0
  5531.2    0.16       0  5694.7     0.1       0  5798.3    0.16       0
  5802.5     0.1       0
Bank Sta=4930.5,4936.5
Exp/Cntr=0.3,0.1

Chan Stop Cuts=-1