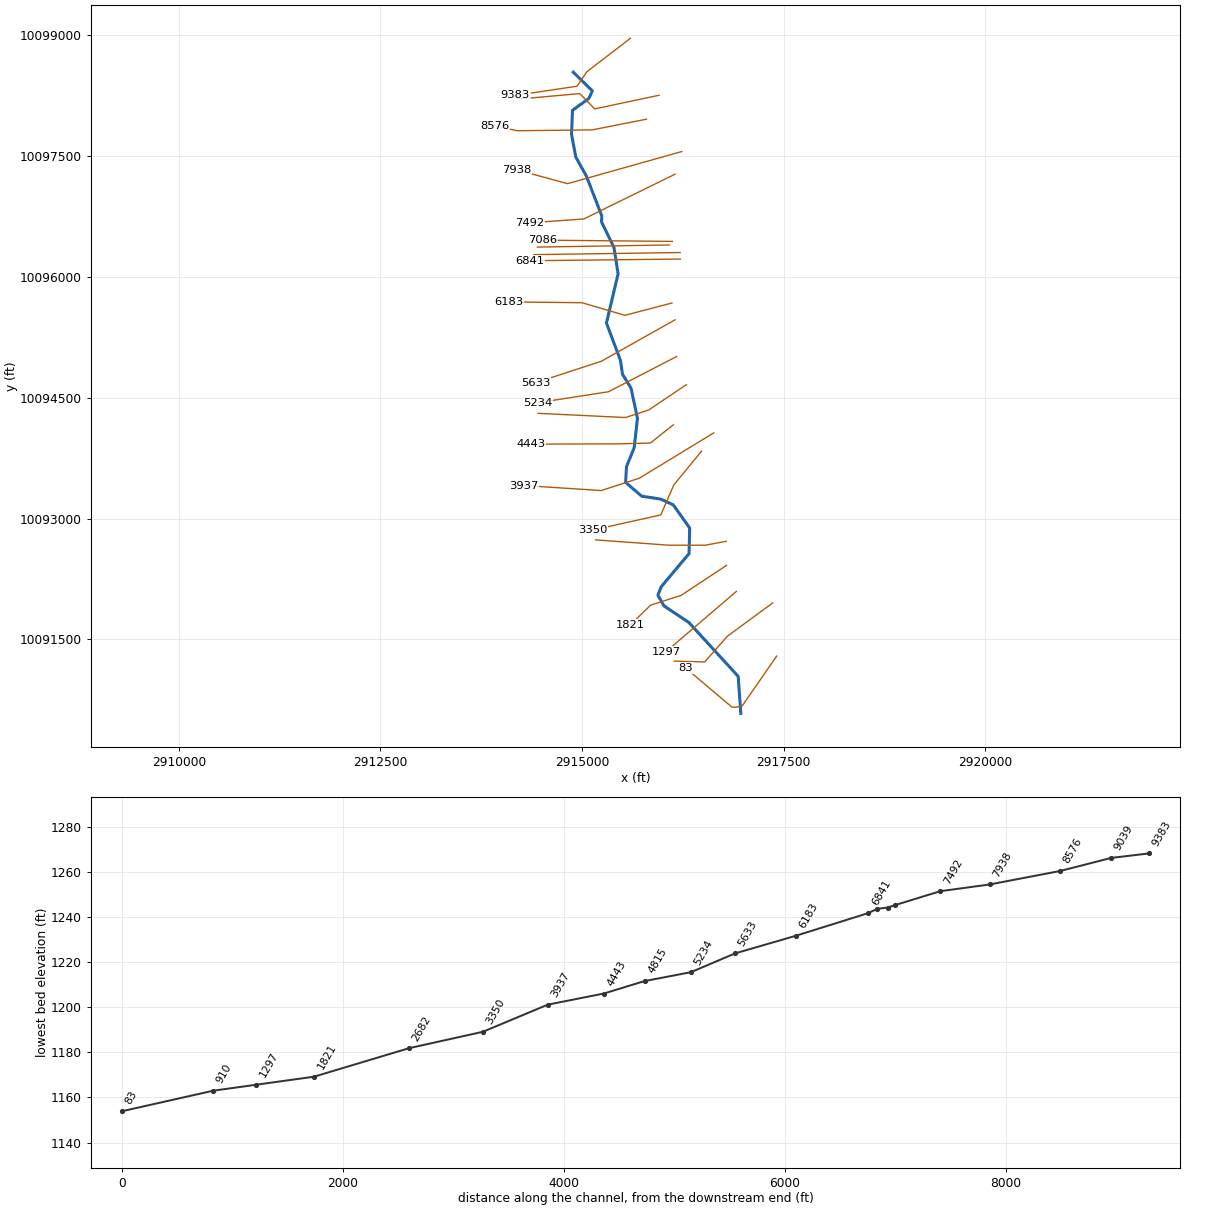
--- UNT 0034 IN LATR.prj (project) ---

Proj Title=UNT 1034 IN LATR Base Level Engineering
Current Plan=p01
Default Exp/Contr=0.3,0.1
English Units
Geom File=g01
Flow File=f01
Plan File=p01
BEGIN DESCRIPTION:
UNT 1034 IN LATR
END DESCRIPTION:

--- UNT 0034 IN LATR.p01 (plan) ---

Plan Title=Multiple Run
Short Identifier=Multiple
Geom File=g01
Flow File=f01
Subcritical Flow
K Sum by GR= 0
Std Step Tol= 0.01
Critical Tol= 0.01
Num of Std Step Trials= 20
Max Error Tol= 0.3
Flow Tol Ratio= 0.001
Split Flow NTrial= 30
Split Flow Tol= 0.02
Split Flow Ratio= 0.02
Log Output Level= 0
Friction Slope Method= 1
Unsteady Friction Slope Method= 2
Unsteady Bridges Friction Slope Method= 1
Parabolic Critical Depth
Global Vel Dist=  1 , 1 , 1
Global Log Level= 0
CheckData=True
Encroach Param= -1, 0, 0, 0
BEGIN DESCRIPTION:
Multiple Run
END DESCRIPTION:

--- UNT 0034 IN LATR.f01 (steady flow) ---

Flow Title=Multiple
Number of Profiles=7
Profile Names=10-year,25-year,50-year,1pct_min,100-year,1pct_plu,500-year
River Rch & RM= UNT 1034 IN LATR,Reach-1,9383
     790    1140    1443    1338    1809    2446    2853
River Rch & RM= UNT 1034 IN LATR,Reach-1,8576
    1189    1746    2235    2092    2830    3827    4554
Boundary for River Rch & Prof#=UNT 1034 IN LATR,Reach-1,1
Up Type=0
Dn Type=3
Dn Slope=0.005
Boundary for River Rch & Prof#=UNT 1034 IN LATR,Reach-1,2
Up Type=0
Dn Type=3
Dn Slope=0.005
Boundary for River Rch & Prof#=UNT 1034 IN LATR,Reach-1,3
Up Type=0
Dn Type=3
Dn Slope=0.005
Boundary for River Rch & Prof#=UNT 1034 IN LATR,Reach-1,4
Up Type=0
Dn Type=3
Dn Slope=0.005
Boundary for River Rch & Prof#=UNT 1034 IN LATR,Reach-1,5
Up Type=0
Dn Type=3
Dn Slope=0.005
Boundary for River Rch & Prof#=UNT 1034 IN LATR,Reach-1,6
Up Type=0
Dn Type=3
Dn Slope=0.005
Boundary for River Rch & Prof#=UNT 1034 IN LATR,Reach-1,7
Up Type=0
Dn Type=3
Dn Slope=0.005

--- UNT 0034 IN LATR.g01 (geometry) ---

Geom Title=Existing Conditions

River Reach=UNT 1034 IN LATR,Reach-1
Reach XY= 30
      2914891.20     10098534.82      2915127.86     10098303.12
      2915083.66     10098208.21      2914881.43     10098062.68
      2914869.65     10097764.24      2914923.00     10097480.90
      2915053.91     10097246.53      2915244.81     10096752.14
      2915242.32     10096675.28      2915395.80     10096362.60
      2915446.82     10096034.14      2915302.60     10095424.39
      2915475.73     10094962.60      2915500.99     10094789.60
      2915606.86     10094618.07      2915687.00     10094243.35
      2915646.58     10093879.33      2915551.21     10093642.59
      2915540.05     10093449.10      2915739.88     10093276.73
      2915977.23     10093240.74      2916130.93     10093169.47
      2916334.87     10092882.32      2916326.80     10092564.43
      2915983.58     10092156.58      2915940.67     10092049.66
      2916015.17     10091917.25      2916325.06     10091710.33
      2916936.05     10091042.81      2916968.47     10090583.73

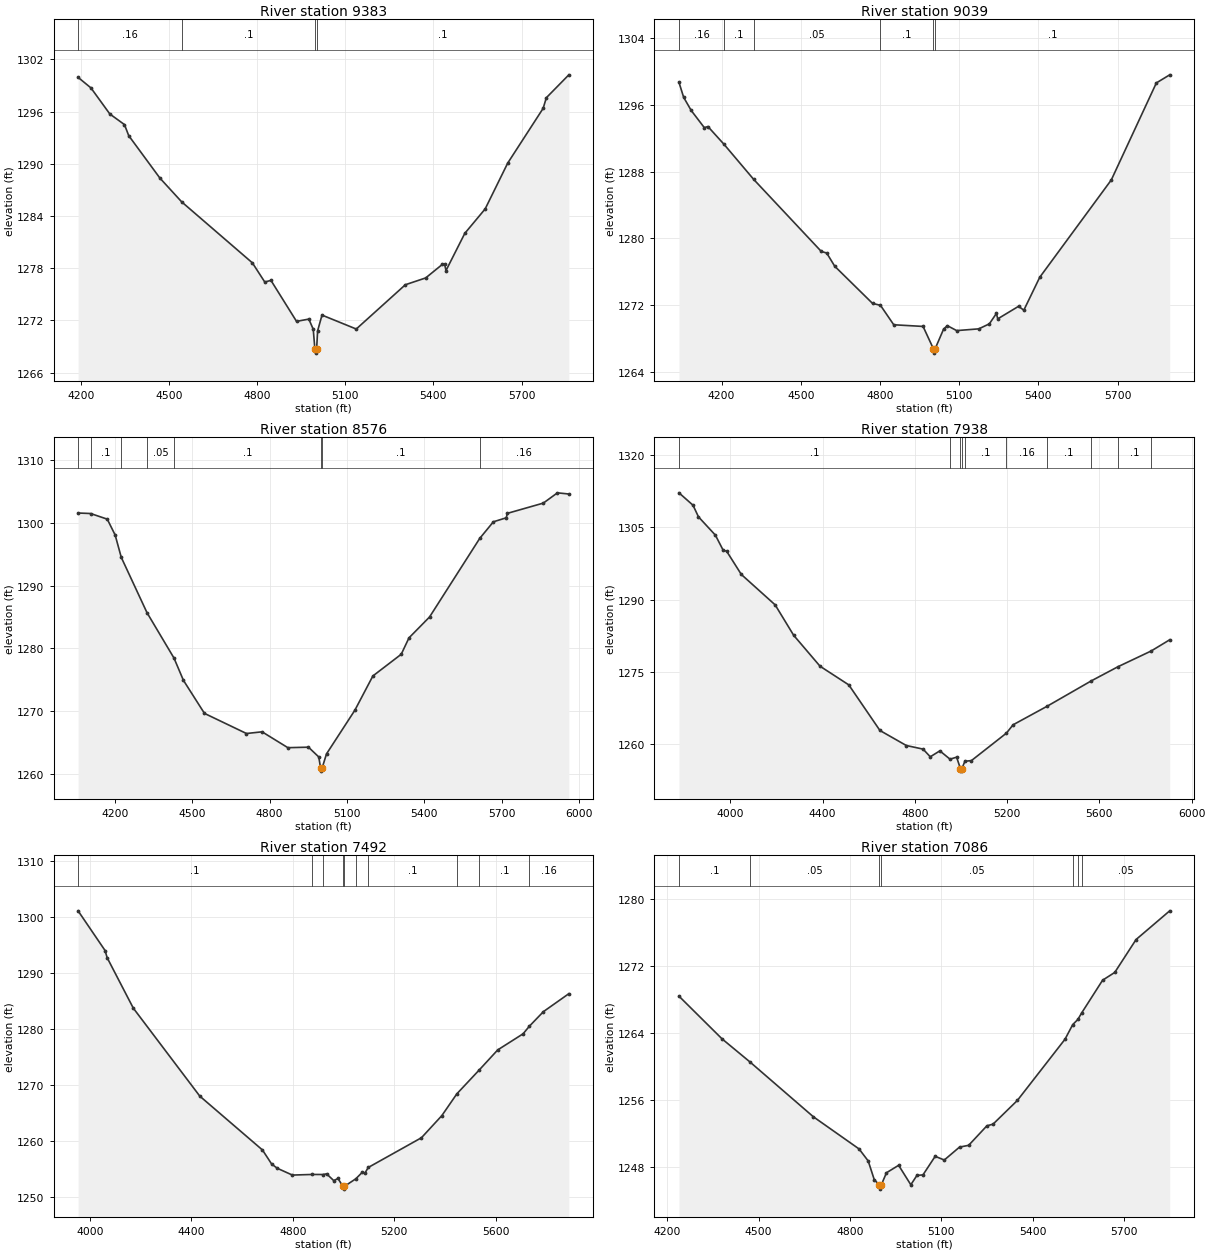
Type RM Length L Ch R = 1,9383,344,344,344
BEGIN DESCRIPTION:
UNT 1034 IN LATR 20.0
END DESCRIPTION:
XS GIS Cut Line= 4
      2915599.09     10098954.62      2915060.07     10098540.59
      2914937.67     10098360.90      2914172.79     10098246.43
#Sta/Elev= 30
  4190.6 1299.94  4234.3 1298.73  4298.7 1295.73  4348.5 1294.51  4363.0 1293.24
  4469.0 1288.37  4543.3 1285.63  4784.0 1278.62  4826.1 1276.42  4847.1 1276.61
  4934.2 1271.90  4976.1 1272.16  4991.1 1270.99  4996.6 1268.75  4999.3 1268.25
  5002.6 1268.75  5006.0 1270.81  5020.9 1272.62  5137.5 1271.02  5304.7 1276.11
  5373.8 1276.89  5430.7 1278.45  5438.0 1278.50  5443.0 1277.74  5507.1 1282.02
  5576.3 1284.82  5653.1 1290.09  5773.7 1296.38  5784.6 1297.60  5861.1 1300.23
#Mann=4,-1,0
  4190.6    0.16       0  4543.3     0.1       0  4996.6    0.07       0
  5002.6     0.1       0
Bank Sta=4996.6,5002.6
Exp/Cntr=0.3,0.1

Type RM Length L Ch R = 1,9039,463,463,463
BEGIN DESCRIPTION:
UNT 1034 IN LATR 19.0
END DESCRIPTION:
XS GIS Cut Line= 4
      2915955.88     10098248.92      2915156.42     10098079.65
      2914971.53     10098269.76      2914198.09     10098199.45
#Sta/Elev= 30
  4038.6 1298.71  4056.4 1296.91  4084.9 1295.34  4134.6 1293.28  4148.4 1293.41
  4209.6 1291.27  4321.8 1287.07  4577.7 1278.44  4598.2 1278.25  4628.8 1276.66
  4771.9 1272.21  4801.9 1271.98  4852.2 1269.65  4963.3 1269.45  5002.7 1266.75
  5005.4 1266.25  5008.7 1266.75  5041.2 1269.14  5055.3 1269.54  5090.6 1268.95
  5174.3 1269.16  5214.4 1269.76  5241.1 1271.01  5246.2 1270.36  5324.9 1271.86
  5345.0 1271.40  5405.2 1275.34  5676.3 1287.01  5847.0 1298.64  5897.6 1299.61
#Mann=6,-1,0
  4038.6    0.16       0  4209.6     0.1       0  4321.8    0.05       0
  4801.9     0.1       0  5002.7    0.07       0  5008.7     0.1       0
Bank Sta=5002.7,5008.7
Exp/Cntr=0.3,0.1

Type RM Length L Ch R = 1,8576,638,638,638
BEGIN DESCRIPTION:
UNT 1034 IN LATR 18.0
END DESCRIPTION:
XS GIS Cut Line= 4
      2915799.68     10097952.05      2915125.17     10097819.24
      2914198.09     10097808.82      2913914.24     10097868.71
#Sta/Elev= 30
  4056.6 1301.61  4105.2 1301.53  4169.9 1300.63  4200.5 1298.10  4224.3 1294.53
  4324.1 1285.71  4428.9 1278.47  4465.5 1274.92  4547.1 1269.65  4710.1 1266.44
  4770.8 1266.71  4870.8 1264.18  4950.8 1264.26  4990.8 1262.70  4997.8 1260.94
  5000.5 1260.44  5003.8 1260.94  5020.8 1263.19  5130.8 1270.15  5200.8 1275.62
  5310.8 1279.08  5340.8 1281.69  5420.8 1285.03  5615.3 1297.55  5668.5 1300.21
  5718.0 1300.84  5723.1 1301.56  5862.2 1303.19  5917.1 1304.83  5961.3 1304.64
#Mann=8,-1,0
  4056.6    0.16       0  4105.2     0.1       0  4224.3    0.16       0
  4324.1    0.05       0  4428.9     0.1       0  4997.8    0.07       0
  5003.8     0.1       0  5615.3    0.16       0
Bank Sta=4997.8,5003.8
Exp/Cntr=0.3,0.1

Type RM Length L Ch R = 1,7938,446,446,446
BEGIN DESCRIPTION:
UNT 1034 IN LATR 17.0
END DESCRIPTION:
XS GIS Cut Line= 3
      2916237.13     10097551.00      2914820.48     10097152.57
      2914187.71     10097324.43
#Sta/Elev= 30
  3777.6 1312.14  3838.5 1309.57  3862.2 1307.16  3935.5 1303.37  3969.5 1300.22
  3984.0 1300.06  4048.0 1295.22  4194.6 1288.92  4274.8 1282.62  4389.1 1276.21
  4513.8 1272.34  4648.8 1262.89  4763.1 1259.78  4835.8 1259.03  4866.9 1257.44
  4908.5 1258.67  4952.5 1256.95  4981.2 1257.36  4997.8 1254.97  5000.6 1254.47
  5003.8 1254.97  5017.1 1256.52  5045.3 1256.65  5197.0 1262.34  5225.9 1264.07
  5373.3 1267.91  5565.2 1273.18  5681.2 1276.12  5824.7 1279.37  5904.9 1281.69
#Mann=10,-1,0
  3777.6     0.1       0  4952.5    0.16       0  4997.8    0.07       0
  5003.8    0.16       0  5017.1     0.1       0  5197.0    0.16       0
  5373.3     0.1       0  5565.2    0.16       0  5681.2     0.1       0
  5824.7    0.05       0
Bank Sta=4997.8,5003.8
Exp/Cntr=0.3,0.1

Type RM Length L Ch R = 1,7492,406,406,406
BEGIN DESCRIPTION:
Mapping XS 2e073e5c
END DESCRIPTION:
XS GIS Cut Line= 3
      2916154.11     10097270.48      2915022.13     10096714.91
      2914348.55     10096666.30
#Sta/Elev= 30
  3952.5 1301.19  4059.0 1294.10  4067.3 1292.81  4170.4 1283.81  4432.7 1268.10
  4680.0 1258.48  4716.3 1255.97  4738.6 1255.21  4798.0 1254.00  4876.3 1254.11
  4919.2 1254.10  4933.0 1254.22  4961.3 1253.01  4977.9 1253.39  4997.4 1251.99
  5000.2 1251.49  5003.4 1251.99  5048.2 1253.33  5073.5 1254.48  5083.9 1254.33
  5097.5 1255.36  5307.4 1260.67  5387.6 1264.61  5447.2 1268.52  5535.7 1272.79
  5608.2 1276.35  5708.4 1279.23  5733.0 1280.58  5788.6 1283.19  5888.8 1286.39
#Mann=10,-1,0
  3952.5     0.1       0  4876.3    0.16       0  4919.2     0.1       0
  4997.4    0.07       0  5003.4     0.1       0  5048.2    0.16       0
  5097.5     0.1       0  5447.2    0.16       0  5535.7     0.1       0
  5733.0    0.16       0
Bank Sta=4997.4,5003.4
Exp/Cntr=0.3,0.1

Type RM Length L Ch R = 1,7086,71,71,71
BEGIN DESCRIPTION:
UNT 1034 IN LATR 16.0
END DESCRIPTION:
XS GIS Cut Line= 2
      2916120.00     10096436.42      2914507.98     10096452.05
#Sta/Elev= 30
  4238.4 1268.38  4379.9 1263.29  4470.9 1260.56  4680.0 1254.00  4830.0 1250.17
  4860.0 1248.74  4880.0 1246.50  4897.0 1245.88  4899.7 1245.38  4903.0 1245.88
  4920.0 1247.33  4960.0 1248.22  5000.0 1245.90  5020.0 1247.01  5040.0 1247.08
  5080.0 1249.29  5110.0 1248.85  5160.0 1250.39  5190.0 1250.60  5250.0 1252.93
  5270.0 1253.12  5350.0 1255.95  5506.6 1263.25  5531.9 1264.99  5548.7 1265.60
  5560.9 1266.36  5630.0 1270.28  5670.0 1271.21  5740.0 1275.13  5850.5 1278.55
#Mann=7,-1,0
  4238.4     0.1       0  4470.9    0.05       0  4897.0    0.04       0
  4903.0    0.05       0  5531.9    0.16       0  5548.7     0.1       0
  5560.9    0.05       0
Bank Sta=4897,4903
Exp/Cntr=0.3,0.1

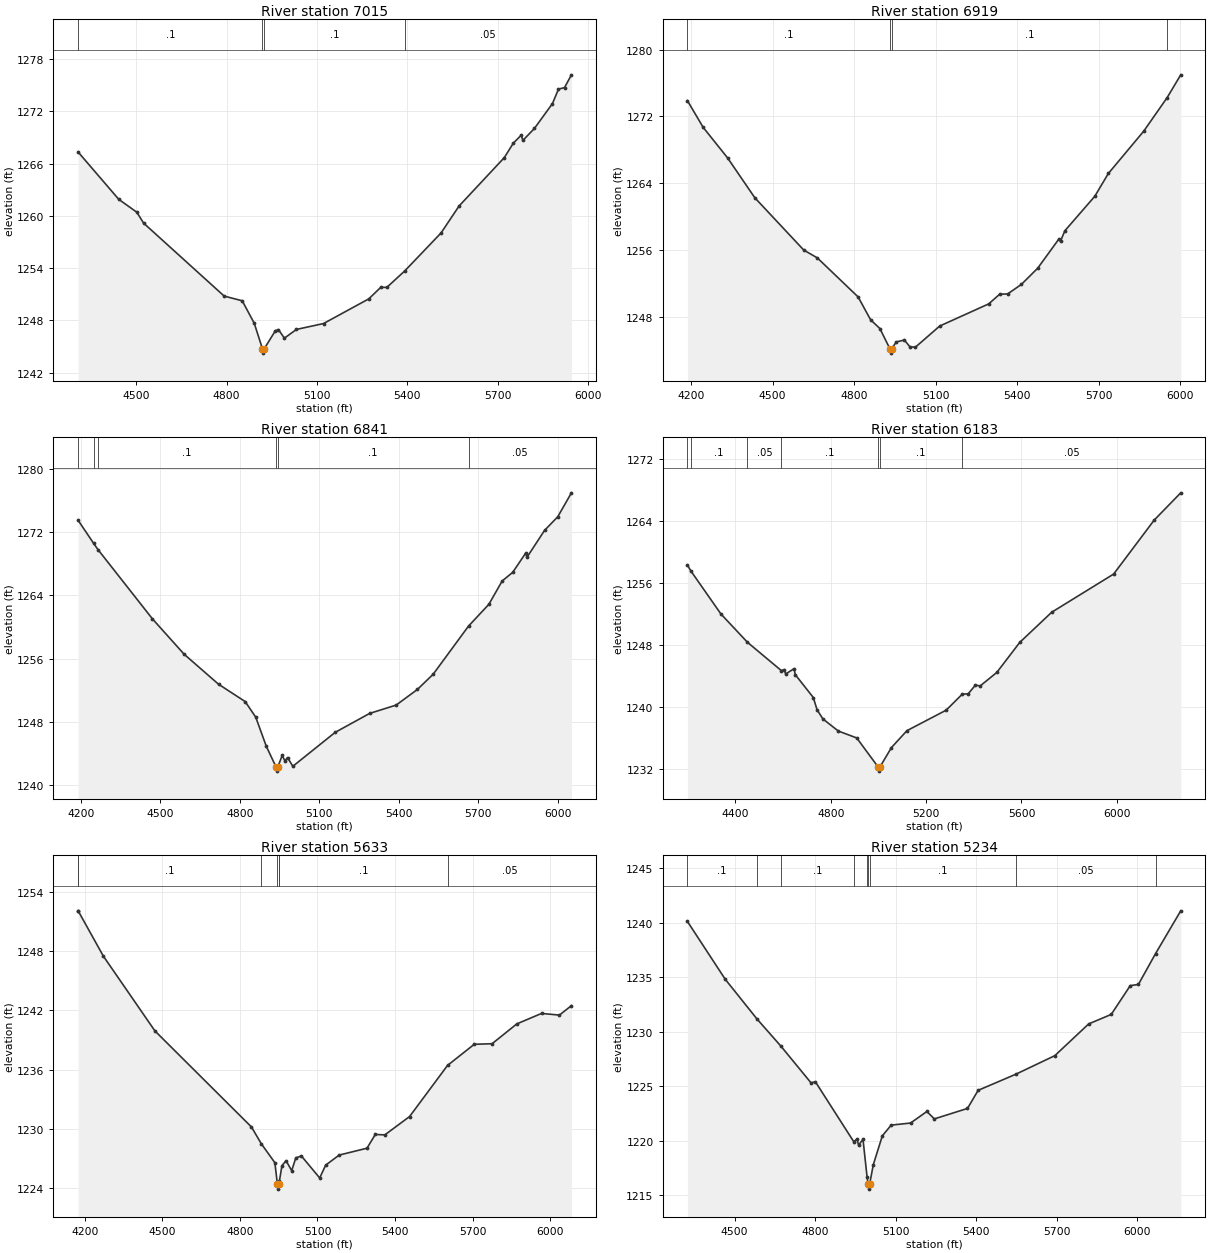
Type RM Length L Ch R = 1,7015,96,96,96
BEGIN DESCRIPTION:
UNT 1034 IN LATR 15.0
END DESCRIPTION:
XS GIS Cut Line= 2
      2916083.50     10096392.15      2914445.51     10096366.11
#Sta/Elev= 30
  4306.7 1267.35  4441.8 1261.91  4501.8 1260.43  4524.3 1259.18  4791.8 1250.80
  4851.8 1250.26  4891.8 1247.67  4918.8 1244.75  4921.6 1244.25  4924.8 1244.75
  4961.8 1246.82  4971.8 1246.96  4991.8 1245.97  5031.8 1246.97  5121.8 1247.65
  5271.9 1250.48  5311.9 1251.81  5331.9 1251.80  5391.1 1253.68  5511.9 1258.05
  5571.9 1261.15  5721.9 1266.70  5751.9 1268.36  5778.5 1269.29  5783.5 1268.67
  5821.9 1270.05  5881.9 1272.91  5901.9 1274.57  5921.9 1274.74  5944.9 1276.21
#Mann=4,-1,0
  4306.7     0.1       0  4918.8    0.07       0  4924.8     0.1       0
  5391.1    0.05       0
Bank Sta=4918.8,4924.8
Exp/Cntr=0.3,0.1

Type RM Length L Ch R = 1,6919,78,78,78
BEGIN DESCRIPTION:
UNT 1034 IN LATR 13.0
END DESCRIPTION:
XS GIS Cut Line= 2
      2916216.35     10096298.40      2914402.33     10096272.38
#Sta/Elev= 30
  4187.0 1273.88  4244.9 1270.68  4334.9 1267.01  4434.9 1262.24  4614.9 1255.97
  4664.9 1255.03  4814.9 1250.35  4860.6 1247.62  4895.0 1246.56  4932.0 1244.12
  4934.7 1243.62  4938.0 1244.12  4955.0 1244.96  4985.0 1245.19  5005.0 1244.39
  5025.0 1244.32  5115.0 1246.87  5295.0 1249.52  5335.0 1250.67  5365.0 1250.72
  5415.0 1251.85  5475.0 1253.79  5554.1 1257.34  5559.1 1257.04  5575.0 1258.28
  5685.0 1262.41  5735.0 1265.15  5865.1 1270.22  5951.0 1274.23  6001.2 1276.97
#Mann=4,-1,0
  4187.0     0.1       0  4932.0    0.07       0  4938.0     0.1       0
  5951.0    0.05       0
Bank Sta=4932,4938
Exp/Cntr=0.3,0.1

Type RM Length L Ch R = 1,6841,658,658,658
BEGIN DESCRIPTION:
UNT 1034 IN LATR 14.0
END DESCRIPTION:
XS GIS Cut Line= 2
      2916218.88     10096217.67      2914356.90     10096196.84
#Sta/Elev= 30
  4190.0 1273.48  4248.6 1270.56  4265.1 1269.77  4470.4 1261.03  4590.4 1256.55
  4720.4 1252.76  4820.5 1250.58  4860.5 1248.61  4900.5 1244.92  4937.5 1242.29
  4940.2 1241.79  4943.5 1242.29  4960.5 1243.78  4970.5 1243.09  4980.5 1243.51
  5000.5 1242.40  5160.5 1246.69  5290.5 1249.08  5390.5 1250.13  5470.5 1252.10
  5530.5 1254.04  5663.7 1260.11  5740.5 1262.86  5790.5 1265.80  5830.5 1266.90
  5879.3 1269.32  5884.3 1268.80  5950.5 1272.19  6000.5 1273.92  6052.1 1276.94
#Mann=6,-1,0
  4190.0     0.1       0  4248.6    0.05       0  4265.1     0.1       0
  4937.5    0.07       0  4943.5     0.1       0  5663.7    0.05       0
Bank Sta=4937.5,4943.5
Exp/Cntr=0.3,0.1

Type RM Length L Ch R = 1,6183,550,550,550
BEGIN DESCRIPTION:
UNT 1034 IN LATR 12.0
END DESCRIPTION:
XS GIS Cut Line= 4
      2916114.73     10095672.53      2915531.42     10095519.76
      2915000.17     10095676.01      2914086.96     10095686.42
#Sta/Elev= 30
  4198.3 1258.31  4211.9 1257.57  4339.2 1251.97  4450.1 1248.33  4592.5 1244.67
  4605.4 1244.80  4610.5 1244.23  4645.8 1244.92  4650.9 1244.15  4726.6 1241.20
  4742.3 1239.62  4767.0 1238.43  4831.8 1236.87  4908.9 1235.98  4999.4 1232.20
  5002.2 1231.70  5005.4 1232.20  5054.5 1234.74  5119.4 1236.92  5283.8 1239.56
  5351.6 1241.63  5376.7 1241.68  5406.7 1242.80  5426.7 1242.69  5496.7 1244.44
  5592.8 1248.31  5726.8 1252.20  5986.8 1257.13  6156.8 1264.09  6268.3 1267.61
#Mann=7,-1,0
  4198.3    0.05       0  4211.9     0.1       0  4450.1    0.05       0
  4592.5     0.1       0  4999.4    0.07       0  5005.4     0.1       0
  5351.6    0.05       0
Bank Sta=4999.4,5005.4
Exp/Cntr=0.3,0.1

Type RM Length L Ch R = 1,5633,399,399,399
BEGIN DESCRIPTION:
UNT 1034 IN LATR 11.0
END DESCRIPTION:
XS GIS Cut Line= 3
      2916152.91     10095464.18      2915239.76     10094950.31
      2914421.90     10094683.47
#Sta/Elev= 30
  4174.1 1252.09  4174.3 1252.09  4271.8 1247.50  4471.2 1239.92  4844.7 1230.18
  4882.7 1228.48  4935.2 1226.56  4945.0 1224.38  4947.7 1223.88  4951.0 1224.38
  4952.6 1224.68  4962.6 1226.26  4978.6 1226.76  5000.2 1225.75  5016.2 1227.05
  5037.8 1227.24  5108.6 1225.01  5131.6 1226.31  5183.8 1227.33  5291.6 1228.03
  5323.5 1229.42  5360.6 1229.38  5456.3 1231.24  5603.0 1236.42  5706.2 1238.56
  5775.3 1238.62  5871.0 1240.63  5966.7 1241.69  6035.7 1241.52  6082.2 1242.48
#Mann=7,-1,0
  4174.1    0.05       0  4174.3     0.1       0  4882.7    0.16       0
  4945.0    0.07       0  4951.0    0.16       0  4952.6     0.1       0
  5603.0    0.05       0
Bank Sta=4945,4951
Exp/Cntr=0.3,0.1

Type RM Length L Ch R = 1,5234,419,419,419
BEGIN DESCRIPTION:
UNT 1034 IN LATR 10.0
END DESCRIPTION:
XS GIS Cut Line= 3
      2916173.83     10095009.36      2915326.56     10094571.84
      2914452.53     10094436.57
#Sta/Elev= 30
  4324.3 1240.11  4465.4 1234.80  4583.7 1231.16  4673.1 1228.66  4784.8 1225.31
  4801.3 1225.40  4943.8 1219.92  4956.3 1220.15  4962.0 1219.59  4978.5 1220.13
  4993.7 1216.68  4997.6 1216.06  5000.4 1215.56  5003.6 1216.06  5016.9 1217.80
  5050.6 1220.45  5083.6 1221.43  5155.7 1221.62  5216.5 1222.68  5244.3 1222.00
  5367.8 1222.96  5407.5 1224.62  5548.2 1226.10  5693.2 1227.80  5819.3 1230.71
  5903.3 1231.58  5974.2 1234.22  6004.5 1234.33  6068.5 1237.16  6162.3 1241.08
#Mann=9,-1,0
  4324.3     0.1       0  4583.7    0.05       0  4673.1     0.1       0
  4943.8    0.16       0  4993.7     0.1       0  4997.6    0.07       0
  5003.6     0.1       0  5548.2    0.05       0  6068.5     0.1       0
Bank Sta=4997.6,5003.6
Exp/Cntr=0.3,0.1

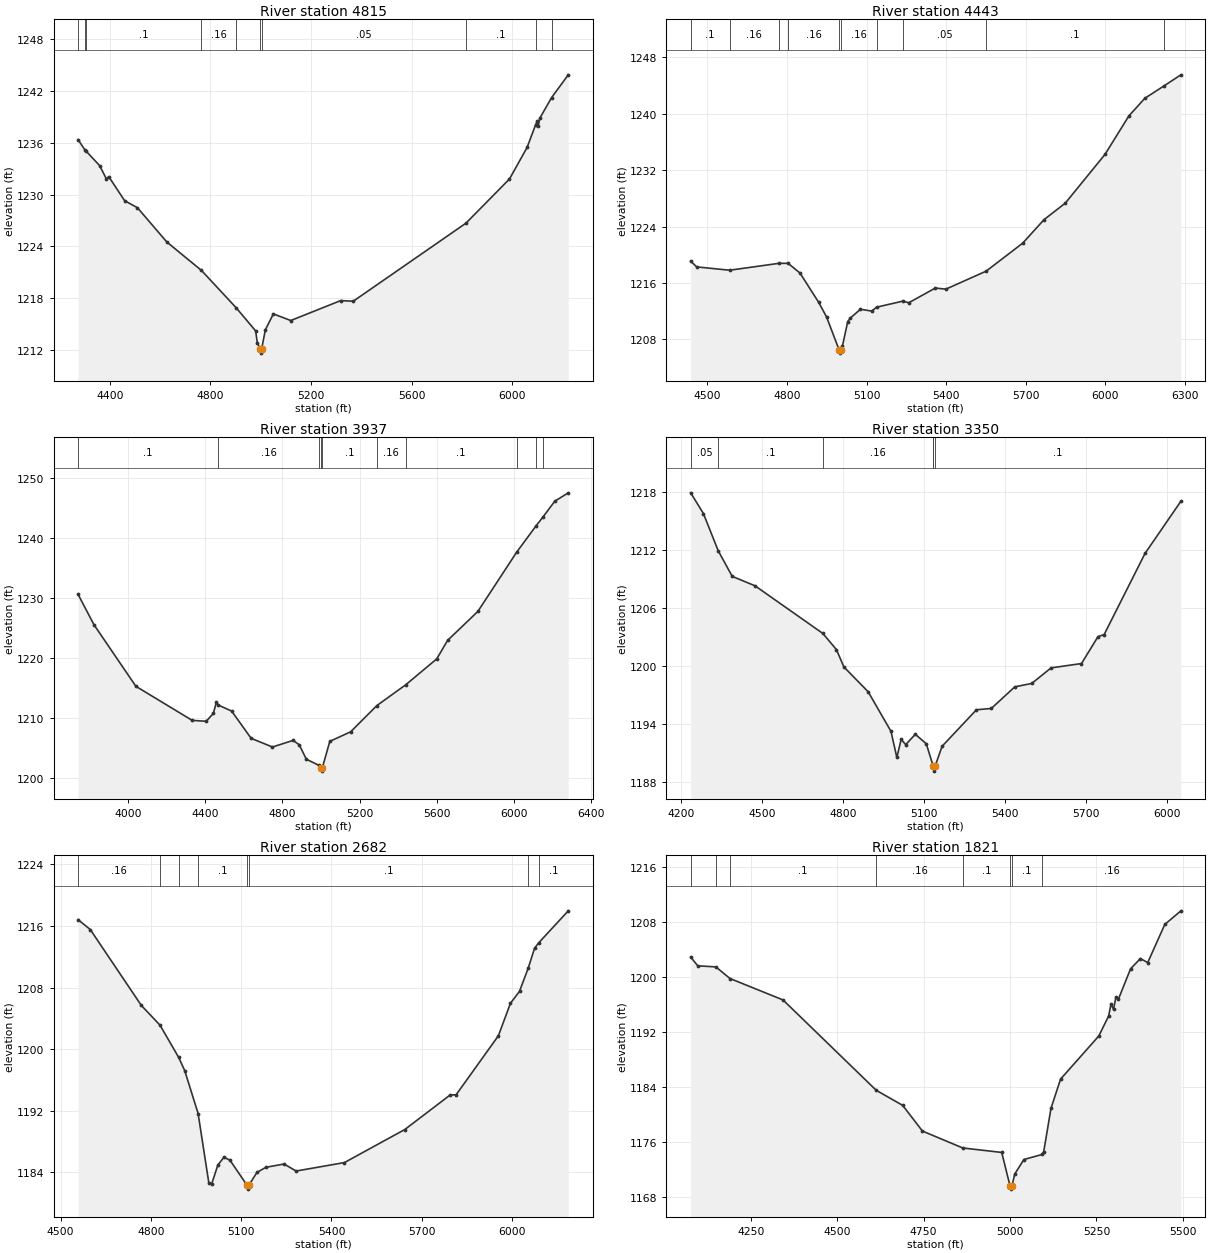
Type RM Length L Ch R = 1,4815,372,372,372
BEGIN DESCRIPTION:
UNT 1034 IN LATR 9.0
END DESCRIPTION:
XS GIS Cut Line= 4
      2916291.83     10094658.64      2915826.56     10094346.15
      2915538.37     10094252.40      2914455.04     10094304.48
#Sta/Elev= 30
  4274.0 1236.38  4302.1 1235.15  4304.1 1235.10  4359.9 1233.36  4387.0 1231.80
  4395.9 1232.09  4459.0 1229.30  4510.0 1228.48  4627.0 1224.50  4764.4 1221.21
  4901.4 1216.91  4979.7 1214.20  4986.3 1212.83  4997.7 1212.12  5000.5 1211.62
  5003.7 1212.12  5018.3 1214.32  5050.2 1216.17  5119.3 1215.40  5317.6 1217.71
  5367.7 1217.64  5815.6 1226.69  5988.4 1231.81  6058.5 1235.47  6092.7 1238.13
  6098.0 1238.49  6103.0 1237.98  6108.5 1238.83  6155.8 1241.25  6222.1 1243.89
#Mann=10,-1,0
  4274.0     0.1       0  4302.1    0.05       0  4304.1     0.1       0
  4764.4    0.16       0  4901.4    0.05       0  4997.7   0.035       0
  5003.7    0.05       0  5815.6     0.1       0  6092.7    0.05       0
  6155.8     0.1       0
Bank Sta=4997.7,5003.7
Exp/Cntr=0.3,0.1

Type RM Length L Ch R = 1,4443,506,506,506
BEGIN DESCRIPTION:
UNT 1034 IN LATR 8.0
END DESCRIPTION:
XS GIS Cut Line= 4
      2916132.09     10094162.10      2915847.39     10093936.42
      2915468.92     10093926.01      2914362.33     10093922.54
#Sta/Elev= 30
  4437.0 1219.10  4459.6 1218.28  4583.9 1217.81  4768.8 1218.78  4804.2 1218.79
  4849.2 1217.41  4919.3 1213.28  4949.3 1211.19  4996.3 1206.56  4999.0 1206.06
  5002.3 1206.56  5009.3 1207.08  5029.3 1210.54  5039.3 1211.04  5077.1 1212.28
  5119.3 1212.02  5138.2 1212.57  5236.9 1213.43  5259.4 1213.20  5359.4 1215.28
  5399.4 1215.13  5551.3 1217.68  5689.4 1221.66  5769.4 1224.98  5849.4 1227.31
  5999.4 1234.23  6089.4 1239.68  6149.4 1242.17  6221.4 1243.92  6285.5 1245.50
#Mann=10,-1,0
  4437.0     0.1       0  4583.9    0.16       0  4768.8     0.1       0
  4804.2    0.16       0  4996.3    0.07       0  5002.3    0.16       0
  5138.2     0.1       0  5236.9    0.05       0  5551.3     0.1       0
  6221.4    0.05       0
Bank Sta=4996.3,5002.3
Exp/Cntr=0.3,0.1

Type RM Length L Ch R = 1,3937,587,587,587
BEGIN DESCRIPTION:
Mapping XS 7b1bddc1
END DESCRIPTION:
XS GIS Cut Line= 4
      2916633.24     10094062.13      2915709.63     10093499.63
      2915237.41     10093346.86      2914279.08     10093409.36
#Sta/Elev= 30
  3742.3 1230.62  3824.9 1225.54  4041.8 1215.28  4333.3 1209.60  4406.0 1209.45
  4442.7 1210.76  4458.2 1212.60  4468.1 1212.16  4537.6 1211.15  4638.4 1206.61
  4748.8 1205.16  4855.2 1206.26  4887.2 1205.55  4924.4 1203.12  4988.7 1202.12
  5000.6 1201.64  5003.4 1201.14  5006.6 1201.64  5045.7 1206.10  5153.8 1207.70
  5289.4 1212.07  5437.8 1215.51  5599.6 1219.86  5655.4 1222.93  5812.4 1227.77
  6013.3 1237.65  6112.5 1241.98  6148.0 1243.45  6210.9 1246.15  6280.4 1247.54
#Mann=10,-1,0
  3742.3     0.1       0  4468.1    0.16       0  4988.7     0.1       0
  5000.6    0.07       0  5006.6     0.1       0  5289.4    0.16       0
  5437.8     0.1       0  6013.3    0.16       0  6112.5     0.1       0
  6148.0    0.16       0
Bank Sta=5000.6,5006.6
Exp/Cntr=0.3,0.1

Type RM Length L Ch R = 1,3350,668,668,668
BEGIN DESCRIPTION:
UNT 1034 IN LATR 6.0
END DESCRIPTION:
XS GIS Cut Line= 4
      2916482.84     10093835.76      2916139.06     10093419.06
      2915975.87     10093044.06      2915128.64     10092856.56
#Sta/Elev= 30
  4234.2 1217.90  4281.3 1215.76  4336.5 1211.89  4388.1 1209.26  4472.8 1208.28
  4724.2 1203.35  4774.4 1201.68  4802.0 1199.89  4891.7 1197.33  4976.5 1193.23
  4998.3 1190.52  5014.3 1192.40  5031.1 1191.85  5066.7 1192.92  5107.4 1191.94
  5132.0 1189.72  5134.0 1189.61  5136.7 1189.11  5140.0 1189.61  5165.9 1191.68
  5293.4 1195.46  5348.3 1195.59  5435.5 1197.83  5498.2 1198.18  5569.9 1199.79
  5682.6 1200.24  5744.0 1203.03  5766.5 1203.23  5918.1 1211.63  6051.1 1217.03
#Mann=6,-1,0
  4234.2    0.05       0  4336.5     0.1       0  4724.2    0.16       0
  5132.0     0.1       0  5134.0    0.07       0  5140.0     0.1       0
Bank Sta=5134,5140
Exp/Cntr=0.3,0.1

Type RM Length L Ch R = 1,2682,861,861,861
BEGIN DESCRIPTION:
UNT 1034 IN LATR 5.0
END DESCRIPTION:
XS GIS Cut Line= 4
      2916788.37     10092717.68      2916527.95     10092669.06
      2916080.03     10092669.06      2915166.85     10092735.03
#Sta/Elev= 30
  4558.2 1216.84  4598.8 1215.55  4768.5 1205.69  4830.5 1203.13  4892.5 1198.94
  4912.6 1197.22  4957.0 1191.66  4992.6 1182.66  5002.6 1182.57  5022.6 1184.97
  5042.6 1185.97  5062.6 1185.61  5119.6 1182.34  5122.4 1181.84  5125.6 1182.34
  5152.6 1184.02  5182.6 1184.68  5242.6 1185.10  5282.6 1184.19  5443.1 1185.29
  5643.6 1189.58  5794.0 1194.06  5814.0 1194.09  5954.4 1201.75  5994.5 1205.97
  6024.6 1207.52  6054.0 1210.59  6074.7 1213.13  6088.5 1213.83  6186.6 1217.98
#Mann=8,-1,0
  4558.2    0.16       0  4830.5     0.1       0  4892.5    0.16       0
  4957.0     0.1       0  5119.6    0.07       0  5125.6     0.1       0
  6054.0    0.05       0  6088.5     0.1       0
Bank Sta=5119.6,5125.6
Exp/Cntr=0.3,0.1

Type RM Length L Ch R = 1,1821,524,524,524
BEGIN DESCRIPTION:
UNT 1034 IN LATR 4.0
END DESCRIPTION:
XS GIS Cut Line= 4
      2916791.83     10092419.06      2916229.34     10092047.54
      2915850.87     10091926.01      2915602.16     10091684.21
#Sta/Elev= 30
  4076.0 1202.97  4096.4 1201.69  4148.9 1201.53  4189.7 1199.84  4343.2 1196.72
  4613.0 1183.57  4689.4 1181.38  4746.6 1177.64  4863.2 1175.18  4976.0 1174.53
  4999.9 1169.69  5002.6 1169.19  5005.9 1169.69  5013.6 1171.38  5040.2 1173.50
  5092.6 1174.23  5097.6 1174.66  5118.6 1180.95  5146.3 1185.20  5257.0 1191.48
  5285.3 1194.38  5292.3 1196.13  5299.5 1195.35  5306.4 1197.11  5313.6 1196.82
  5348.9 1201.26  5377.2 1202.74  5398.5 1202.16  5447.9 1207.71  5494.5 1209.69
#Mann=8,-1,0
  4076.0     0.1       0  4148.9    0.16       0  4189.7     0.1       0
  4613.0    0.16       0  4863.2     0.1       0  4999.9    0.07       0
  5005.9     0.1       0  5092.6    0.16       0
Bank Sta=4999.9,5005.9
Exp/Cntr=0.3,0.1

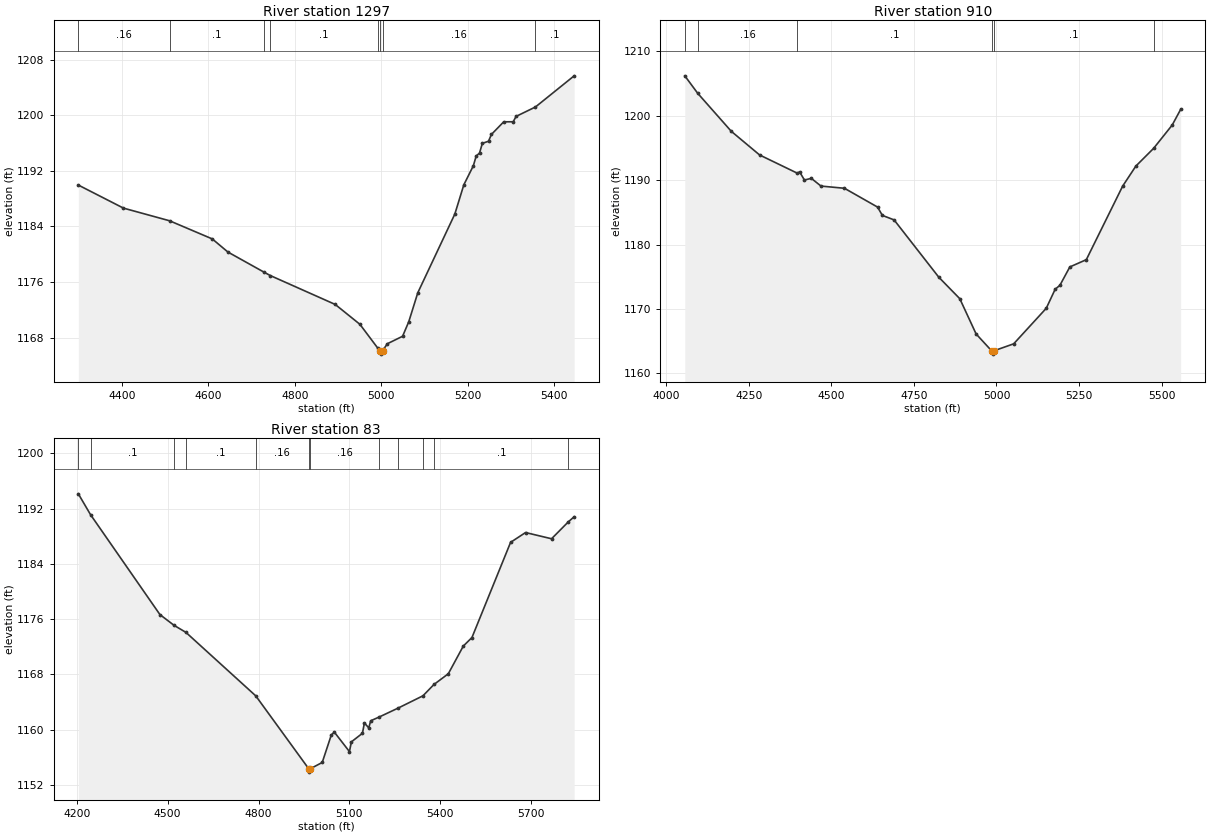
Type RM Length L Ch R = 1,1297,387,387,387
BEGIN DESCRIPTION:
UNT 1034 IN LATR 3.0
END DESCRIPTION:
XS GIS Cut Line= 2
      2916913.39     10092096.16      2916042.65     10091350.32
#Sta/Elev= 30
  4299.7 1189.95  4404.1 1186.63  4510.7 1184.81  4609.4 1182.20  4645.6 1180.31
  4730.1 1177.38  4743.5 1176.93  4893.7 1172.77  4950.8 1169.91  4992.5 1166.45
  4997.2 1166.12  4999.9 1165.62  5003.2 1166.12  5014.4 1167.12  5049.5 1168.19
  5063.8 1170.29  5084.7 1174.46  5170.3 1185.78  5191.1 1189.99  5213.1 1192.73
  5219.7 1194.13  5227.4 1194.56  5233.9 1195.95  5248.2 1196.26  5254.8 1197.23
  5283.3 1199.05  5305.3 1199.06  5311.9 1199.83  5356.8 1201.19  5446.2 1205.67
#Mann=8,-1,0
  4299.7    0.16       0  4510.7     0.1       0  4730.1    0.16       0
  4743.5     0.1       0  4992.5    0.16       0  4997.2    0.07       0
  5003.2    0.16       0  5356.8     0.1       0
Bank Sta=4997.2,5003.2
Exp/Cntr=0.3,0.1

Type RM Length L Ch R = 1,910,827,827,827
BEGIN DESCRIPTION:
UNT 1034 IN LATR 2.0
END DESCRIPTION:
XS GIS Cut Line= 4
      2917364.72     10091953.76      2916802.26     10091540.59
      2916521.01     10091221.15      2916142.97     10091231.55
#Sta/Elev= 30
  4056.1 1206.18  4095.2 1203.47  4196.9 1197.57  4282.6 1193.90  4397.3 1191.06
  4403.7 1191.29  4418.4 1190.01  4439.3 1190.27  4468.6 1189.07  4539.6 1188.73
  4639.9 1185.81  4654.5 1184.52  4690.0 1183.82  4825.5 1174.92  4889.0 1171.59
  4938.4 1166.12  4985.6 1163.49  4988.4 1162.99  4991.6 1163.49  5052.2 1164.59
  5150.9 1170.11  5177.8 1173.06  5192.2 1173.67  5222.2 1176.52  5272.2 1177.65
  5382.2 1189.06  5422.2 1192.17  5475.9 1194.92  5532.3 1198.54  5557.8 1200.96
#Mann=6,-1,0
  4056.1     0.1       0  4095.2    0.16       0  4397.3     0.1       0
  4985.6    0.07       0  4991.6     0.1       0  5475.9    0.16       0
Bank Sta=4985.6,4991.6
Exp/Cntr=0.3,0.1

Type RM Length L Ch R = 1,83,0,0,0
BEGIN DESCRIPTION:
UNT 1034 IN LATR 1.0
END DESCRIPTION:
XS GIS Cut Line= 4
      2917413.69     10091294.50      2916978.26     10090665.41
      2916861.08     10090659.34      2916285.18     10091145.82
#Sta/Elev= 30
  4205.4 1194.13  4245.6 1191.12  4474.7 1176.66  4521.5 1175.10  4560.4 1174.09
  4791.0 1164.90  4965.5 1154.37  4968.2 1153.87  4971.5 1154.37  5010.3 1155.27
  5040.4 1159.26  5050.4 1159.65  5100.1 1156.84  5106.6 1158.25  5143.0 1159.49
  5149.5 1160.99  5163.8 1160.27  5170.3 1161.30  5197.6 1161.83  5259.6 1163.11
  5342.7 1164.91  5379.3 1166.56  5426.4 1168.10  5475.9 1172.11  5504.4 1173.34
  5631.9 1187.11  5681.3 1188.53  5767.1 1187.63  5823.0 1190.10  5841.7 1190.81
#Mann=12,-1,0
  4205.4    0.16       0  4245.6     0.1       0  4521.5    0.16       0
  4560.4     0.1       0  4791.0    0.16       0  4965.5    0.07       0
  4971.5    0.16       0  5197.6    0.05       0  5259.6    0.16       0
  5342.7    0.05       0  5379.3     0.1       0  5823.0    0.05       0
Bank Sta=4965.5,4971.5
Exp/Cntr=0.3,0.1

Chan Stop Cuts=-1