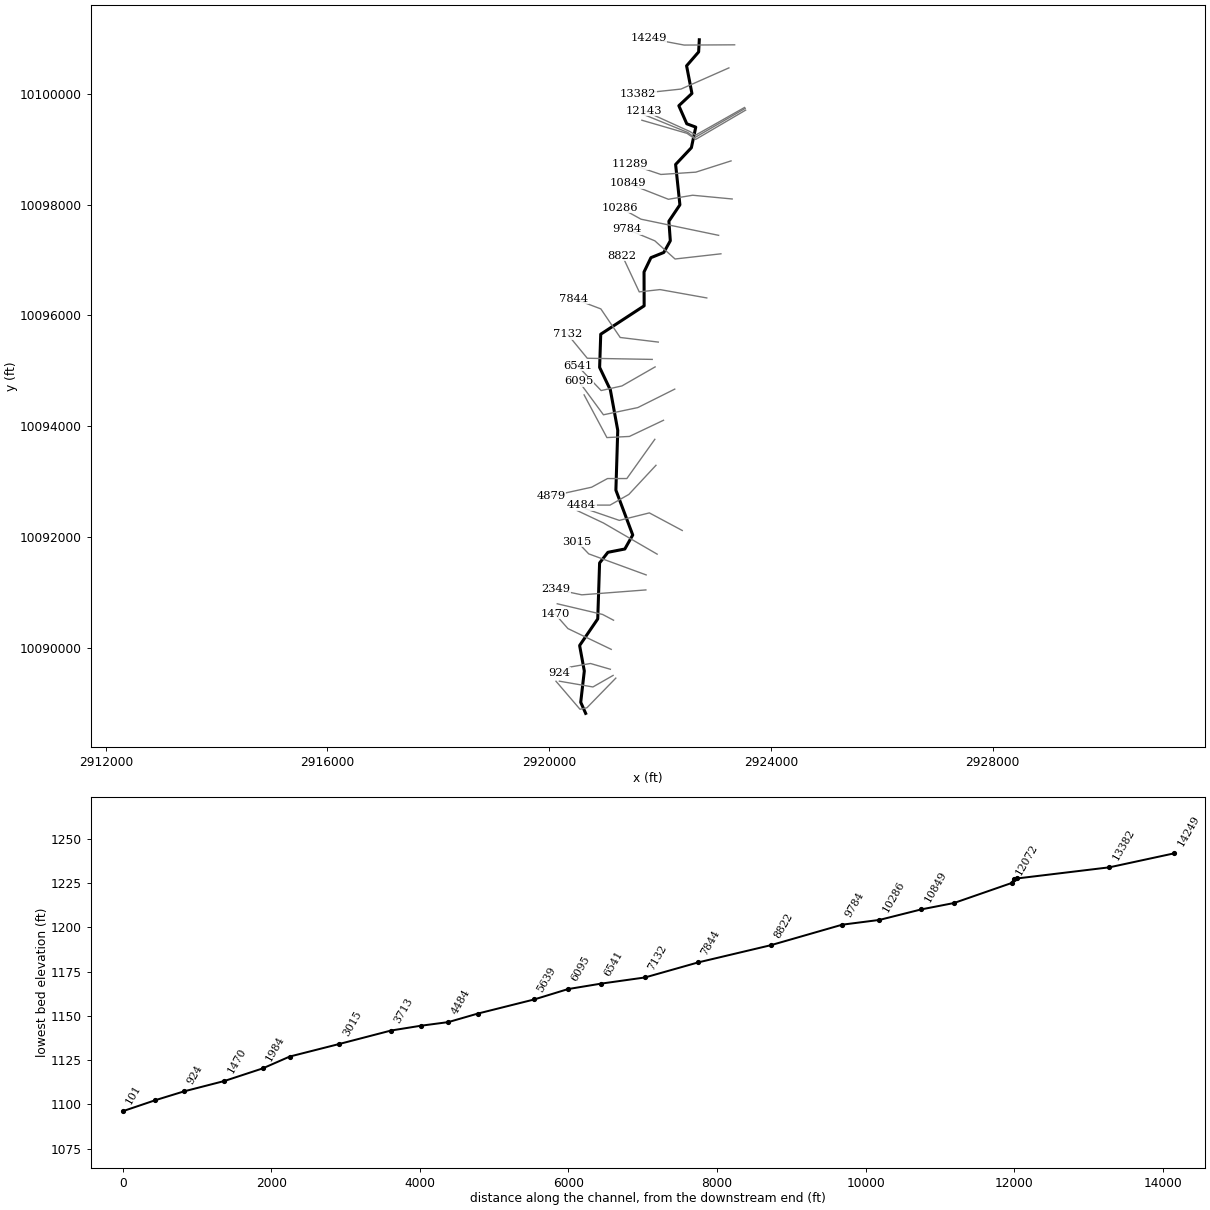
--- UNT 0035 IN LATR.prj (project) ---

Proj Title=UNT 1035 IN LATR Base Level Engineering
Current Plan=p01
Default Exp/Contr=0.3,0.1
English Units
Geom File=g01
Flow File=f01
Plan File=p01
Y Axis Title=Elevation
X Axis Title(PF)=Main Channel Distance
X Axis Title(XS)=Station
BEGIN DESCRIPTION:
UNT 1035 IN LATR
END DESCRIPTION:
DSS Export Rating Curves= 0
DSS Export Rating Curve Sorted= 0
DSS Export Volume Flow Curves= 0
DXF OffsetX= 0
DXF OffsetY= 0
DXF ScaleX= 1
DXF ScaleY= 10

--- UNT 0035 IN LATR.p01 (plan) ---

Plan Title=Multiple Run
Short Identifier=Multiple
Geom File=g01
Flow File=f01
Subcritical Flow
K Sum by GR= 0
Std Step Tol= 0.01
Critical Tol= 0.01
Num of Std Step Trials= 20
Max Error Tol= 0.3
Flow Tol Ratio= 0.001
Split Flow NTrial= 30
Split Flow Tol= 0.02
Split Flow Ratio= 0.02
Log Output Level= 0
Friction Slope Method= 1
Unsteady Friction Slope Method= 2
Unsteady Bridges Friction Slope Method= 1
Parabolic Critical Depth
Global Vel Dist=  1 , 1 , 1
Global Log Level= 0
CheckData=True
Encroach Param= -1, 0, 0, 0
BEGIN DESCRIPTION:
Multiple Run
END DESCRIPTION:

--- UNT 0035 IN LATR.f01 (steady flow) ---

Flow Title=Multiple
Program Version=4.10
Number of Profiles= 7
Profile Names=10-year,25-year,50-year,1pct_min,100-year,1pct_plu,500-year
River Rch & RM=UNT 1035 IN LATR,Reach-1         ,14249
     804    1162    1472    1367    1848    2500    2923
River Rch & RM=UNT 1035 IN LATR,Reach-1         ,13382
    1219    1790    2291    2143    2898    3919    4658
River Rch & RM=UNT 1035 IN LATR,Reach-1         ,4879
    1927    2895    3762    3568    4826    6526    7978
River Rch & RM=UNT 1035 IN LATR,Reach-1         ,4484
    1927    2895    3762    3568    4826    6526    7978
River Rch & RM=UNT 1035 IN LATR,Reach-1         ,2349
    2024    3046    3964    3764    5090    6883    8432
Boundary for River Rch & Prof#=UNT 1035 IN LATR,Reach-1         , 1
Up Type= 0
Dn Type= 3
Dn Slope=0.005
Boundary for River Rch & Prof#=UNT 1035 IN LATR,Reach-1         , 2
Up Type= 0
Dn Type= 3
Dn Slope=0.005
Boundary for River Rch & Prof#=UNT 1035 IN LATR,Reach-1         , 3
Up Type= 0
Dn Type= 3
Dn Slope=0.005
Boundary for River Rch & Prof#=UNT 1035 IN LATR,Reach-1         , 4
Up Type= 0
Dn Type= 3
Dn Slope=0.005
Boundary for River Rch & Prof#=UNT 1035 IN LATR,Reach-1         , 5
Up Type= 0
Dn Type= 3
Dn Slope=0.005
Boundary for River Rch & Prof#=UNT 1035 IN LATR,Reach-1         , 6
Up Type= 0
Dn Type= 3
Dn Slope=0.005
Boundary for River Rch & Prof#=UNT 1035 IN LATR,Reach-1         , 7
Up Type= 0
Dn Type= 3
Dn Slope=0.005
DSS Import GetInterval= 0
DSS Import GetPeak= 0
DSS Import FillOption= 0

--- UNT 0035 IN LATR.g01 (geometry) ---

Geom Title=Existing Conditions
Program Version=4.10

River Reach=UNT 1035 IN LATR,Reach-1
Reach XY= 30
      2922708.47     10100973.73      2922696.69     10100754.47
      2922479.21     10100503.51      2922575.59     10100004.68
      2922339.26      10099783.2      2922482.64     10099457.16
      2922644.66     10099396.98      2922565.46     10099024.95
      2922281.22     10098722.59       2922358.5     10097993.79
      2922160.06     10097698.07      2922185.59     10097345.11
      2922068.35     10097134.21      2921835.99     10097040.26
       2921711.5     10096782.21      2921713.57     10096171.04
      2920930.28     10095658.33      2920910.25      10095059.3
      2921104.08     10094652.33      2921237.33     10093923.09
      2921203.68     10092843.23       2921507.6     10092034.17
      2921364.96     10091781.07       2921059.5     10091721.24
      2920909.72     10091529.06      2920876.23     10090519.33
      2920549.28     10090038.73       2920633.9     10089578.57
      2920569.34     10089014.29      2920658.47     10088813.73

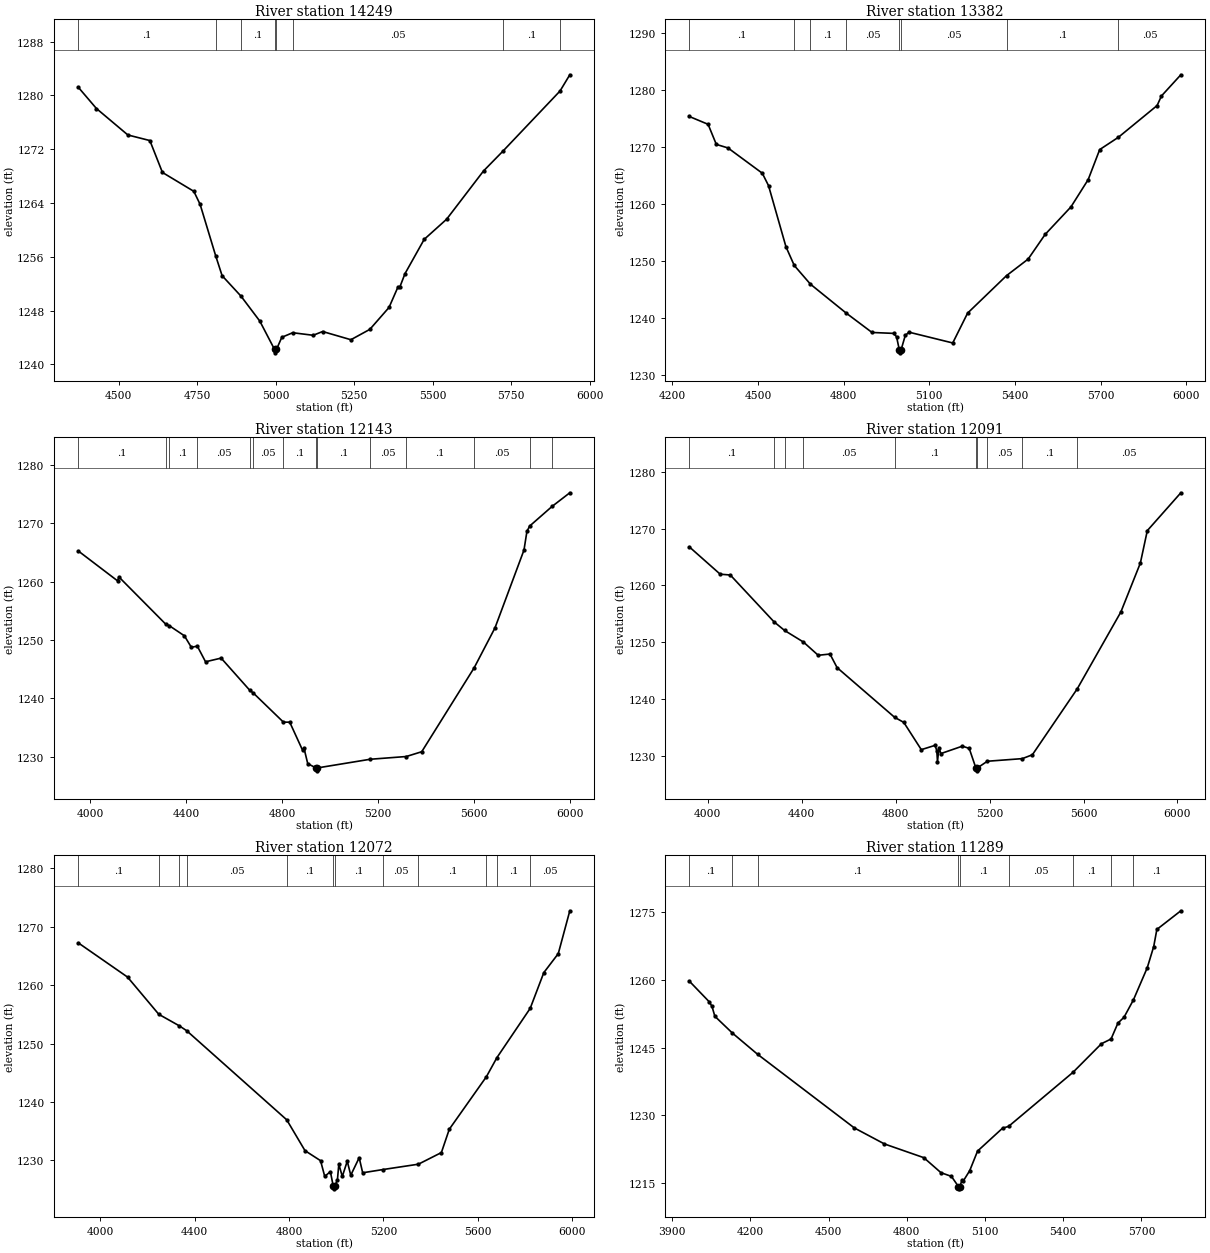
Type RM Length L Ch R = 1 ,14249   ,867,867,867
BEGIN DESCRIPTION:
UNT 1035 IN LATR 29.0
END DESCRIPTION:
XS GIS Cut Line= 3
      2923346.27      10100882.6      2922434.85     10100878.26
      2921792.97      10100999.7
#Sta/Elev= 30
  4371.8 1281.21  4429.6 1278.05  4529.6 1274.12  4599.6 1273.29  4639.6 1268.55
  4739.6 1265.74  4759.6  1263.8    4809 1256.18  4829.6  1253.2  4889.7 1250.16
  4949.6 1246.45  4996.6 1242.23  4999.4 1241.73  5002.6 1242.23  5019.6 1244.04
  5054.3 1244.72  5119.6 1244.34  5149.6  1244.9  5239.6 1243.68  5299.9 1245.22
    5361 1248.48  5389.9 1251.57    5395 1251.47  5411.9 1253.51  5472.9  1258.6
  5544.2 1261.59  5661.8 1268.77  5724.1 1271.74  5905.4 1280.66  5936.5 1283.07
#Mann= 8 ,-1 , 0
  4371.8      .1       0    4809     .05       0  4889.7      .1       0
  4996.6     .07       0  5002.6      .1       0  5054.3     .05       0
  5724.1      .1       0  5905.4     .05       0
Bank Sta=4996.6,5002.6
XS Rating Curve= 0 ,0
Exp/Cntr=0.3,0.1

Type RM Length L Ch R = 1 ,13382   ,1239,1239,1239
BEGIN DESCRIPTION:
UNT 1035 IN LATR 28.0
END DESCRIPTION:
XS GIS Cut Line= 3
      2923242.17     10100465.95      2922378.43     10100083.99
      2921605.84     10100001.53
#Sta/Elev= 30
  4259.7  1275.3  4325.4 1273.93  4354.2 1270.41    4395 1269.79  4515.2 1265.36
  4537.1 1263.18  4598.1 1252.47  4627.2 1249.19  4683.9 1245.91  4808.7 1240.86
  4899.5 1237.45  4974.9 1237.29  4985.4 1236.71  4995.2 1234.38  4997.9 1233.88
  5001.2 1234.38    5016 1236.93  5029.1  1237.5  5182.2 1235.61  5234.3 1240.84
  5370.6 1247.41  5446.3 1250.31  5505.8 1254.63  5596.3 1259.46  5656.6 1264.24
  5696.9  1269.5  5762.5 1271.66    5898 1277.22  5913.1 1278.89  5981.1 1282.61
#Mann= 8 ,-1 , 0
  4259.7      .1       0  4627.2     .05       0  4683.9      .1       0
  4808.7     .05       0  4995.2    .035       0  5001.2     .05       0
  5370.6      .1       0  5762.5     .05       0
Bank Sta=4995.2,5001.2
XS Rating Curve= 0 ,0
Exp/Cntr=0.3,0.1

Type RM Length L Ch R = 1 ,12143   ,52,52,52
BEGIN DESCRIPTION:
Mapping XS b74a35f5
END DESCRIPTION:
XS GIS Cut Line= 4
      2923523.39     10099750.66      2922643.18     10099253.26
      2922536.41     10099318.37      2921705.68     10099695.97
#Sta/Elev= 30
  3949.6 1265.23  4113.2 1260.12    4119 1260.78  4314.2  1252.7  4328.8 1252.45
  4391.7 1250.72  4420.7 1248.75  4445.6 1248.95  4479.9 1246.27  4544.9  1246.9
    4665 1241.36  4678.7 1240.94  4804.6 1235.94  4830.8 1235.94  4884.2 1231.15
    4890 1231.53  4905.9 1228.84  4940.1 1228.11  4942.8 1227.61  4946.1 1228.11
  5165.9 1229.59  5316.5 1230.06    5381 1230.88  5599.5 1245.24  5686.4 1252.08
  5807.2 1265.39  5819.4 1268.57  5830.7 1269.49  5924.1 1272.85  5998.2 1275.19
#Mann= 14 ,-1 , 0
  3949.6      .1       0  4314.2     .05       0  4328.8      .1       0
  4445.6     .05       0    4665      .1       0  4678.7     .05       0
  4804.6      .1       0  4940.1     .07       0  4946.1      .1       0
  5165.9     .05       0  5316.5      .1       0  5599.5     .05       0
  5830.7      .1       0  5924.1     .05       0
Bank Sta=4940.1,4946.1
XS Rating Curve= 0 ,0
Exp/Cntr=0.3,0.1

Type RM Length L Ch R = 1 ,12091   ,19,19,19
BEGIN DESCRIPTION:
UNT 1035 IN LATR 27.0
END DESCRIPTION:
XS GIS Cut Line= 4
       2923536.4     10099735.03      2922624.96     10099206.39
      2922502.56     10099300.14      2921682.88     10099633.21
#Sta/Elev= 30
  3921.7 1266.78  4053.1 1261.97  4096.1 1261.83  4282.1 1253.59  4327.3 1252.06
  4407.6 1250.02  4470.4 1247.69  4520.5 1247.91  4550.7 1245.52  4795.6 1236.77
  4834.8 1235.87  4909.3 1231.07  4968.1 1231.83  4975.4 1230.85  4978.2 1228.96
  4984.5 1231.42  4992.7 1230.38  5084.3 1231.69  5113.3 1231.29  5141.7 1227.84
  5144.5 1227.34  5147.7 1227.84  5190.5 1229.03  5339.3 1229.49  5382.2 1230.17
  5573.2 1241.78    5759 1255.32    5842 1263.94  5871.5 1269.64  6014.3 1276.31
#Mann= 10 ,-1 , 0
  3921.7      .1       0  4282.1     .05       0  4327.3      .1       0
  4407.6     .05       0  4795.6      .1       0  5141.7     .07       0
  5147.7      .1       0  5190.5     .05       0  5339.3      .1       0
  5573.2     .05       0
Bank Sta=5141.7,5147.7
XS Rating Curve= 0 ,0
Exp/Cntr=0.3,0.1

Type RM Length L Ch R = 1 ,12072   ,783,783,783
BEGIN DESCRIPTION:
UNT 1035 IN LATR 26.0
END DESCRIPTION:
XS GIS Cut Line= 4
      2923544.22     10099703.78      2922643.18     10099175.14
      2922486.93     10099284.51      2921672.65     10099521.26
#Sta/Elev= 30
  3906.9 1267.24  4115.5 1261.39  4248.1 1255.01  4334.9 1253.04  4366.3  1252.2
  4790.4 1236.94  4867.8 1231.66  4933.8 1229.94  4951.4 1227.26  4975.5 1228.06
  4987.3 1225.62    4990 1225.12  4993.3 1225.62  5005.1  1226.6  5011.2 1229.33
    5026 1227.24  5046.9 1229.86  5061.8 1227.45  5097.5 1230.45  5112.3 1227.87
  5199.2 1228.43  5348.5 1229.34  5445.9 1231.33  5479.5 1235.33    5637 1244.34
  5681.3 1247.59  5822.4 1256.03  5880.1 1262.15  5941.4  1265.4  5990.3 1272.74
#Mann= 12 ,-1 , 0
  3906.9      .1       0  4248.1     .05       0  4334.9      .1       0
  4366.3     .05       0  4790.4      .1       0  4987.3     .07       0
  4993.3      .1       0  5199.2     .05       0  5348.5      .1       0
    5637     .05       0  5681.3      .1       0  5822.4     .05       0
Bank Sta=4987.3,4993.3
XS Rating Curve= 0 ,0
Exp/Cntr=0.3,0.1

Type RM Length L Ch R = 1 ,11289   ,440,440,440
BEGIN DESCRIPTION:
UNT 1035 IN LATR 24.0
END DESCRIPTION:
XS GIS Cut Line= 4
      2923281.23     10098787.13      2922645.79     10098583.99
      2922015.58     10098542.33       2921459.9     10098729.29
#Sta/Elev= 30
    3966 1259.75  4042.4 1255.17  4052.9 1254.15  4063.9 1251.96  4130.4 1248.28
  4228.1 1243.52  4598.8 1227.21  4714.3 1223.66  4865.2 1220.62  4931.1 1217.29
  4971.2 1216.47  4998.2 1214.21    5001 1213.71  5004.2 1214.21  5011.1 1215.65
  5016.2 1215.41  5041.3 1217.74  5071.4 1222.08  5167.1 1227.15  5190.3 1227.55
  5437.4 1239.54  5546.5 1245.88  5583.4 1246.93  5609.8 1250.46    5633 1251.74
    5669 1255.58  5722.2 1262.72    5747 1267.43    5759 1271.21    5851 1275.35
#Mann= 9 ,-1 , 0
    3966      .1       0  4130.4     .05       0  4228.1      .1       0
  4998.2     .07       0  5004.2      .1       0  5190.3     .05       0
  5437.4      .1       0  5583.4     .05       0    5669      .1       0
Bank Sta=4998.2,5004.2
XS Rating Curve= 0 ,0
Exp/Cntr=0.3,0.1

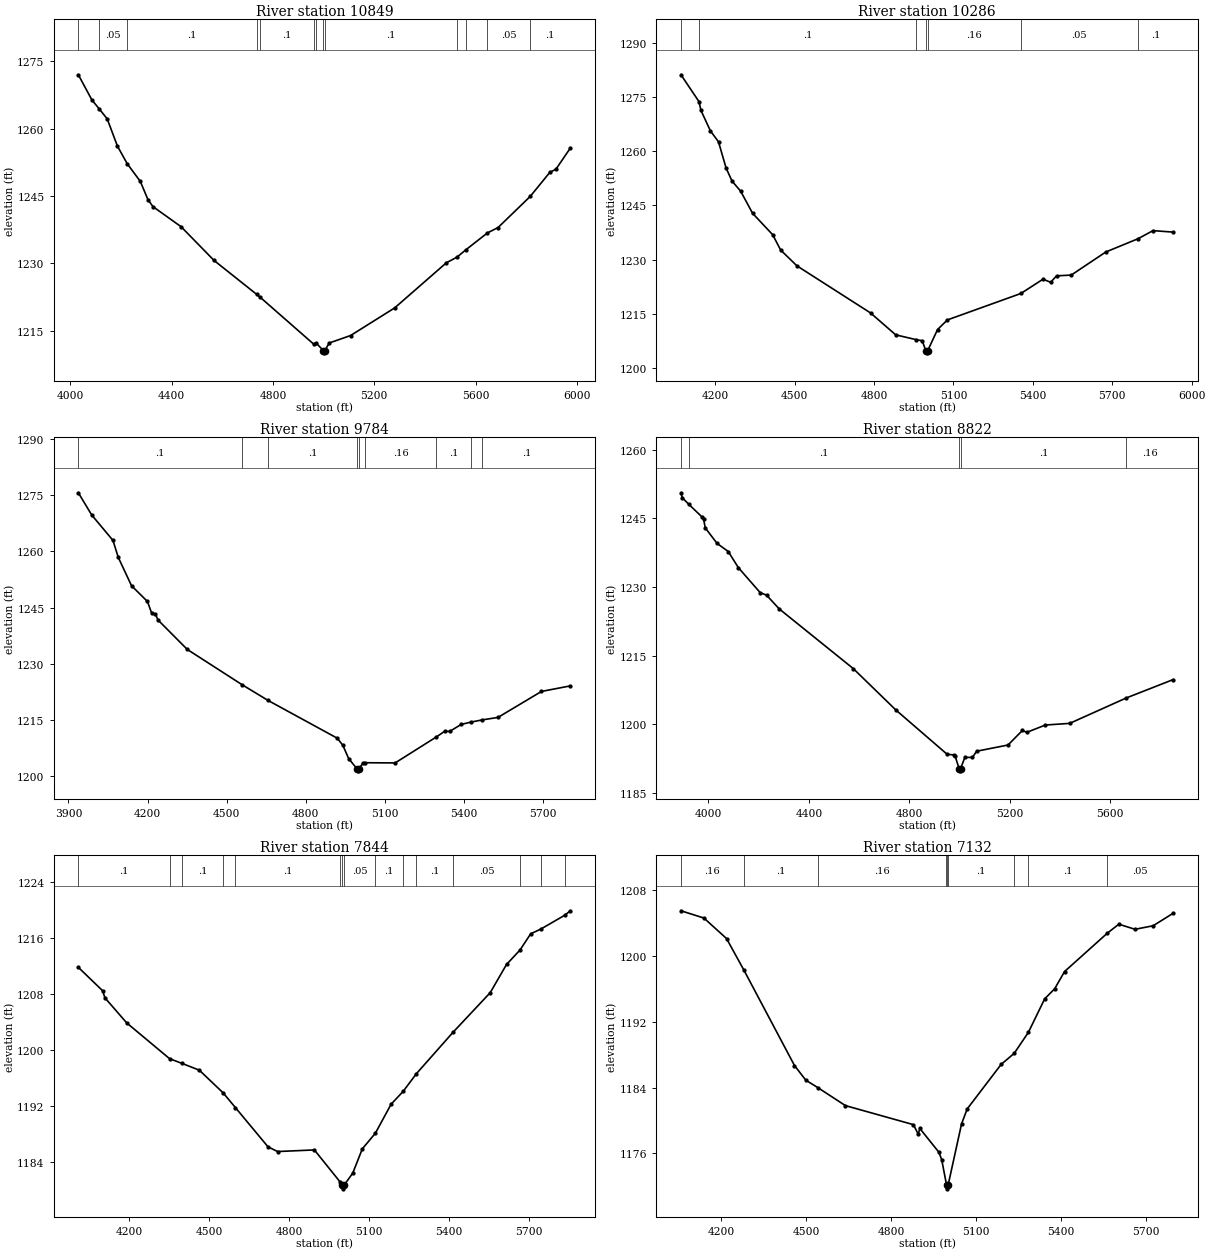
Type RM Length L Ch R = 1 ,10849   ,563,563,563
BEGIN DESCRIPTION:
UNT 1035 IN LATR 23.0
END DESCRIPTION:
XS GIS Cut Line= 4
      2923302.02     10098099.62       2922588.5     10098167.33
        2922151.     10098094.41      2921422.65     10098380.55
#Sta/Elev= 30
  4031.7 1271.98  4085.5 1266.36  4114.7 1264.36  4145.8 1262.16  4185.9 1256.13
  4224.6  1252.2  4276.4 1248.26  4306.5 1244.21  4326.6 1242.63  4437.1 1238.19
  4567.7 1230.66  4736.1 1223.11  4749.4 1222.49  4962.2 1211.98  4971.1 1212.28
  4998.9 1210.61  5001.7 1210.11  5004.9 1210.61  5022.2  1212.3  5106.6 1213.96
  5280.5  1220.1  5484.8 1230.15  5526.4 1231.39  5562.5 1233.07  5647.1  1236.8
  5688.9 1237.99  5815.8 1244.91    5893 1250.25  5917.4 1250.97  5974.5 1255.69
#Mann= 13 ,-1 , 0
  4031.7      .1       0  4114.7     .05       0  4224.6      .1       0
  4736.1     .05       0  4749.4      .1       0  4962.2     .05       0
  4971.1      .1       0  4998.9     .07       0  5004.9      .1       0
  5526.4     .05       0  5562.5      .1       0  5647.1     .05       0
  5815.8      .1       0
Bank Sta=4998.9,5004.9
XS Rating Curve= 0 ,0
Exp/Cntr=0.3,0.1

Type RM Length L Ch R = 1 ,10286   ,502,502,502
BEGIN DESCRIPTION:
UNT 1035 IN LATR 22.0
END DESCRIPTION:
XS GIS Cut Line= 3
      2923057.29     10097443.36      2921656.21     10097735.04
      2921282.35     10097942.74
#Sta/Elev= 30
  4070.9 1281.13  4138.8 1273.71  4146.3 1271.28  4182.1  1265.6  4212.7 1262.57
  4241.3 1255.31  4263.8 1251.71  4296.5 1248.89  4341.5 1242.78    4417 1236.89
  4447.6 1232.61  4508.9 1228.25    4787 1215.21    4882 1209.15  4959.3 1207.82
  4982.2 1207.52  4996.2 1204.67    4999 1204.17  5002.2 1204.67  5040.1 1210.62
  5077.2 1213.28  5354.9  1220.6  5438.4 1224.55  5467.5  1223.7  5489.5 1225.48
  5545.1 1225.69  5675.6 1232.08  5796.1 1235.71    5854 1237.99  5929.7 1237.59
#Mann= 7 ,-1 , 0
  4070.9     .16       0  4138.8      .1       0  4959.3     .16       0
  4996.2     .07       0  5002.2     .16       0  5354.9     .05       0
  5796.1      .1       0
Bank Sta=4996.2,5002.2
XS Rating Curve= 0 ,0
Exp/Cntr=0.3,0.1

Type RM Length L Ch R = 1 ,9784    ,962,962,962
BEGIN DESCRIPTION:
UNT 1035 IN LATR 21.0
END DESCRIPTION:
XS GIS Cut Line= 4
       2923098.9     10097110.03      2922270.79     10097016.29
      2921906.21     10097344.41      2921406.17     10097552.76
#Sta/Elev= 30
  3937.6 1275.59  3988.4 1269.67  4068.9 1262.89    4089 1258.37  4139.3 1250.81
  4199.7 1246.61  4215.3 1243.56  4229.9 1243.23  4239.9 1241.66  4350.7 1233.83
  4558.4 1224.43  4657.3 1220.22  4919.8 1210.15  4940.7 1208.25  4962.4 1204.75
  4994.5 1201.97  4997.2 1201.47  5000.5 1201.97  5018.4 1203.66  5026.3 1203.63
  5138.8 1203.58  5293.8 1210.45  5327.1 1212.04  5345.5 1211.98    5389 1213.83
  5425.7 1214.46  5469.9 1215.06  5528.6 1215.71  5693.3 1222.63  5803.2 1224.12
#Mann= 9 ,-1 , 0
  3937.6      .1       0  4558.4     .05       0  4657.3      .1       0
  4994.5     .07       0  5000.5      .1       0  5026.3     .16       0
  5293.8      .1       0  5425.7     .16       0  5469.9      .1       0
Bank Sta=4994.5,5000.5
XS Rating Curve= 0 ,0
Exp/Cntr=0.3,0.1

Type RM Length L Ch R = 1 ,8822    ,978,978,978
BEGIN DESCRIPTION:
UNT 1035 IN LATR 19.0
END DESCRIPTION:
XS GIS Cut Line= 4
      2922843.73     10096313.16      2921999.96      10096464.2
      2921624.96     10096422.54      2921317.67     10097078.76
#Sta/Elev= 30
  3890.8 1250.57  3896.1 1249.48  3922.3 1248.03  3975.8 1245.23  3980.8 1244.79
  3987.6  1242.9  4034.6 1239.51    4079 1237.75  4119.6  1234.2  4206.1 1228.78
  4231.4 1228.22  4282.2 1225.21  4576.8 1212.19  4746.2 1203.16  4950.7 1193.47
  4977.2 1193.35  4982.3 1193.08    4998 1190.37  5000.8 1189.87    5004 1190.37
  5021.1  1192.8  5051.3 1192.81  5067.8 1194.15  5192.9 1195.51  5250.2 1198.69
  5267.5 1198.27  5341.5 1199.87  5438.3 1200.23  5664.2 1205.79  5849.9 1209.78
#Mann= 5 ,-1 , 0
  3890.8     .05       0  3922.3      .1       0    4998     .07       0
    5004      .1       0  5664.2     .16       0
Bank Sta=4998,5004
XS Rating Curve= 0 ,0
Exp/Cntr=0.3,0.1

Type RM Length L Ch R = 1 ,7844    ,712,712,712
BEGIN DESCRIPTION:
UNT 1035 IN LATR 17.0
END DESCRIPTION:
XS GIS Cut Line= 4
      2921968.72     10095516.28      2921281.21     10095599.62
      2920932.25     10096115.24      2920437.44     10096302.75
#Sta/Elev= 30
  4010.6  1211.8  4101.5 1208.46  4110.3 1207.44  4192.2 1203.85  4352.5 1198.75
  4400.1 1198.06  4464.2  1197.1  4553.7 1193.85  4599.1 1191.77  4721.6 1186.15
  4757.5 1185.48  4895.3 1185.71  4991.6 1181.14  5000.2 1180.65  5002.9 1180.15
  5006.2 1180.65  5039.1 1182.39  5075.1 1185.87  5123.8 1188.09    5183 1192.25
  5227.8 1194.06  5277.4 1196.59  5415.5 1202.54  5554.4 1208.18  5615.5 1212.21
  5666.2 1214.28    5706 1216.59  5743.7 1217.26  5833.2 1219.23  5854.9 1219.88
#Mann= 15 ,-1 , 0
  4010.6      .1       0  4352.5     .05       0  4400.1      .1       0
  4553.7     .05       0  4599.1      .1       0  4991.6     .05       0
  5000.2    .035       0  5006.2     .05       0  5123.8      .1       0
  5227.8     .05       0  5277.4      .1       0  5415.5     .05       0
  5666.2      .1       0  5743.7     .16       0  5833.2      .1       0
Bank Sta=5000.2,5006.2
XS Rating Curve= 0 ,0
Exp/Cntr=0.3,0.1

Type RM Length L Ch R = 1 ,7132    ,591,591,591
BEGIN DESCRIPTION:
UNT 1035 IN LATR 15.0
END DESCRIPTION:
XS GIS Cut Line= 3
      2921859.36     10095203.78      2920687.46     10095224.62
      2920328.06     10095662.14
#Sta/Elev= 30
  4058.2 1205.47  4139.1 1204.59  4219.1  1202.1  4280.2 1198.28  4459.2 1186.67
  4499.2 1184.89  4541.9 1183.98  4639.2  1181.8  4879.2 1179.49  4896.7 1178.31
  4901.7 1179.04  4969.2 1176.14  4979.2 1175.24    4996 1172.23  4996.2 1172.19
    4999 1171.69  5002.2 1172.19  5049.3 1179.57  5069.3  1181.4  5189.3 1186.81
  5235.4 1188.15  5285.7 1190.72    5343 1194.77  5378.2 1195.99  5413.3 1198.09
  5563.7 1202.73  5604.9 1203.84  5662.3 1203.22  5726.2 1203.65  5796.5 1205.16
#Mann= 9 ,-1 , 0
  4058.2     .16       0  4280.2      .1       0  4541.9     .16       0
    4996      .1       0  4996.2     .07       0  5002.2      .1       0
  5235.4     .05       0  5285.7      .1       0  5563.7     .05       0
Bank Sta=4996.2,5002.2
XS Rating Curve= 0 ,0
Exp/Cntr=0.3,0.1

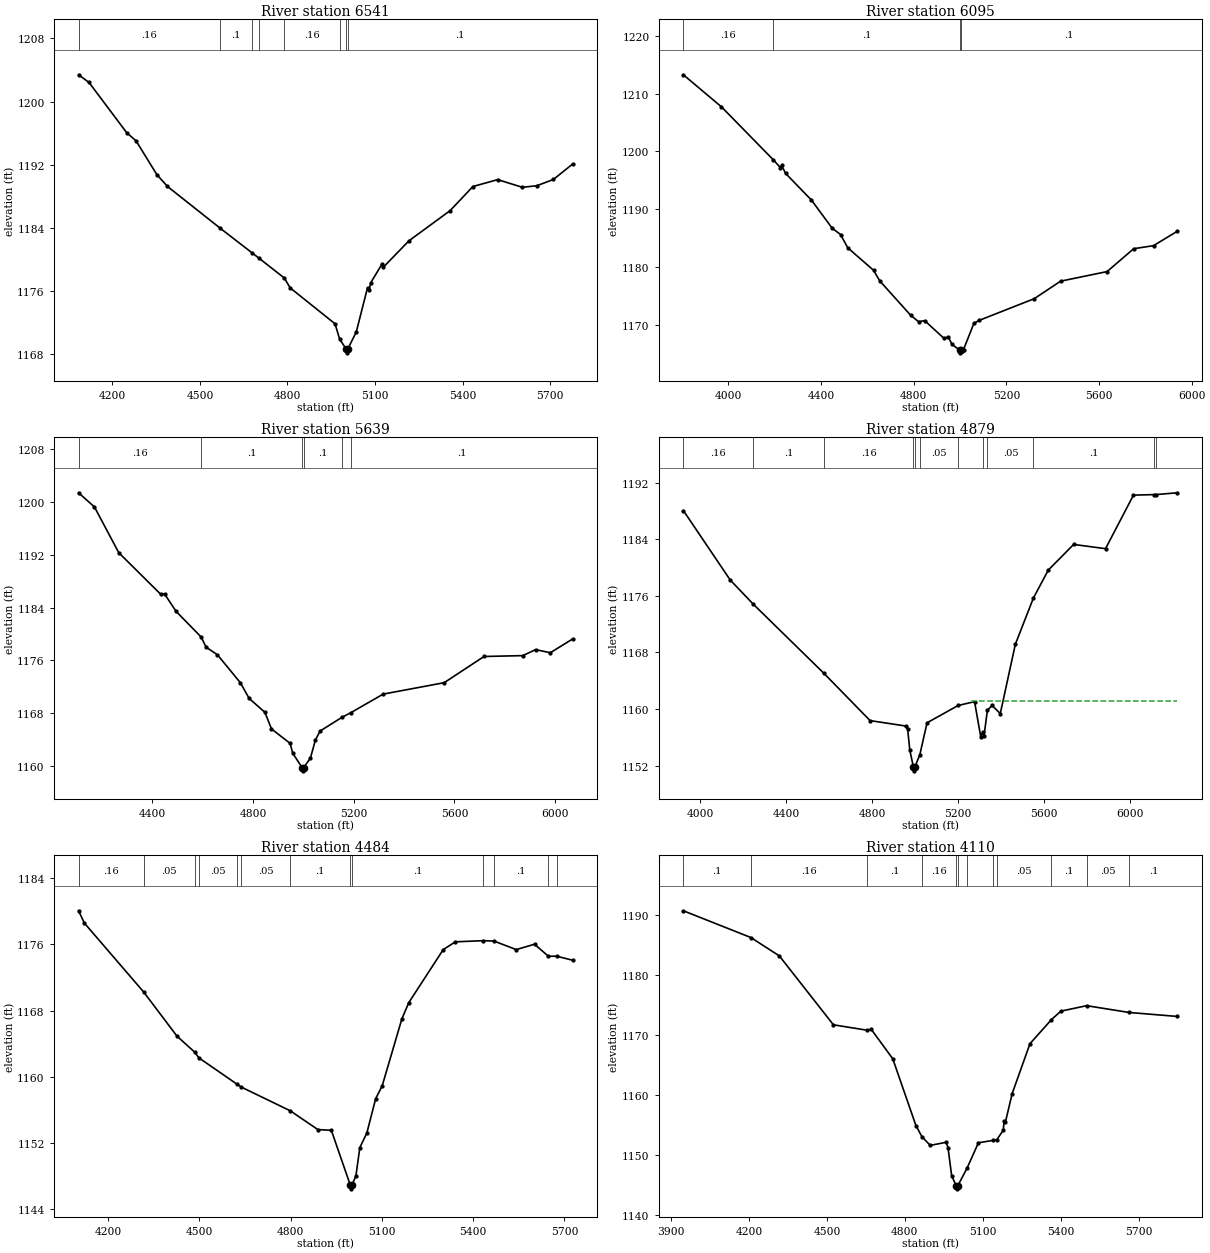
Type RM Length L Ch R = 1 ,6541    ,446,446,446
BEGIN DESCRIPTION:
UNT 1035 IN LATR 14.0
END DESCRIPTION:
XS GIS Cut Line= 4
      2921911.37     10095068.35      2921312.46     10094724.62
      2920937.46     10094641.29      2920510.57     10095088.99
#Sta/Elev= 30
    4084 1203.39  4119.8 1202.42  4249.2 1196.05  4280.9 1195.04  4352.5 1190.75
  4388.7 1189.26  4568.8 1183.99  4679.9 1180.82    4702 1180.19  4789.3 1177.67
  4809.4 1176.42    4963 1171.88    4979 1169.93    5001  1168.7  5003.7  1168.2
    5007  1168.7    5036 1170.85  5074.4 1176.44  5079.5 1176.18  5085.9  1177.1
  5123.1 1179.38  5128.2 1179.02  5216.4 1182.38  5357.6  1186.2  5435.7 1189.25
  5520.6 1190.12  5605.2 1189.15  5654.9 1189.35  5711.5 1190.14  5777.3 1192.09
#Mann= 8 ,-1 , 0
    4084     .16       0  4568.8      .1       0  4679.9     .16       0
    4702      .1       0  4789.3     .16       0    4979      .1       0
    5001     .07       0    5007      .1       0
Bank Sta=5001,5007
XS Rating Curve= 0 ,0
Exp/Cntr=0.3,0.1

Type RM Length L Ch R = 1 ,6095    ,456,456,456
BEGIN DESCRIPTION:
UNT 1035 IN LATR 13.0
END DESCRIPTION:
XS GIS Cut Line= 4
      2922265.62     10094667.35      2921598.91     10094333.99
      2920979.12     10094203.79      2920532.34     10094811.62
#Sta/Elev= 30
  3805.3 1213.27  3969.8 1207.72  4192.9 1198.58  4224.2  1197.2  4229.8 1197.58
  4246.6  1196.2  4358.4 1191.57  4447.8  1186.7  4484.1 1185.61  4514.9 1183.32
  4626.4 1179.42  4653.3 1177.58  4786.2 1171.65  4820.7 1170.52  4847.5 1170.69
  4929.2 1167.68  4949.7 1167.84  4965.2 1166.58  4997.8 1165.62  5000.5 1165.12
  5003.8 1165.62  5015.1 1165.69  5059.8 1170.23  5082.5 1170.74  5320.5  1174.5
  5434.2 1177.53  5634.8 1179.19  5749.7 1183.15  5835.4 1183.68  5938.4 1186.18
#Mann= 4 ,-1 , 0
  3805.3     .16       0  4192.9      .1       0  4997.8     .07       0
  5003.8      .1       0
Bank Sta=4997.8,5003.8
XS Rating Curve= 0 ,0
Exp/Cntr=0.3,0.1

Type RM Length L Ch R = 1 ,5639    ,760,760,760
BEGIN DESCRIPTION:
UNT 1035 IN LATR 12.0
END DESCRIPTION:
XS GIS Cut Line= 4
      2922062.49     10094104.84      2921447.87     10093813.16
      2921041.62     10093792.33      2920630.15     10094563.18
#Sta/Elev= 30
  4107.8 1201.39  4170.9 1199.24  4267.4 1192.31  4433.3 1186.03  4449.2 1186.06
  4494.7 1183.43  4594.4 1179.53  4613.9    1178  4659.3 1176.83  4750.3 1172.59
    4785 1170.22  4847.6 1168.11  4873.6  1165.6  4947.7 1163.41  4957.8 1161.92
  4994.8 1159.75  4997.6 1159.25  5000.8 1159.75  5027.8 1161.14  5047.9 1163.92
  5066.4 1165.28  5152.4 1167.34  5189.3 1168.08    5317 1170.88  5559.2 1172.61
  5717.1 1176.58  5870.8 1176.71    5922 1177.62  5980.5 1177.15  6068.7 1179.23
#Mann= 6 ,-1 , 0
  4107.8     .16       0  4594.4      .1       0  4994.8     .07       0
  5000.8      .1       0  5152.4     .16       0  5189.3      .1       0
Bank Sta=4994.8,5000.8
XS Rating Curve= 0 ,0
Exp/Cntr=0.3,0.1

Type RM Length L Ch R = 1 ,4879    ,395,395,395
BEGIN DESCRIPTION:
UNT 1035 IN LATR 11.0
END DESCRIPTION:
XS GIS Cut Line= 5
      2921906.23     10093761.11        2921401.     10093052.74
      2921052.04     10093052.74      2920765.58     10092896.49
      2920032.33     10092735.28
#Sta/Elev= 30
  3923.1 1188.05    4141 1178.23  4247.6 1174.83  4574.5  1165.1  4791.1 1158.36
  4955.7  1157.6  4965.7 1157.14  4975.7 1154.15  4992.7 1151.76  4995.5 1151.26
  4998.7 1151.76  5022.3 1153.55  5055.7 1158.05  5200.5  1160.5  5276.5 1161.04
  5305.7 1156.01  5313.8 1156.74  5320.2 1156.12  5336.1  1159.8  5358.1  1160.5
  5396.1 1159.35  5466.1 1169.15    5550 1175.68  5619.1 1179.63  5737.1 1183.26
  5885.3 1182.66  6015.1 1190.23  6111.7  1190.3    6118  1190.3  6219.2 1190.56
#Mann= 12 ,-1 , 0
  3923.1     .16       0  4247.6      .1       0  4574.5     .16       0
  4992.7     .07       0  4998.7     .16       0  5022.3     .05       0
  5200.5      .1       0  5313.8     .16       0  5336.1     .05       0
    5550      .1       0  6111.7     .05       0    6118      .1       0
#XS Ineff= 2 , 0
                          5262.5         1161.14
Permanent Ineff=
       T       T
Bank Sta=4992.7,4998.7
XS Rating Curve= 0 ,0
Exp/Cntr=0.3,0.1

Type RM Length L Ch R = 1 ,4484    ,374,374,374
BEGIN DESCRIPTION:
UNT 1035 IN LATR 10.0
END DESCRIPTION:
XS GIS Cut Line= 4
      2921927.01      10093292.3      2921437.46     10092766.29
      2921098.91     10092573.58      2920583.34     10092573.58
#Sta/Elev= 30
    4103 1180.06  4122.2 1178.57  4317.2 1170.24  4426.6 1164.91  4484.6 1162.99
  4498.6 1162.29  4623.1 1159.13  4638.5 1158.75  4798.7  1155.9  4889.5 1153.63
  4933.8 1153.54  4995.7 1146.97  4998.4 1146.47  5001.7 1146.97  5014.5 1148.01
  5027.5 1151.46  5050.5 1153.21  5079.4 1157.35    5101 1158.92  5165.8 1167.02
  5188.6 1168.98  5301.6 1175.37  5341.6 1176.31  5433.3 1176.45  5468.5  1176.4
  5541.6 1175.37  5601.6 1176.02  5647.1 1174.57  5674.3 1174.57  5726.7 1174.09
#Mann= 13 ,-1 , 0
    4103     .16       0  4317.2     .05       0  4484.6      .1       0
  4498.6     .05       0  4623.1      .1       0  4638.5     .05       0
  4798.7      .1       0  4995.7     .07       0  5001.7      .1       0
  5433.3     .05       0  5468.5      .1       0  5647.1     .05       0
  5674.3      .1       0
Bank Sta=4995.7,5001.7
XS Rating Curve= 0 ,0
Exp/Cntr=0.3,0.1

Type RM Length L Ch R = 1 ,4110    ,397,397,397
BEGIN DESCRIPTION:
UNT 1035 IN LATR 9.0
END DESCRIPTION:
XS GIS Cut Line= 4
      2922401.01     10092115.24      2921807.25     10092432.95
      2921265.58     10092297.54      2920631.84     10092515.71
#Sta/Elev= 30
  3947.2 1190.65  4207.1  1186.2  4316.8 1183.14  4524.9 1171.68  4655.7 1170.77
  4670.9 1170.91  4753.4 1166.03  4842.6 1154.92  4865.7 1153.07  4897.7 1151.62
  4959.5 1152.14  4966.3 1151.17  4980.1  1146.6  4997.7 1144.89  5000.5 1144.39
  5003.7 1144.89  5040.3 1147.91  5083.2 1152.05    5141 1152.46  5153.8 1152.54
    5179 1154.16  5181.9 1155.61  5187.2  1155.5  5213.1 1160.23  5281.7 1168.54
  5363.9 1172.52  5400.5 1173.95  5499.9 1174.86  5663.9 1173.73  5849.2 1173.07
#Mann= 12 ,-1 , 0
  3947.2      .1       0  4207.1     .16       0  4655.7      .1       0
  4865.7     .16       0  4997.7     .07       0  5003.7     .16       0
  5040.3     .05       0    5141      .1       0  5153.8     .05       0
  5363.9      .1       0  5499.9     .05       0  5663.9      .1       0
Bank Sta=4997.7,5003.7
XS Rating Curve= 0 ,0
Exp/Cntr=0.3,0.1

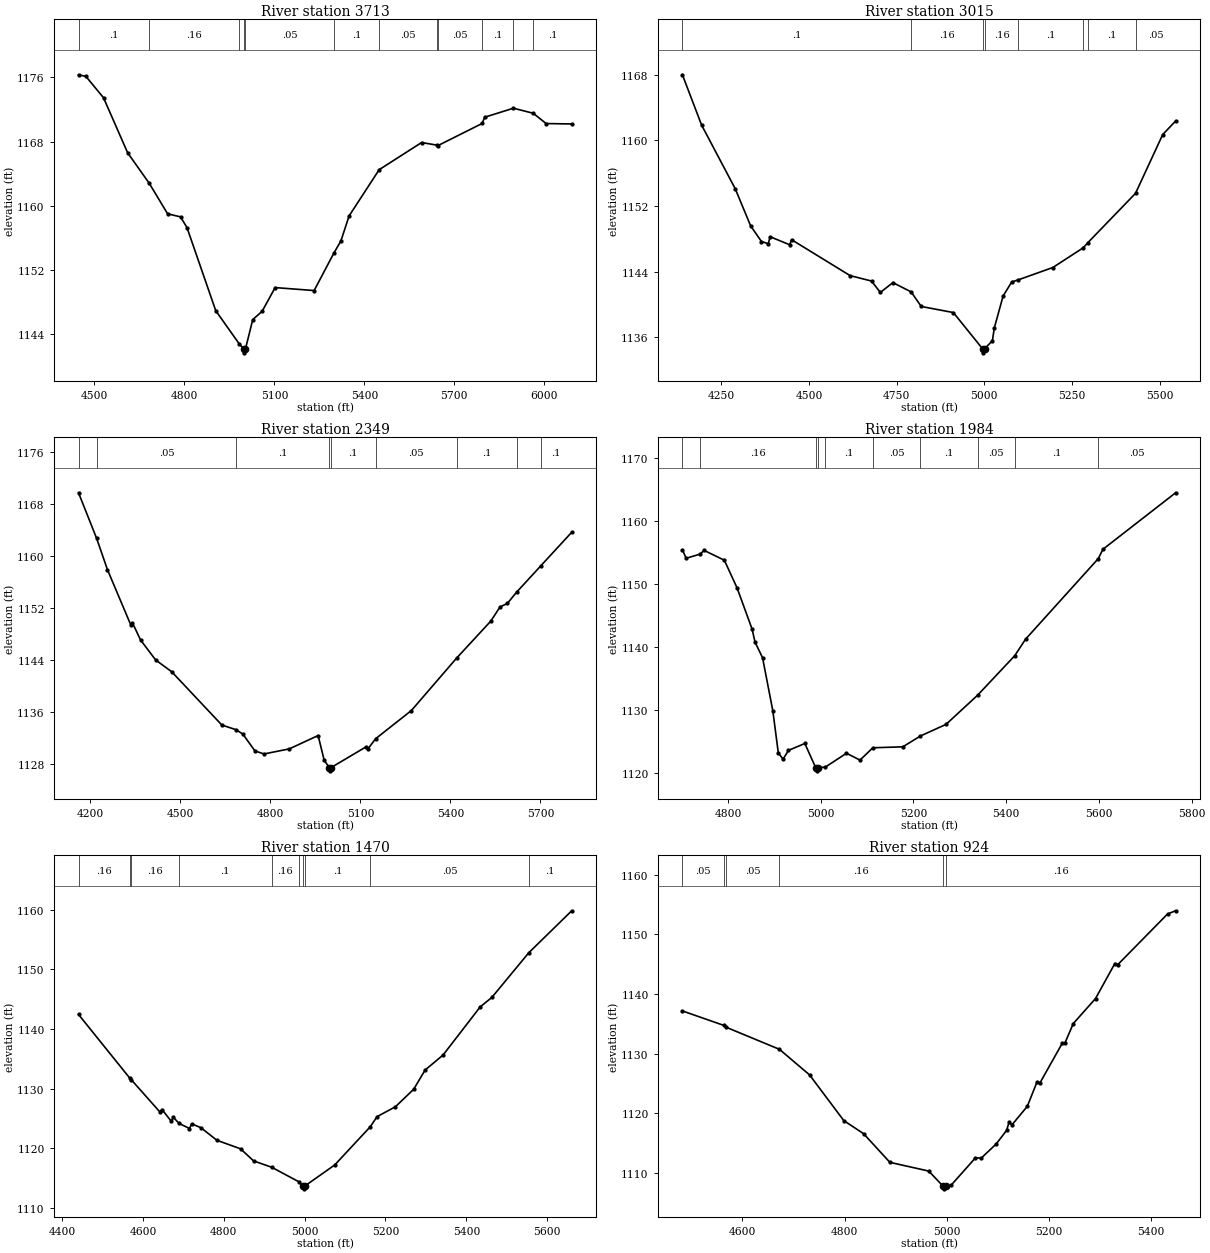
Type RM Length L Ch R = 1 ,3713    ,698,698,698
BEGIN DESCRIPTION:
UNT 1035 IN LATR 8.0
END DESCRIPTION:
XS GIS Cut Line= 3
      2921947.88     10091688.16      2920979.12     10092250.66
      2920505.19     10092474.61
#Sta/Elev= 30
  4446.9 1176.31  4471.5 1176.11  4530.3 1173.45  4610.6 1166.61  4682.8  1162.8
  4743.9 1159.01    4787 1158.63  4808.5  1157.3  4904.5 1146.95  4982.1 1142.86
  4997.6 1142.21  5000.3 1141.71  5003.6 1142.21  5027.9 1145.85  5059.1 1146.88
  5102.4 1149.83  5232.5 1149.46    5298  1154.1  5321.8 1155.64  5349.1 1158.75
  5449.3  1164.5  5590.8 1167.88  5642.7 1167.55  5644.4 1167.48  5792.5 1170.25
  5801.2 1171.03    5897 1172.15    5963 1171.52    6006 1170.24  6091.3 1170.19
#Mann= 12 ,-1 , 0
  4446.9      .1       0  4682.8     .16       0  4982.1     .05       0
  4997.6    .035       0  5003.6     .05       0    5298      .1       0
  5449.3     .05       0  5642.7      .1       0  5644.4     .05       0
  5792.5      .1       0    5897     .05       0    5963      .1       0
Bank Sta=4997.6,5003.6
XS Rating Curve= 0 ,0
Exp/Cntr=0.3,0.1

Type RM Length L Ch R = 1 ,3015    ,666,666,666
BEGIN DESCRIPTION:
UNT 1035 IN LATR 6.0
END DESCRIPTION:
XS GIS Cut Line= 3
      2921749.94     10091313.16       2920713.5     10091693.37
      2920505.14     10091912.14
#Sta/Elev= 30
  4139.4 1167.99  4194.2 1161.85  4290.1 1154.09  4333.9 1149.58  4364.7 1147.67
  4384.2  1147.4  4389.6 1148.25  4445.2 1147.27  4450.6 1147.89  4617.6 1143.51
  4678.6 1142.85  4703.7 1141.46  4739.5 1142.66  4791.4 1141.53  4820.4 1139.75
  4911.9 1139.01    4995  1134.6  4997.8  1134.1    5001  1134.6  5023.2 1135.58
  5028.5 1137.11  5053.7 1141.03  5078.3 1142.74  5097.2    1143  5195.5  1144.5
  5282.4 1146.91  5295.4 1147.53  5431.2 1153.54  5508.8 1160.71  5545.5 1162.35
#Mann= 8 ,-1 , 0
  4139.4      .1       0  4791.4     .16       0    4995     .07       0
    5001     .16       0  5097.2      .1       0  5282.4     .05       0
  5295.4      .1       0  5431.2     .05       0
Bank Sta=4995,5001
XS Rating Curve= 0 ,0
Exp/Cntr=0.3,0.1

Type RM Length L Ch R = 1 ,2349    ,365,365,365
BEGIN DESCRIPTION:
UNT 1035 IN LATR 5.0
END DESCRIPTION:
XS GIS Cut Line= 3
      2921744.76     10091042.33       2920588.5     10090953.79
      2920114.57     10091052.74
#Sta/Elev= 30
  4160.4 1169.69  4220.6 1162.71    4257 1157.87  4335.3 1149.33  4340.3 1149.71
  4367.3 1147.09  4417.4 1144.03    4471 1142.22  4638.1 1134.04  4686.3 1133.31
  4708.3 1132.64  4748.4 1130.07  4778.5  1129.6    4863 1130.38    4959 1132.43
  4979.1 1128.65  4996.1 1127.51  4998.9 1127.01  5002.1 1127.51  5119.4 1130.71
  5124.4 1130.34  5150.4 1131.93  5269.9 1136.27  5420.3  1144.3  5534.6    1150
  5565.3 1152.17  5589.8 1152.71  5620.3 1154.42  5700.4 1158.44  5804.2 1163.63
#Mann= 9 ,-1 , 0
  4160.4      .1       0  4220.6     .05       0  4686.3      .1       0
  4996.1     .07       0  5002.1      .1       0  5150.4     .05       0
  5420.3      .1       0  5620.3     .05       0  5700.4      .1       0
Bank Sta=4996.1,5002.1
XS Rating Curve= 0 ,0
Exp/Cntr=0.3,0.1

Type RM Length L Ch R = 1 ,1984    ,514,514,514
BEGIN DESCRIPTION:
UNT 1035 IN LATR 4.0
END DESCRIPTION:
XS GIS Cut Line= 3
      2921161.43     10090495.44       2920963.5     10090599.62
      2920145.78     10090792.33
#Sta/Elev= 30
  4701.6 1155.48  4709.6 1154.12  4740.1 1154.79  4748.1 1155.38  4792.1 1153.81
  4819.8 1149.35  4851.9 1142.85  4858.2 1140.79  4874.5 1138.29  4896.7 1129.82
  4908.4 1123.17  4918.7 1122.15  4930.4 1123.56  4965.7 1124.65  4989.1  1120.8
  4991.8  1120.3  4995.1  1120.8    5010  1120.9  5055.5  1123.1  5084.6 1122.01
  5112.4 1123.97    5177 1124.12  5214.9 1125.84  5270.2 1127.69  5338.4 1132.34
  5418.2  1138.6  5441.8 1141.25  5598.8 1154.08  5608.5 1155.54  5765.4 1164.54
#Mann= 10 ,-1 , 0
  4701.6      .1       0  4740.1     .16       0  4989.1     .07       0
  4995.1     .16       0    5010      .1       0  5112.4     .05       0
  5214.9      .1       0  5338.4     .05       0  5418.2      .1       0
  5598.8     .05       0
Bank Sta=4989.1,4995.1
XS Rating Curve= 0 ,0
Exp/Cntr=0.3,0.1

Type RM Length L Ch R = 1 ,1470    ,546,546,546
BEGIN DESCRIPTION:
UNT 1035 IN LATR 3.0
END DESCRIPTION:
XS GIS Cut Line= 3
      2921119.73     10089969.42       2920338.5     10090344.41
      2920104.72     10090609.35
#Sta/Elev= 30
  4440.7 1142.43  4567.5 1131.76  4571.4 1131.48  4641.7 1126.11  4647.2  1126.5
  4669.8 1124.56  4675.4 1125.19  4689.1 1124.19  4715.1 1123.32  4720.7  1124.1
  4743.3 1123.46  4783.1 1121.34  4841.4 1119.92  4873.7 1117.89  4918.4 1116.83
  4986.3 1114.37    4995 1113.71  4997.7 1113.21    5001 1113.71  5074.4 1117.21
  5162.3 1123.61  5179.2 1125.31  5224.5 1126.96  5269.8  1129.9  5297.9 1133.11
  5342.4 1135.63  5434.4 1143.71  5462.9 1145.27  5554.3 1152.76  5660.6  1159.8
#Mann= 10 ,-1 , 0
  4440.7     .16       0  4567.5      .1       0  4571.4     .16       0
  4689.1      .1       0  4918.4     .16       0  4986.3      .1       0
    4995     .07       0    5001      .1       0  5162.3     .05       0
  5554.3      .1       0
Bank Sta=4995,5001
XS Rating Curve= 0 ,0
Exp/Cntr=0.3,0.1

Type RM Length L Ch R = 1 ,924     ,382,382,382
BEGIN DESCRIPTION:
UNT 1035 IN LATR 2.0
END DESCRIPTION:
XS GIS Cut Line= 4
      2921104.13     10089610.03      2920744.75      10089714.2
      2920385.37      10089651.7      2920187.43     10089542.31
#Sta/Elev= 30
  4482.7 1137.14  4563.3 1134.73  4568.5  1134.4  4672.5 1130.71  4731.4 1126.43
  4798.5 1118.76  4837.3 1116.56  4888.7 1111.76  4964.7  1110.3  4992.2 1107.82
  4994.9 1107.32  4998.2 1107.82    5008 1107.88  5056.1 1112.51  5067.6 1112.48
  5096.7 1114.84    5117 1117.11  5122.2 1118.58  5127.2 1118.01  5157.6 1121.15
  5176.7 1125.26  5181.8 1124.99  5225.8 1131.69  5231.5 1131.82  5247.6 1135.03
  5291.1 1139.22  5328.9 1145.09  5334.6  1144.9    5432 1153.39  5447.8 1153.93
#Mann= 6 ,-1 , 0
  4482.7     .05       0  4563.3     .16       0  4568.5     .05       0
  4672.5     .16       0  4992.2     .07       0  4998.2     .16       0
Bank Sta=4992.2,4998.2
XS Rating Curve= 0 ,0
Exp/Cntr=0.3,0.1

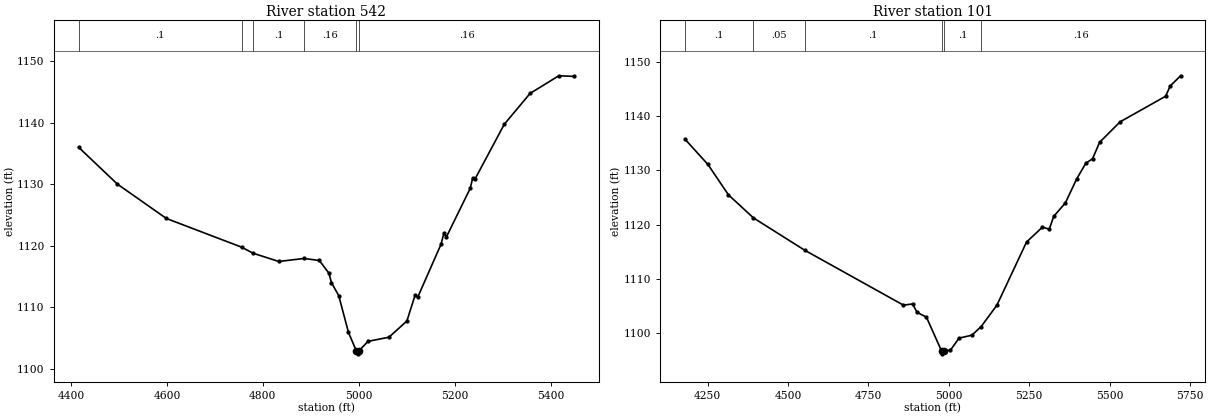
Type RM Length L Ch R = 1 ,542     ,441,441,441
BEGIN DESCRIPTION:
Mapping XS a109d68e
END DESCRIPTION:
XS GIS Cut Line= 3
       2921153.6     10089498.85      2920789.04     10089290.52
      2920184.84     10089394.69
#Sta/Elev= 30
    4416 1135.98  4496.8 1129.99    4599  1124.4  4755.7 1119.74  4779.7 1118.75
  4833.3 1117.41  4885.7  1117.9  4917.7 1117.57  4937.9 1115.49    4943 1113.97
  4958.2 1111.86  4978.5 1105.87  4994.8 1102.89  4997.6 1102.39  5000.8 1102.89
  5019.1 1104.42  5062.8 1105.09  5100.3 1107.73  5117.6 1111.99  5122.7 1111.57
  5171.3 1120.18  5177.5 1122.03  5182.5 1121.37  5232.2 1129.29  5237.3 1130.91
  5242.4 1130.83  5303.3 1139.72  5357.1 1144.74  5416.9 1147.61    5449 1147.51
#Mann= 6 ,-1 , 0
    4416      .1       0  4755.7     .05       0  4779.7      .1       0
  4885.7     .16       0  4994.8     .07       0  5000.8     .16       0
Bank Sta=4994.8,5000.8
XS Rating Curve= 0 ,0
Exp/Cntr=0.3,0.1

Type RM Length L Ch R = 1 ,101     ,0,0,0
BEGIN DESCRIPTION:
UNT 1035 IN LATR 1.0
END DESCRIPTION:
XS GIS Cut Line= 4
      2921202.22     10089450.24       2920681.4     10088915.52
       2920556.4     10088887.75      2920122.93     10089394.04
#Sta/Elev= 30
    4180 1135.75  4250.9 1131.12  4314.6 1125.51  4392.5 1121.24  4552.5 1115.25
  4859.1 1105.12  4887.3 1105.35  4901.4 1103.79  4930.5 1102.91  4977.7 1096.63
  4980.4 1096.13  4983.7 1096.63  5005.1  1096.8  5031.9 1099.03  5071.7 1099.57
  5100.7 1101.17  5149.6 1105.11  5241.8 1116.78  5291.2 1119.53  5312.5 1119.16
  5326.3 1121.52  5362.5    1124  5397.7 1128.44  5426.2 1131.34  5447.1 1132.16
    5469  1135.2  5532.7 1138.98  5674.3 1143.71  5688.6 1145.62    5721 1147.49
#Mann= 6 ,-1 , 0
    4180      .1       0  4392.5     .05       0  4552.5      .1       0
  4977.7     .07       0  4983.7      .1       0  5100.7     .16       0
Bank Sta=4977.7,4983.7
XS Rating Curve= 0 ,0
Exp/Cntr=0.3,0.1

Chan Stop Cuts=-1
Use User Specified Reach Order=0
Composite Channel Slope=5