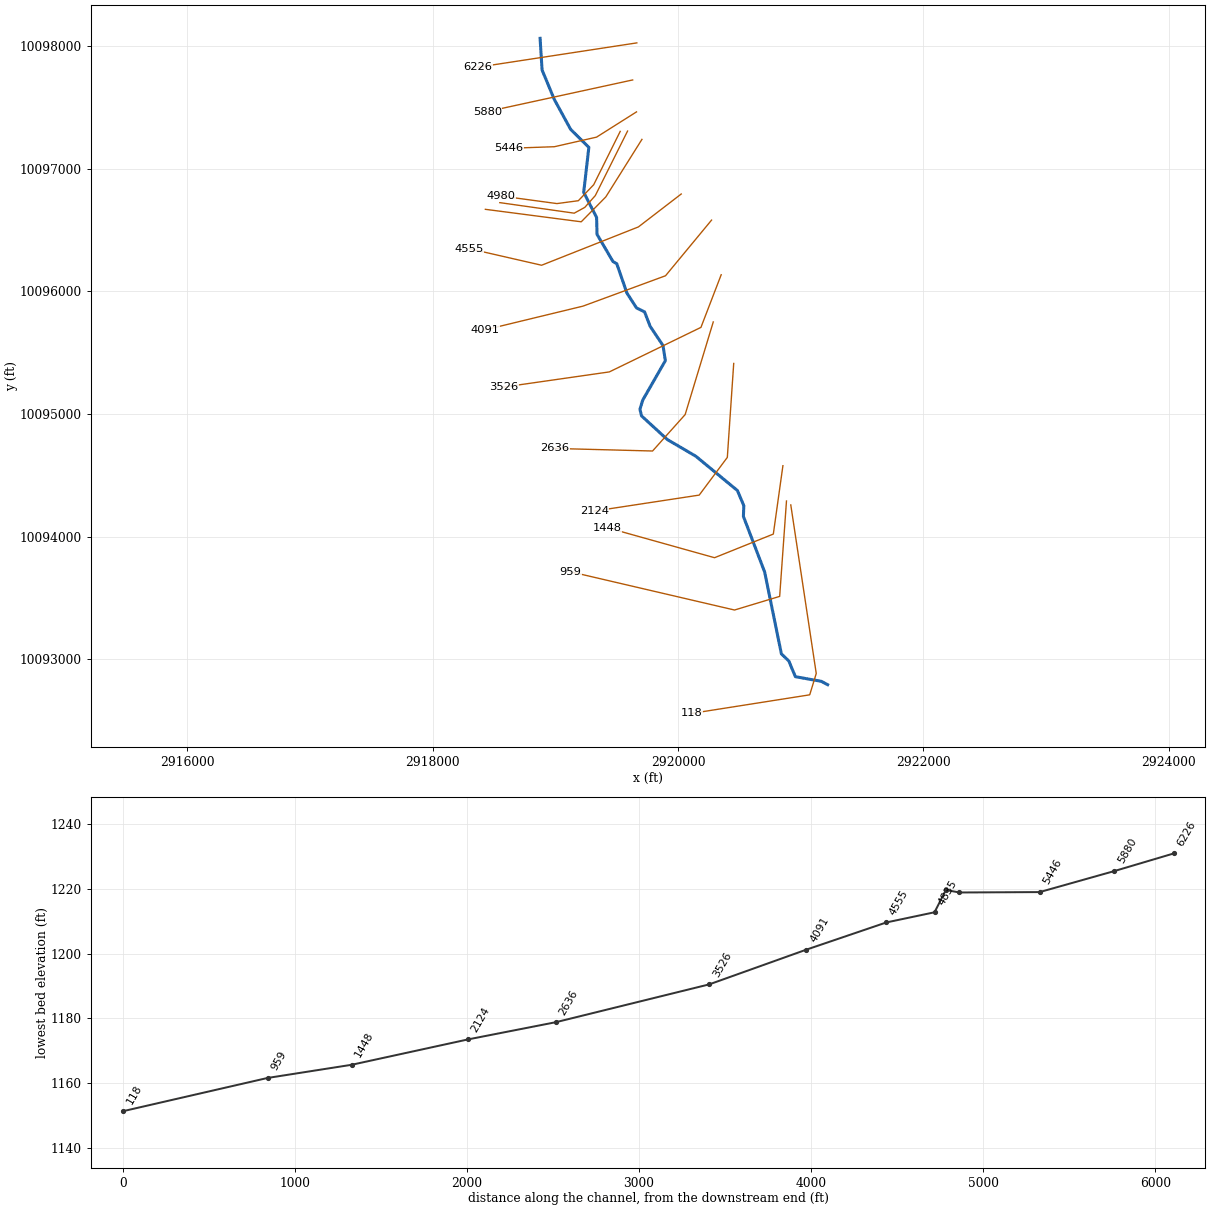
--- UNT 0036 IN LATR.prj (project) ---

Proj Title=UNT 1036 IN LATR Base Level Engineering
Current Plan=p01
Default Exp/Contr=0.3,0.1
English Units
Geom File=g01
Flow File=f01
Plan File=p01
BEGIN DESCRIPTION:
UNT 1036 IN LATR
END DESCRIPTION:

--- UNT 0036 IN LATR.p01 (plan) ---

Plan Title=Multiple Run
Short Identifier=Multiple
Geom File=g01
Flow File=f01
Subcritical Flow
K Sum by GR= 0
Std Step Tol= 0.01
Critical Tol= 0.01
Num of Std Step Trials= 20
Max Error Tol= 0.3
Flow Tol Ratio= 0.001
Split Flow NTrial= 30
Split Flow Tol= 0.02
Split Flow Ratio= 0.02
Log Output Level= 0
Friction Slope Method= 1
Unsteady Friction Slope Method= 2
Unsteady Bridges Friction Slope Method= 1
Parabolic Critical Depth
Global Vel Dist=  1 , 1 , 1
Global Log Level= 0
CheckData=True
Encroach Param= -1, 0, 0, 0
BEGIN DESCRIPTION:
Multiple Run
END DESCRIPTION:

--- UNT 0036 IN LATR.f01 (steady flow) ---

Flow Title=Multiple
Number of Profiles=7
Profile Names=10-year,25-year,50-year,1pct_min,100-year,1pct_plu,500-year
River Rch & RM= UNT 1036 IN LATR,Reach-1,6226
     790    1140    1442    1336    1807    2444    2848
River Rch & RM= UNT 1036 IN LATR,Reach-1,4980
    1022    1492    1902    1774    2399    3245    3834
Boundary for River Rch & Prof#=UNT 1036 IN LATR,Reach-1,1
Up Type=0
Dn Type=3
Dn Slope=0.005
Boundary for River Rch & Prof#=UNT 1036 IN LATR,Reach-1,2
Up Type=0
Dn Type=3
Dn Slope=0.005
Boundary for River Rch & Prof#=UNT 1036 IN LATR,Reach-1,3
Up Type=0
Dn Type=3
Dn Slope=0.005
Boundary for River Rch & Prof#=UNT 1036 IN LATR,Reach-1,4
Up Type=0
Dn Type=3
Dn Slope=0.005
Boundary for River Rch & Prof#=UNT 1036 IN LATR,Reach-1,5
Up Type=0
Dn Type=3
Dn Slope=0.005
Boundary for River Rch & Prof#=UNT 1036 IN LATR,Reach-1,6
Up Type=0
Dn Type=3
Dn Slope=0.005
Boundary for River Rch & Prof#=UNT 1036 IN LATR,Reach-1,7
Up Type=0
Dn Type=3
Dn Slope=0.005

--- UNT 0036 IN LATR.g01 (geometry) ---

Geom Title=Existing Conditions

River Reach=UNT 1036 IN LATR,Reach-1
Reach XY= 30
      2918874.81     10098062.34      2918891.02     10097804.60
      2918990.44     10097564.55      2919123.40     10097320.97
      2919272.27     10097173.70      2919230.25     10096807.03
      2919335.36     10096602.49      2919338.93     10096464.67
      2919468.47     10096243.73      2919500.11     10096224.57
      2919582.60     10095985.96      2919660.97     10095864.72
      2919726.34     10095833.00      2919771.83     10095715.13
      2919876.85     10095558.05      2919895.83     10095434.98
      2919711.00     10095112.65      2919688.86     10095038.45
      2919701.43     10094985.05      2919912.04     10094791.98
      2920144.58     10094655.66      2920483.44     10094376.18
      2920535.24     10094252.76      2920532.13     10094165.35
      2920705.21     10093712.38      2920841.75     10093045.02
      2920902.77     10092986.11      2920955.60     10092858.98
      2921167.21     10092821.04      2921218.47     10092793.73

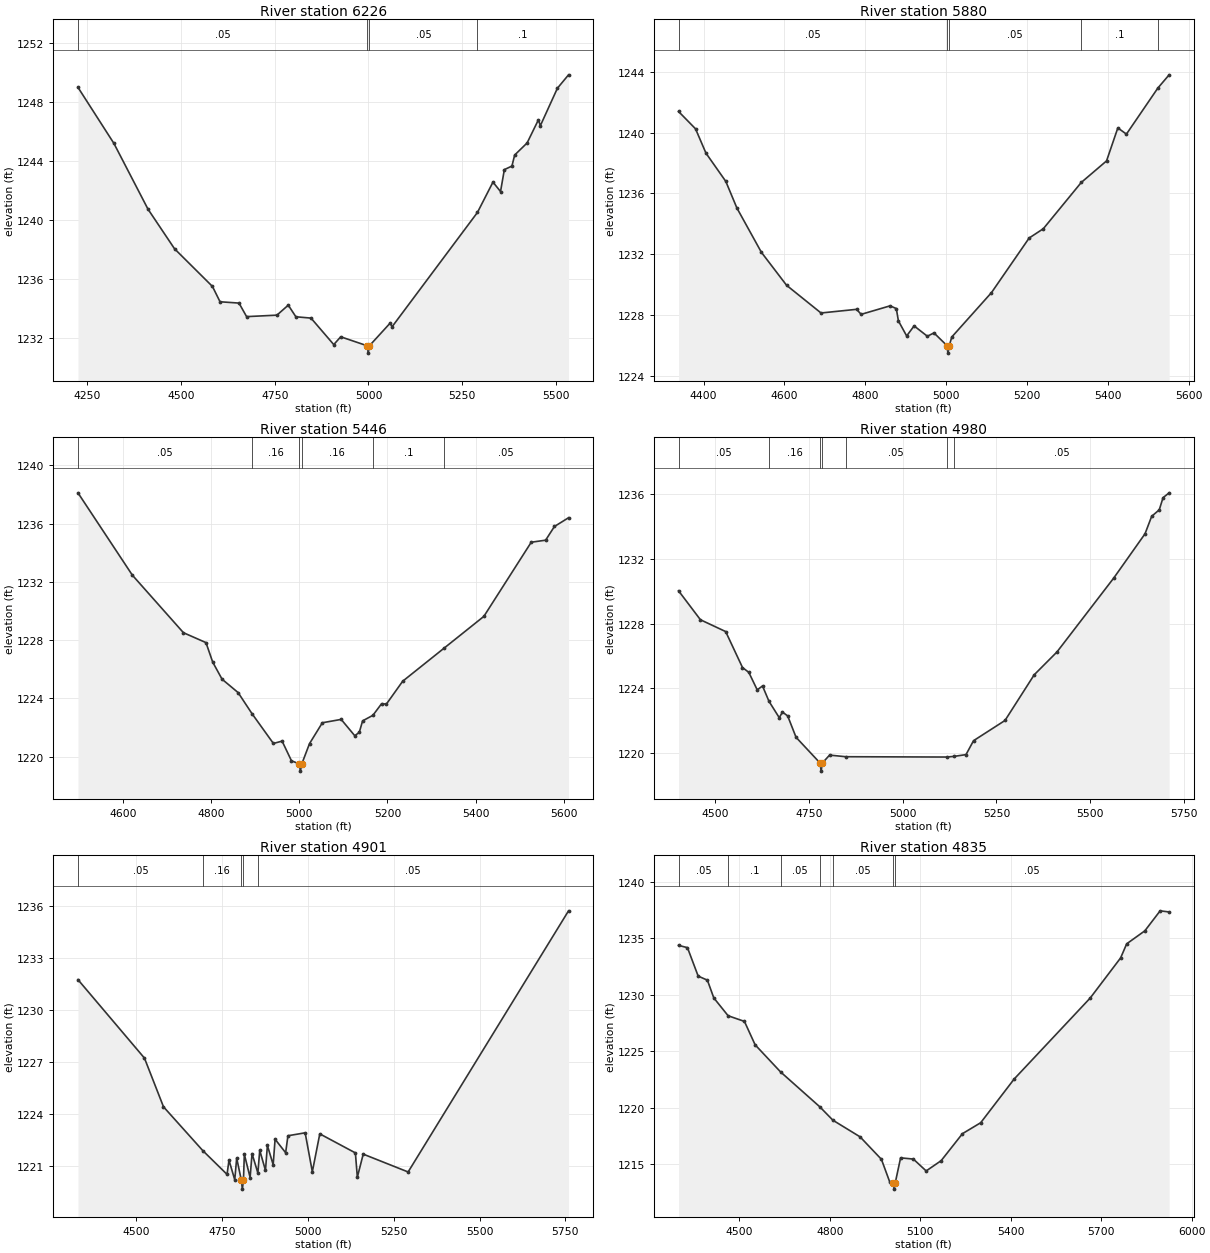
Type RM Length L Ch R = 1,6226,346,346,346
BEGIN DESCRIPTION:
UNT 1036 IN LATR 8.0
END DESCRIPTION:
XS GIS Cut Line= 2
      2919663.35     10098025.26      2918369.09     10097827.35
#Sta/Elev= 30
  4224.6 1249.01  4320.6 1245.20  4411.6 1240.73  4482.4 1238.04  4583.6 1235.48
  4603.8 1234.44  4654.4 1234.35  4674.7 1233.43  4755.6 1233.53  4785.9 1234.21
  4806.2 1233.42  4846.6 1233.33  4907.3 1231.53  4925.9 1232.06  4996.5 1231.45
  4999.2 1230.95  5002.5 1231.45  5057.8 1232.99  5062.9 1232.74  5290.8 1240.51
  5332.2 1242.57  5352.4 1241.93  5362.6 1243.42  5382.8 1243.66  5390.1 1244.41
  5423.3 1245.23  5453.6 1246.81  5458.6 1246.40  5504.2 1248.95  5533.9 1249.86
#Mann=4,-1,0
  4224.6    0.05       0  4996.5    0.04       0  5002.5    0.05       0
  5290.8     0.1       0
Bank Sta=4996.5,5002.5
Exp/Cntr=0.3,0.1

Type RM Length L Ch R = 1,5880,434,434,434
BEGIN DESCRIPTION:
Mapping XS b846d368
END DESCRIPTION:
XS GIS Cut Line= 2
      2919629.51     10097723.18      2918444.53     10097465.35
#Sta/Elev= 30
  4338.1 1241.39  4380.1 1240.25  4405.9 1238.65  4455.0 1236.79  4482.4 1235.04
  4542.9 1232.13  4605.2 1229.96  4690.3 1228.14  4778.2 1228.38  4789.5 1228.05
  4861.1 1228.61  4876.4 1228.43  4881.6 1227.62  4902.0 1226.63  4920.4 1227.29
  4953.2 1226.61  4969.5 1226.83  5001.4 1226.00  5004.1 1225.50  5007.4 1226.00
  5013.5 1226.56  5111.7 1229.48  5204.8 1233.07  5239.8 1233.68  5333.5 1236.72
  5396.1 1238.14  5424.0 1240.31  5445.2 1239.90  5522.9 1242.93  5550.8 1243.80
#Mann=5,-1,0
  4338.1    0.05       0  5001.4   0.035       0  5007.4    0.05       0
  5333.5     0.1       0  5522.9    0.05       0
Bank Sta=5001.4,5007.4
Exp/Cntr=0.3,0.1

Type RM Length L Ch R = 1,5446,466,466,466
BEGIN DESCRIPTION:
UNT 1036 IN LATR 7.0
END DESCRIPTION:
XS GIS Cut Line= 4
      2919660.72     10097462.76      2919335.20     10097257.03
      2918991.45     10097178.90      2918616.48     10097165.88
#Sta/Elev= 30
  4497.9 1238.11  4621.3 1232.46  4737.2 1228.51  4788.3 1227.83  4803.6 1226.49
  4824.8 1225.32  4861.2 1224.40  4892.8 1222.95  4941.2 1220.91  4961.0 1221.07
  4982.2 1219.72  4999.7 1219.51  5002.4 1219.01  5005.7 1219.51  5023.2 1220.90
  5052.3 1222.33  5095.0 1222.56  5125.8 1221.44  5136.0 1221.67  5143.6 1222.46
  5166.9 1222.84  5186.7 1223.64  5197.5 1223.61  5234.5 1225.18  5327.6 1227.43
  5418.6 1229.63  5526.1 1234.72  5558.7 1234.86  5578.7 1235.80  5610.7 1236.40
#Mann=6,-1,0
  4497.9    0.05       0  4892.8    0.16       0  4999.7    0.07       0
  5005.7    0.16       0  5166.9     0.1       0  5327.6    0.05       0
Bank Sta=4999.7,5005.7
Exp/Cntr=0.3,0.1

Type RM Length L Ch R = 1,4980,79,79,79
BEGIN DESCRIPTION:
Mapping XS 1f383928
END DESCRIPTION:
XS GIS Cut Line= 5
      2919527.93     10097303.94      2919311.76     10096869.01
      2919186.76     10096738.80      2919012.29     10096715.36
      2918552.43     10096777.72
#Sta/Elev= 30
  4403.4 1230.03  4461.7 1228.24  4528.9 1227.51  4573.7 1225.29  4590.5 1224.99
  4612.9 1223.91  4627.0 1224.15  4644.3 1223.20  4671.6 1222.19  4680.1 1222.54
  4694.0 1222.30  4716.3 1220.98  4780.3 1219.39  4783.1 1218.89  4786.3 1219.39
  4805.6 1219.88  4848.5 1219.78  5117.0 1219.76  5136.8 1219.80  5168.8 1219.91
  5188.9 1220.77  5272.7 1222.02  5350.4 1224.84  5411.0 1226.25  5562.3 1230.82
  5645.5 1233.55  5663.2 1234.63  5683.4 1235.03  5693.5 1235.78  5709.7 1236.08
#Mann=7,-1,0
  4403.4    0.05       0  4644.3    0.16       0  4780.3   0.033       0
  4786.3    0.16       0  4848.5    0.05       0  5117.0     0.1       0
  5136.8    0.05       0
Bank Sta=4780.3,4786.3
Exp/Cntr=0.3,0.1

Type RM Length L Ch R = 1,4901,66,66,66
BEGIN DESCRIPTION:
Mapping XS 9bef3eb5
END DESCRIPTION:
XS GIS Cut Line= 5
      2919587.79     10097306.48      2919324.79     10096780.47
      2919238.85     10096684.11      2919152.91     10096637.24
      2918546.17     10096723.17
#Sta/Elev= 30
  4331.2 1231.75  4524.8 1227.22  4580.2 1224.41  4694.7 1221.88  4765.2 1220.51
  4770.8 1221.33  4787.6 1220.20  4793.2 1221.45  4806.9 1220.16  4809.7 1219.66
  4812.9 1220.16  4815.5 1221.67  4832.3 1220.33  4837.9 1221.71  4854.9 1220.59
  4860.3 1221.90  4877.0 1220.74  4882.6 1222.18  4899.4 1221.07  4905.0 1222.54
  4935.7 1221.76  4942.4 1222.74  4992.5 1222.91  5013.4 1220.66  5035.1 1222.85
  5138.7 1221.75  5144.4 1220.35  5161.5 1221.68  5292.2 1220.65  5759.1 1235.72
#Mann=5,-1,0
  4331.2    0.05       0  4694.7    0.16       0  4806.9   0.033       0
  4812.9    0.16       0  4854.9    0.05       0
Bank Sta=4806.9,4812.9
Exp/Cntr=0.3,0.1

Type RM Length L Ch R = 1,4835,280,280,280
BEGIN DESCRIPTION:
UNT 1036 IN LATR 6.0
END DESCRIPTION:
XS GIS Cut Line= 4
      2919704.97     10097238.76      2919410.72     10096770.05
      2919210.20     10096566.92      2918428.92     10096668.49
#Sta/Elev= 30
  4298.6 1234.36  4328.2 1234.16  4363.7 1231.64  4394.3 1231.28  4415.5 1229.71
  4463.0 1228.13  4517.1 1227.63  4552.5 1225.56  4636.8 1223.16  4766.5 1220.08
  4810.5 1218.88  4900.5 1217.41  4971.3 1215.42  4999.5 1213.37  5010.7 1213.28
  5013.4 1212.78  5016.7 1213.28  5034.9 1215.55  5077.3 1215.44  5119.7 1214.39
  5169.4 1215.30  5240.0 1217.69  5300.5 1218.66  5411.5 1222.53  5663.6 1229.70
  5764.4 1233.25  5784.6 1234.50  5844.8 1235.65  5895.5 1237.42  5925.3 1237.32
#Mann=7,-1,0
  4298.6    0.05       0  4463.0     0.1       0  4636.8    0.05       0
  4766.5     0.1       0  4810.5    0.05       0  5010.7    0.04       0
  5016.7    0.05       0
Bank Sta=5010.7,5016.7
Exp/Cntr=0.3,0.1

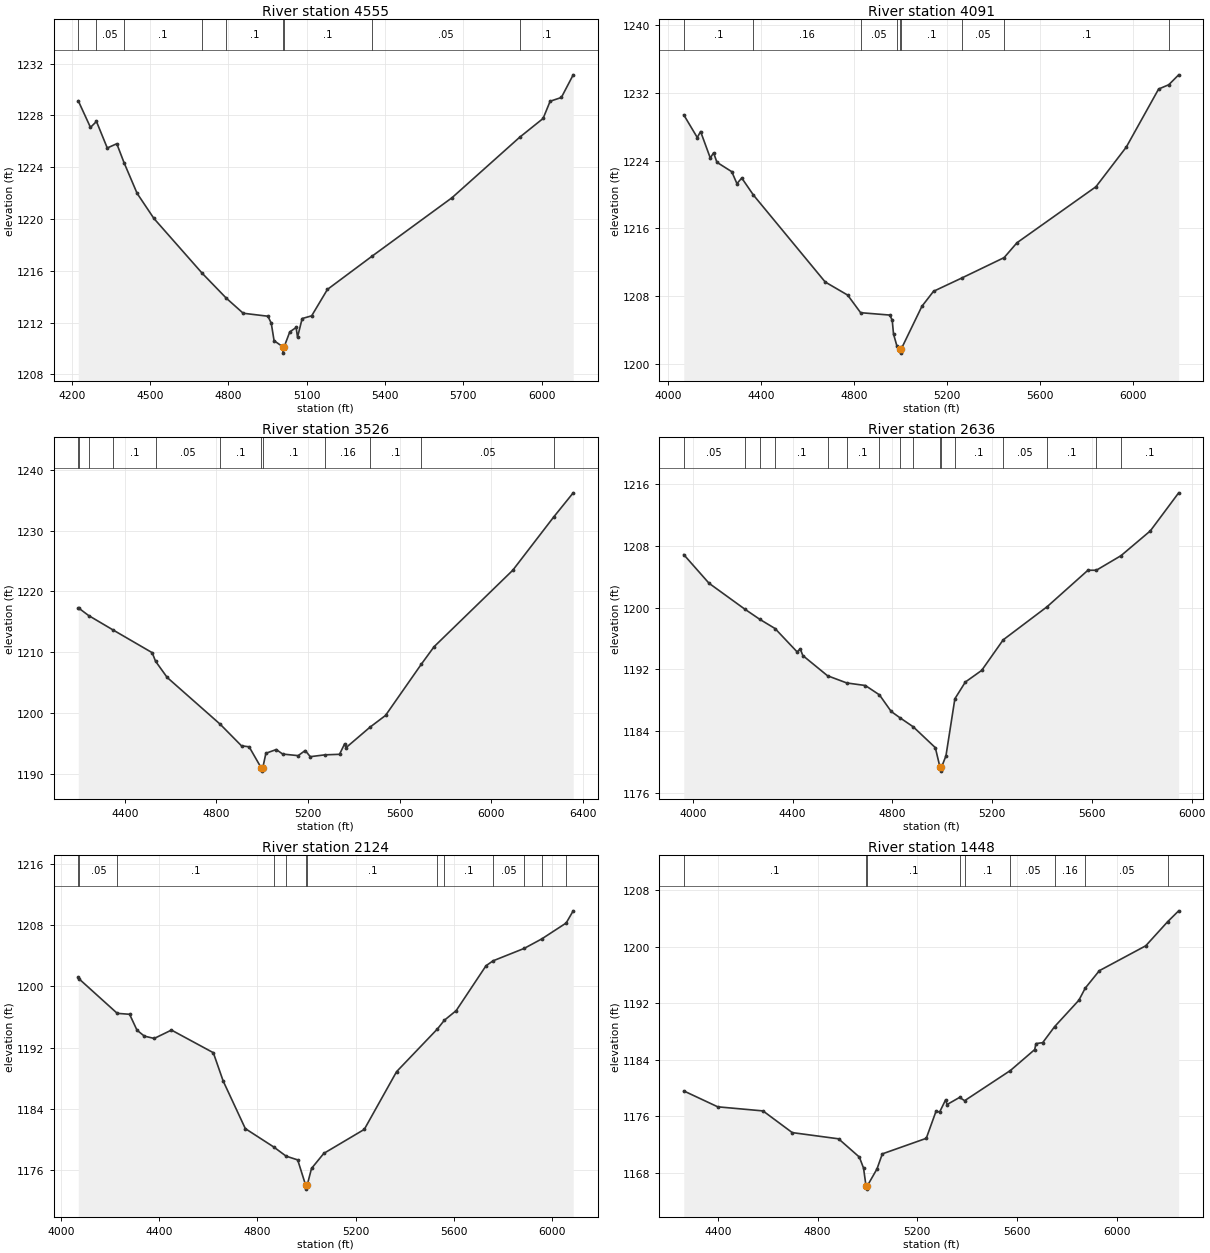
Type RM Length L Ch R = 1,4555,464,464,464
BEGIN DESCRIPTION:
UNT 1036 IN LATR 5.0
END DESCRIPTION:
XS GIS Cut Line= 4
      2920025.30     10096793.48      2919676.35     10096525.26
      2918887.29     10096212.76      2918296.12     10096348.18
#Sta/Elev= 30
  4225.4 1229.12  4272.1 1227.07  4295.0 1227.53  4336.4 1225.48  4372.8 1225.81
  4400.6 1224.35  4450.6 1221.98  4515.0 1220.04  4699.8 1215.81  4792.4 1213.88
  4856.9 1212.72  4951.6 1212.49  4964.4 1211.95  4975.2 1210.60  5008.0 1210.14
  5010.7 1209.64  5014.0 1210.14  5035.3 1211.28  5059.6 1211.62  5065.0 1210.87
  5082.7 1212.31  5119.1 1212.52  5179.5 1214.56  5350.0 1217.12  5656.6 1221.64
  5915.1 1226.30  6005.4 1227.76  6032.3 1229.09  6075.3 1229.38  6120.7 1231.13
#Mann=9,-1,0
  4225.4     0.1       0  4295.0    0.05       0  4400.6     0.1       0
  4699.8    0.05       0  4792.4     0.1       0  5008.0    0.07       0
  5014.0     0.1       0  5350.0    0.05       0  5915.1     0.1       0
Bank Sta=5008,5014
Exp/Cntr=0.3,0.1

Type RM Length L Ch R = 1,4091,565,565,565
BEGIN DESCRIPTION:
Mapping XS 91eff3fd
END DESCRIPTION:
XS GIS Cut Line= 4
      2920272.66     10096580.86      2919897.26     10096127.08
      2919224.86     10095879.57      2918424.55     10095685.68
#Sta/Elev= 30
  4068.4 1229.43  4126.5 1226.75  4140.8 1227.46  4182.5 1224.33  4196.8 1224.94
  4211.1 1223.82  4274.9 1222.71  4297.1 1221.30  4317.9 1221.96  4368.0 1219.95
  4676.8 1209.67  4773.5 1208.12  4829.2 1206.04  4954.4 1205.76  4965.1 1205.16
  4970.7 1203.52  4985.2 1202.11  4998.1 1201.76  5000.9 1201.26  5004.1 1201.76
  5092.9 1206.80  5142.8 1208.57  5264.4 1210.14  5446.4 1212.55  5501.8 1214.31
  5841.4 1220.93  5972.0 1225.62  6111.0 1232.48  6154.8 1232.99  6197.3 1234.16
#Mann=9,-1,0
  4068.4     0.1       0  4368.0    0.16       0  4829.2    0.05       0
  4985.2     0.1       0  4998.1    0.07       0  5004.1     0.1       0
  5264.4    0.05       0  5446.4     0.1       0  6154.8    0.05       0
Bank Sta=4998.1,5004.1
Exp/Cntr=0.3,0.1

Type RM Length L Ch R = 1,3526,890,890,890
BEGIN DESCRIPTION:
Mapping XS a16740a7
END DESCRIPTION:
XS GIS Cut Line= 4
      2920351.01     10096135.30      2920186.02     10095706.31
      2919439.36     10095343.30      2918577.25     10095219.55
#Sta/Elev= 30
  4197.1 1217.22  4200.8 1217.22  4242.3 1216.05  4350.6 1213.65  4519.7 1209.96
  4534.4 1208.56  4585.1 1205.90  4817.0 1198.21  4909.7 1194.68  4943.0 1194.52
  4996.3 1191.03  4999.0 1190.53  5002.3 1191.03  5016.2 1193.46  5061.4 1194.07
  5089.5 1193.33  5157.1 1193.07  5187.7 1193.91  5210.0 1192.90  5273.8 1193.20
  5337.6 1193.29  5360.1 1195.02  5365.7 1194.37  5470.4 1197.73  5538.4 1199.66
  5695.5 1208.11  5750.5 1210.94  6094.0 1223.48  6272.8 1232.22  6357.9 1236.18
#Mann=12,-1,0
  4197.1    0.16       0  4200.8     0.1       0  4242.3    0.16       0
  4350.6     0.1       0  4534.4    0.05       0  4817.0     0.1       0
  4996.3    0.07       0  5002.3     0.1       0  5273.8    0.16       0
  5470.4     0.1       0  5695.5    0.05       0  6272.8     0.1       0
Bank Sta=4996.3,5002.3
Exp/Cntr=0.3,0.1

Type RM Length L Ch R = 1,2636,512,512,512
BEGIN DESCRIPTION:
UNT 1036 IN LATR 4.0
END DESCRIPTION:
XS GIS Cut Line= 4
      2920286.43     10095750.70      2920057.25     10094995.45
      2919791.62     10094698.58      2918994.71     10094719.41
#Sta/Elev= 30
  3963.3 1206.84  4064.6 1203.14  4207.9 1199.80  4267.7 1198.49  4329.4 1197.29
  4418.0 1194.27  4430.4 1194.67  4440.8 1193.80  4539.9 1191.19  4617.0 1190.26
  4691.6 1189.93  4748.1 1188.72  4795.1 1186.58  4829.6 1185.78  4883.8 1184.59
  4972.2 1181.90  4990.9 1179.37  4993.7 1178.87  4996.9 1179.37  5014.8 1180.84
  5050.6 1188.22  5092.6 1190.38  5158.0 1191.88  5244.4 1195.83  5420.2 1200.10
  5584.2 1204.82  5617.9 1204.82  5716.7 1206.70  5834.3 1209.90  5948.1 1214.82
#Mann=16,-1,0
  3963.3    0.05       0  4207.9     0.1       0  4267.7    0.05       0
  4329.4     0.1       0  4539.9    0.05       0  4617.0     0.1       0
  4748.1    0.05       0  4829.6     0.1       0  4883.8    0.16       0
  4990.9    0.07       0  4996.9    0.16       0  5050.6     0.1       0
  5244.4    0.05       0  5420.2     0.1       0  5617.9    0.05       0
  5716.7     0.1       0
Bank Sta=4990.9,4996.9
Exp/Cntr=0.3,0.1

Type RM Length L Ch R = 1,2124,676,676,676
BEGIN DESCRIPTION:
UNT 1036 IN LATR 3.0
END DESCRIPTION:
XS GIS Cut Line= 4
      2920453.08     10095412.13      2920401.00     10094646.49
      2920171.83     10094339.20      2919317.63     10094208.99
#Sta/Elev= 30
  4070.9 1201.16  4075.3 1200.92  4229.6 1196.46  4279.8 1196.34  4309.8 1194.27
  4339.9 1193.49  4380.0 1193.19  4450.2 1194.28  4620.6 1191.33  4660.7 1187.64
  4750.9 1181.43  4866.4 1179.04  4917.0 1177.84  4964.1 1177.35  4996.6 1174.04
  4999.3 1173.54  5002.6 1174.04  5020.4 1176.24  5070.4 1178.20  5235.2 1181.33
  5366.7 1188.86  5533.0 1194.43  5561.1 1195.56  5609.4 1196.82  5730.8 1202.67
  5759.4 1203.31  5886.2 1204.93  5957.8 1206.17  6057.0 1208.24  6085.7 1209.83
#Mann=13,-1,0
  4070.9     0.1       0  4075.3    0.05       0  4229.6     0.1       0
  4866.4    0.16       0  4917.0     0.1       0  4996.6    0.07       0
  5002.6     0.1       0  5533.0    0.05       0  5561.1     0.1       0
  5759.4    0.05       0  5886.2     0.1       0  5957.8    0.16       0
  6057.0     0.1       0
Bank Sta=4996.6,5002.6
Exp/Cntr=0.3,0.1

Type RM Length L Ch R = 1,1448,489,489,489
BEGIN DESCRIPTION:
UNT 1036 IN LATR 2.0
END DESCRIPTION:
XS GIS Cut Line= 4
      2920854.13     10094578.82      2920776.00     10094021.49
      2920296.83     10093828.79      2919422.63     10094073.35
#Sta/Elev= 30
  4262.5 1179.61  4398.9 1177.36  4580.7 1176.78  4698.1 1173.71  4884.1 1172.83
  4967.4 1170.25  4984.3 1168.69  4994.0 1166.21  4996.7 1165.71  5000.0 1166.21
  5038.2 1168.56  5059.7 1170.70  5236.1 1172.90  5275.3 1176.73  5289.9 1176.63
  5314.1 1178.37  5319.4 1177.68  5369.8 1178.69  5390.3 1178.23  5573.9 1182.50
  5671.4 1185.46  5676.6 1186.31  5703.5 1186.44  5751.2 1188.70  5848.9 1192.45
  5874.2 1194.15  5931.1 1196.63  6117.3 1200.15  6205.2 1203.56  6249.5 1205.10
#Mann=9,-1,0
  4262.5     0.1       0  4994.0    0.07       0  5000.0     0.1       0
  5369.8    0.05       0  5390.3     0.1       0  5573.9    0.05       0
  5751.2    0.16       0  5874.2    0.05       0  6205.2     0.1       0
Bank Sta=4994,5000
Exp/Cntr=0.3,0.1

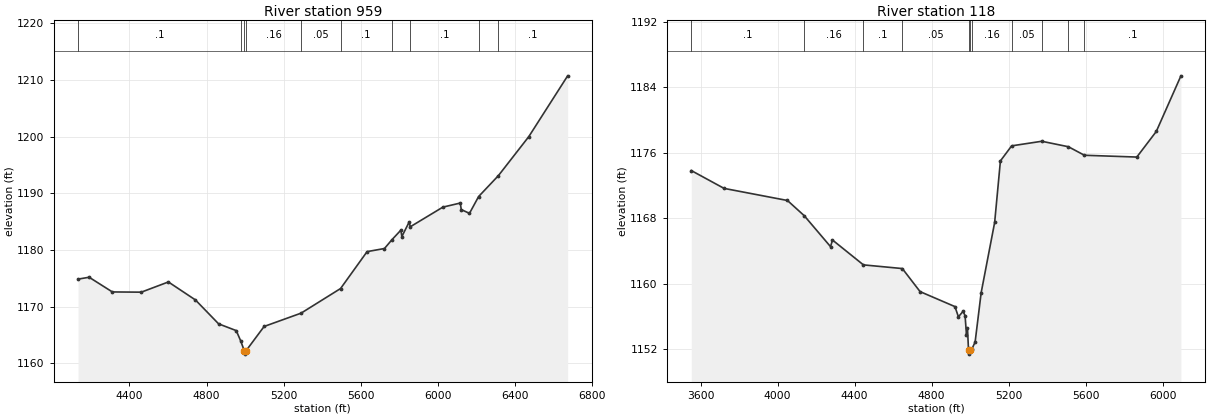
Type RM Length L Ch R = 1,959,841,841,841
BEGIN DESCRIPTION:
Mapping XS 14f93ac4
END DESCRIPTION:
XS GIS Cut Line= 4
      2920883.25     10094291.33      2920827.69     10093513.52
      2920459.63     10093402.41      2919119.33     10093714.92
#Sta/Elev= 30
  4133.2 1174.87  4190.9 1175.20  4311.3 1172.61  4461.6 1172.57  4602.0 1174.37
  4742.3 1171.20  4862.7 1166.98  4954.0 1165.79  4976.7 1164.02  4996.9 1162.14
  4999.6 1161.64  5002.9 1162.14  5098.8 1166.52  5290.7 1168.87  5495.4 1173.21
  5633.0 1179.72  5723.2 1180.27  5761.7 1181.81  5808.3 1183.51  5813.5 1182.38
  5850.9 1184.92  5857.5 1184.11  6026.2 1187.57  6116.5 1188.29  6121.6 1187.14
  6164.2 1186.47  6211.8 1189.44  6314.2 1193.12  6472.3 1200.02  6673.7 1210.73
#Mann=10,-1,0
  4133.2     0.1       0  4976.7    0.16       0  4996.9    0.07       0
  5002.9    0.16       0  5290.7    0.05       0  5495.4     0.1       0
  5761.7    0.16       0  5857.5     0.1       0  6211.8    0.05       0
  6314.2     0.1       0
Bank Sta=4996.9,5002.9
Exp/Cntr=0.3,0.1

Type RM Length L Ch R = 1,118,0,0,0
BEGIN DESCRIPTION:
UNT 1036 IN LATR 1.0
END DESCRIPTION:
XS GIS Cut Line= 4
      2920918.31     10094258.97      2921125.81     10092884.98
      2921072.53     10092711.13      2920112.06     10092559.92
#Sta/Elev= 30
  3552.0 1173.81  3722.3 1171.63  4051.6 1170.15  4138.8 1168.29  4275.3 1164.51
  4285.5 1165.32  4446.2 1162.28  4648.4 1161.83  4740.6 1159.01  4921.7 1157.18
  4939.7 1155.93  4963.8 1156.60  4974.3 1156.08  4981.6 1153.73  4986.8 1154.51
  4992.2 1151.87  4994.9 1151.37  4998.2 1151.87  5008.8 1151.94  5026.5 1152.85
  5057.9 1158.88  5128.0 1167.47  5157.9 1174.99  5216.2 1176.83  5372.7 1177.39
  5511.2 1176.72  5594.3 1175.68  5866.5 1175.46  5967.7 1178.59  6095.7 1185.39
#Mann=11,-1,0
  3552.0     0.1       0  4138.8    0.16       0  4446.2     0.1       0
  4648.4    0.05       0  4992.2   0.035       0  4998.2    0.05       0
  5008.8    0.16       0  5216.2    0.05       0  5372.7     0.1       0
  5511.2    0.05       0  5594.3     0.1       0
Bank Sta=4992.2,4998.2
Exp/Cntr=0.3,0.1

Chan Stop Cuts=-1