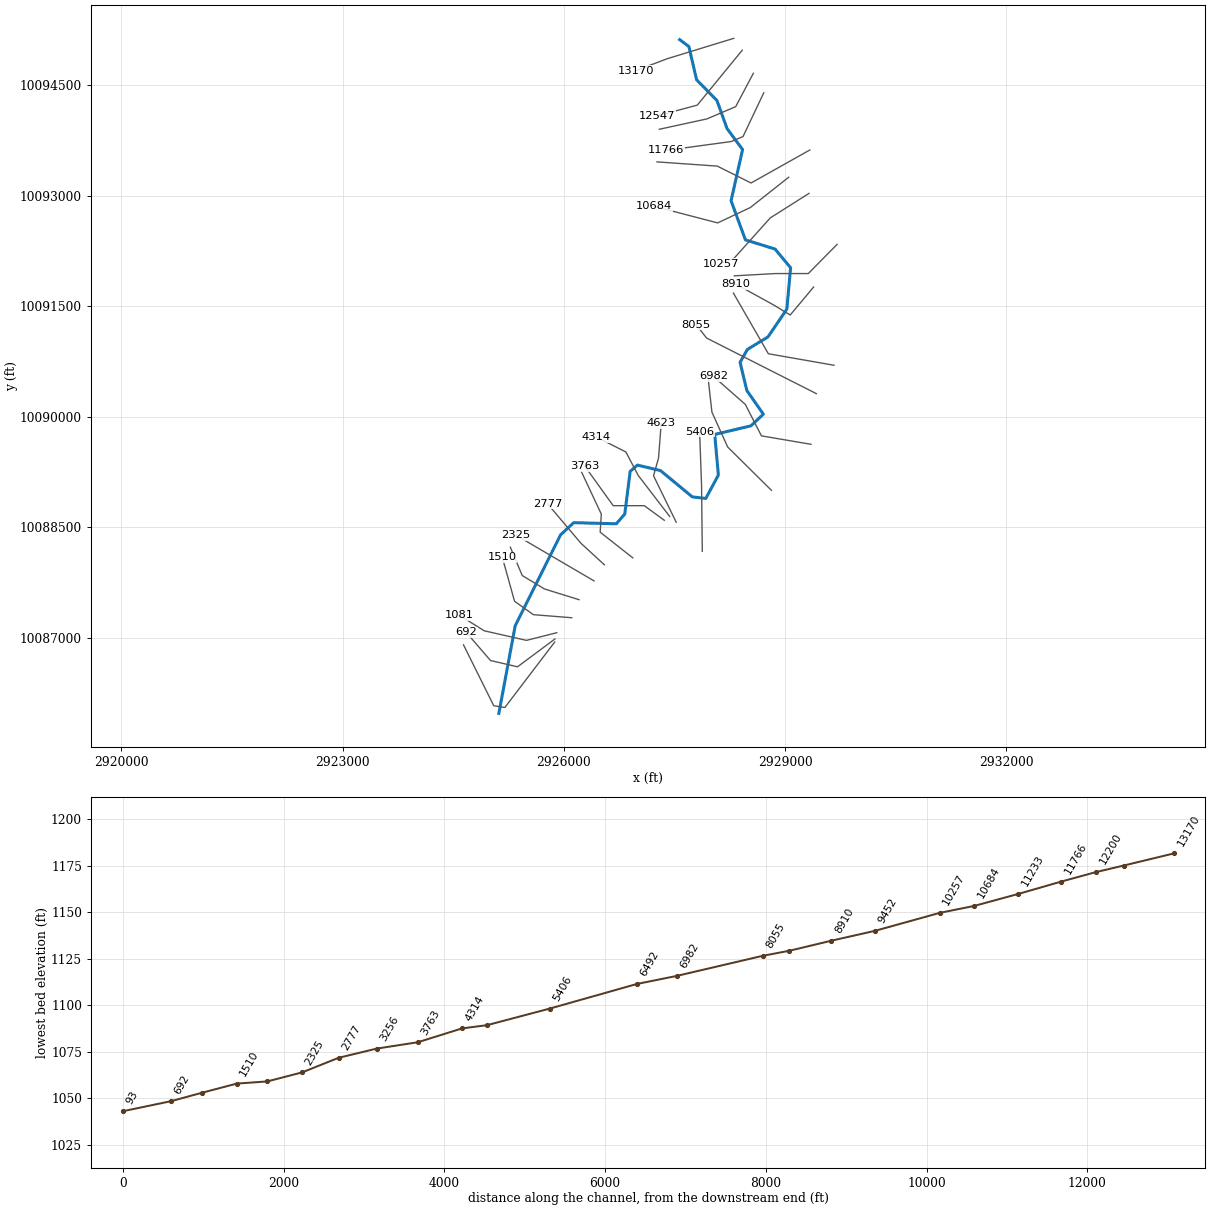
--- UNT 0037 IN LATR.prj (project) ---

Proj Title=UNT 1037 IN LATR Base Level Engineering
Current Plan=p01
Default Exp/Contr=0.3,0.1
English Units
Geom File=g01
Flow File=f01
Plan File=p01
BEGIN DESCRIPTION:
UNT 1037 IN LATR
END DESCRIPTION:

--- UNT 0037 IN LATR.p01 (plan) ---

Plan Title=Multiple Run
Short Identifier=Multiple
Geom File=g01
Flow File=f01
Subcritical Flow
K Sum by GR= 0
Std Step Tol= 0.01
Critical Tol= 0.01
Num of Std Step Trials= 20
Max Error Tol= 0.3
Flow Tol Ratio= 0.001
Split Flow NTrial= 30
Split Flow Tol= 0.02
Split Flow Ratio= 0.02
Log Output Level= 0
Friction Slope Method= 1
Unsteady Friction Slope Method= 2
Unsteady Bridges Friction Slope Method= 1
Parabolic Critical Depth
Global Vel Dist=  1 , 1 , 1
Global Log Level= 0
CheckData=True
Encroach Param= -1, 0, 0, 0
BEGIN DESCRIPTION:
Multiple Run
END DESCRIPTION:

--- UNT 0037 IN LATR.f01 (steady flow) ---

Flow Title=Multiple
Number of Profiles=7
Profile Names=10-year,25-year,50-year,1pct_min,100-year,1pct_plu,500-year
River Rch & RM= UNT 1037 IN LATR,Reach-1,13170
     935    1360    1731    1614    2182    2951    3479
River Rch & RM= UNT 1037 IN LATR,Reach-1,11233
     961    1397    1778    1655    2238    3027    3562
River Rch & RM= UNT 1037 IN LATR,Reach-1,8386
    1680    2511    3251    3075    4159    5625    6836
River Rch & RM= UNT 1037 IN LATR,Reach-1,1510
    2012    3031    3947    3753    5075    6863    8428
Boundary for River Rch & Prof#=UNT 1037 IN LATR,Reach-1,1
Up Type=0
Dn Type=3
Dn Slope=0.005
Boundary for River Rch & Prof#=UNT 1037 IN LATR,Reach-1,2
Up Type=0
Dn Type=3
Dn Slope=0.005
Boundary for River Rch & Prof#=UNT 1037 IN LATR,Reach-1,3
Up Type=0
Dn Type=3
Dn Slope=0.005
Boundary for River Rch & Prof#=UNT 1037 IN LATR,Reach-1,4
Up Type=0
Dn Type=3
Dn Slope=0.005
Boundary for River Rch & Prof#=UNT 1037 IN LATR,Reach-1,5
Up Type=0
Dn Type=3
Dn Slope=0.005
Boundary for River Rch & Prof#=UNT 1037 IN LATR,Reach-1,6
Up Type=0
Dn Type=3
Dn Slope=0.005
Boundary for River Rch & Prof#=UNT 1037 IN LATR,Reach-1,7
Up Type=0
Dn Type=3
Dn Slope=0.005

--- UNT 0037 IN LATR.g01 (geometry) ---

Geom Title=Existing Conditions

River Reach=UNT 1037 IN LATR,Reach-1
Reach XY= 30
      2927571.01     10095118.48      2927695.84     10095026.37
      2927800.28     10094574.67      2928076.12     10094292.68
      2928213.93     10093911.09      2928424.42     10093626.74
      2928268.19     10092932.17      2928462.79     10092400.75
      2928864.81     10092276.52      2929075.73     10092022.59
      2929024.52     10091460.65      2928769.17     10091084.29
      2928488.70     10090913.14      2928390.31     10090738.15
      2928482.37     10090355.40      2928706.13     10090034.95
      2928537.36     10089876.40      2928046.27     10089760.22
      2928095.93     10089208.29      2927925.03     10088890.98
      2927741.78     10088912.58      2927311.40     10089269.20
      2926998.47     10089343.73      2926899.69     10089258.35
      2926826.38     10088679.49      2926711.46     10088547.26
      2926134.15     10088562.30      2925956.46     10088398.51
      2925340.54     10087164.49      2925118.47     10085973.73

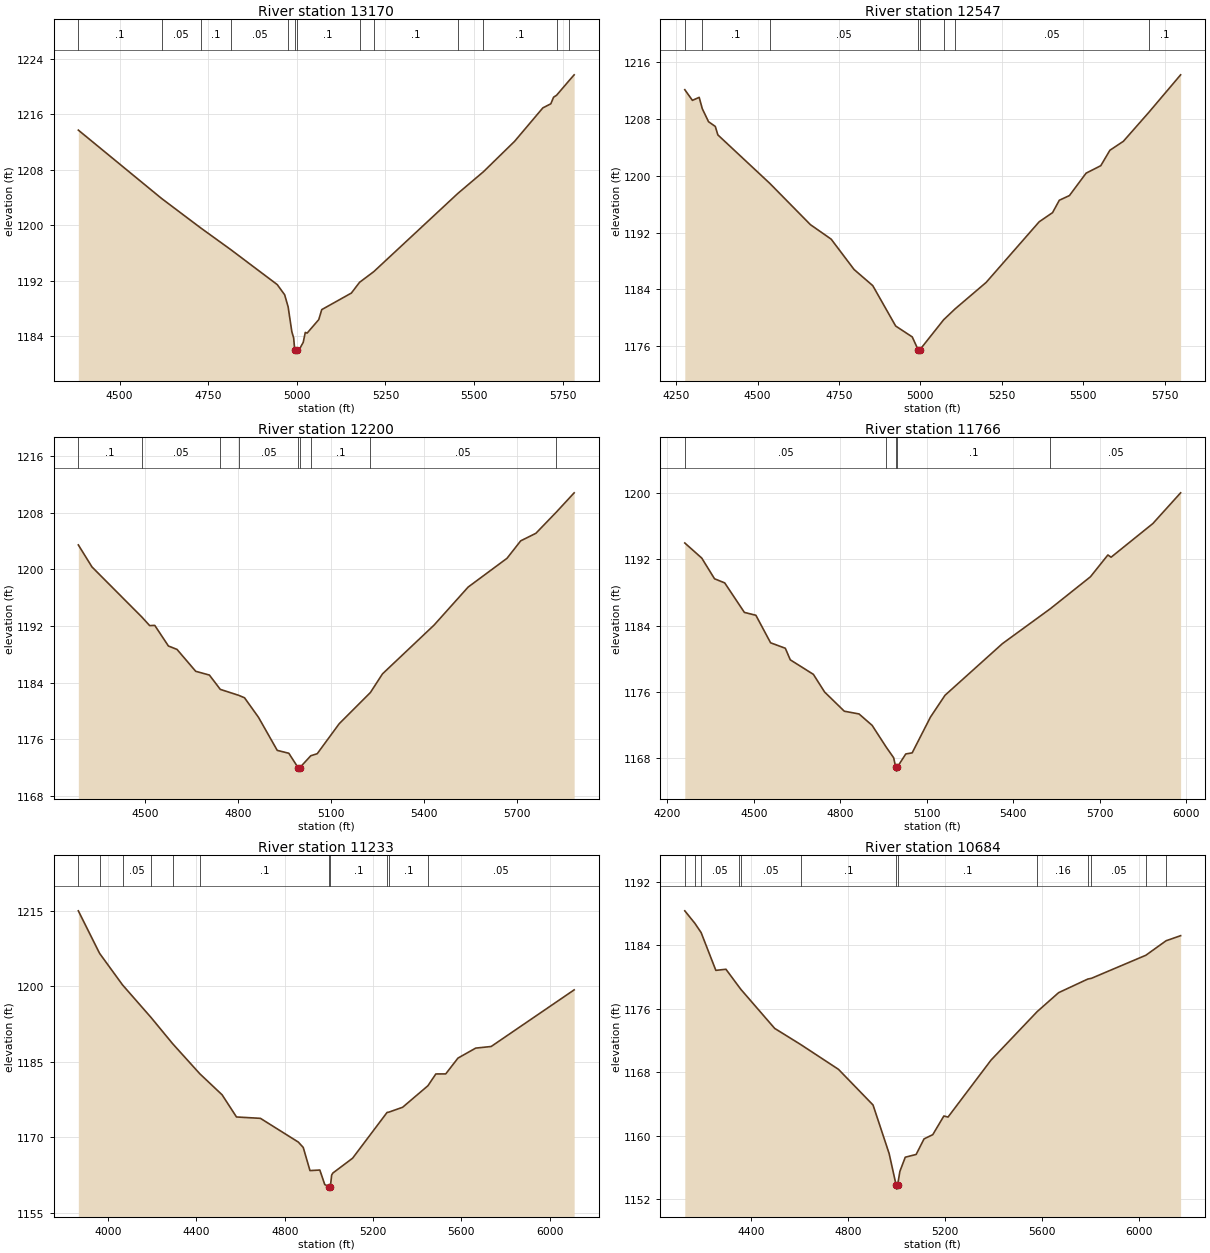
Type RM Length L Ch R = 1,13170,623,623,623
BEGIN DESCRIPTION:
UNT 1037 IN LATR 29.0
END DESCRIPTION:
XS GIS Cut Line= 3
      2928305.10     10095136.52      2927404.04     10094860.47
      2926976.94     10094699.01
#Sta/Elev= 30
  4383.6 1213.74  4618.6 1203.87  4729.2 1199.61  4813.2 1196.51  4944.9 1191.44
  4965.8 1189.97  4975.6 1188.22  4986.0 1184.65  4991.2 1183.73  4994.1 1182.05
  4996.9 1181.55  5000.1 1182.05  5007.6 1182.14  5018.1 1183.10  5024.0 1184.54
  5029.2 1184.44  5062.0 1186.39  5070.4 1187.83  5154.0 1190.22  5177.1 1191.77
  5217.4 1193.32  5454.4 1204.60  5526.8 1207.74  5614.5 1212.12  5694.3 1216.95
  5716.8 1217.54  5724.5 1218.49  5733.0 1218.77  5767.6 1220.84  5782.6 1221.72
#Mann=13,-1,0
  4383.6     0.1       0  4618.6    0.05       0  4729.2     0.1       0
  4813.2    0.05       0  4975.6     0.1       0  4994.1    0.07       0
  5000.1     0.1       0  5177.1    0.05       0  5217.4     0.1       0
  5454.4    0.05       0  5526.8     0.1       0  5733.0    0.05       0
  5767.6     0.1       0
Bank Sta=4994.1,5000.1
Exp/Cntr=0.3,0.1

Type RM Length L Ch R = 1,12547,347,347,347
BEGIN DESCRIPTION:
UNT 1037 IN LATR 28.0
END DESCRIPTION:
XS GIS Cut Line= 3
      2928419.68     10094975.08      2927810.29     10094230.26
      2927268.63     10094084.43
#Sta/Elev= 30
  4276.2 1212.09  4299.6 1210.59  4320.4 1211.01  4329.9 1209.42  4349.1 1207.59
  4369.9 1206.92  4377.8 1205.73  4537.2 1198.92  4662.1 1193.11  4725.9 1191.07
  4796.3 1186.80  4853.7 1184.53  4924.1 1178.85  4975.0 1177.32  4992.8 1175.54
  4995.6 1175.04  4998.8 1175.54  5071.4 1179.73  5106.8 1181.27  5201.9 1184.98
  5364.9 1193.51  5406.1 1194.80  5426.8 1196.54  5457.9 1197.20  5509.1 1200.35
  5554.2 1201.40  5582.2 1203.57  5623.6 1204.83  5701.6 1208.89  5799.5 1214.18
#Mann=8,-1,0
  4276.2    0.05       0  4329.9     0.1       0  4537.2    0.05       0
  4992.8   0.035       0  4998.8    0.05       0  5071.4     0.1       0
  5106.8    0.05       0  5701.6     0.1       0
Bank Sta=4992.8,4998.8
Exp/Cntr=0.3,0.1

Type RM Length L Ch R = 1,12200,434,434,434
BEGIN DESCRIPTION:
UNT 1037 IN LATR 27.0
END DESCRIPTION:
XS GIS Cut Line= 4
      2928570.72     10094662.59      2928331.12     10094209.43
      2927940.49     10094042.76      2927294.63     10093902.13
#Sta/Elev= 30
  4285.3 1203.43  4329.3 1200.32  4489.8 1193.26  4515.3 1192.04  4531.7 1192.07
  4575.7 1189.16  4603.4 1188.68  4663.7 1185.59  4707.8 1185.06  4742.9 1183.04
  4802.9 1182.19  4821.1 1181.85  4866.0 1179.10  4926.5 1174.43  4963.9 1174.02
  4993.5 1172.00  4996.2 1171.50  4999.5 1172.00  5034.6 1173.67  5055.4 1173.96
  5126.2 1178.19  5226.7 1182.59  5265.6 1185.22  5432.0 1192.11  5541.9 1197.48
  5667.2 1201.54  5711.2 1204.00  5760.3 1205.07  5824.7 1207.99  5883.6 1210.78
#Mann=9,-1,0
  4285.3     0.1       0  4489.8    0.05       0  4742.9     0.1       0
  4802.9    0.05       0  4993.5   0.035       0  4999.5    0.05       0
  5034.6     0.1       0  5226.7    0.05       0  5824.7     0.1       0
Bank Sta=4993.5,4999.5
Exp/Cntr=0.3,0.1

Type RM Length L Ch R = 1,11766,533,533,533
BEGIN DESCRIPTION:
UNT 1037 IN LATR 26.0
END DESCRIPTION:
XS GIS Cut Line= 4
      2928711.33     10094396.93      2928430.08     10093803.18
      2928268.62     10093735.47      2927388.41     10093615.68
#Sta/Elev= 30
  4260.3 1193.99  4319.2 1192.16  4363.4 1189.66  4398.8 1189.16  4467.0 1185.59
  4507.0 1185.24  4558.0 1181.91  4609.1 1181.25  4626.3 1179.85  4706.5 1178.09
  4745.5 1175.95  4813.8 1173.63  4864.8 1173.30  4910.3 1171.92  4958.9 1169.30
  4985.0 1168.00  4992.0 1166.88  4994.7 1166.38  4998.0 1166.88  5027.1 1168.46
  5049.2 1168.59  5112.7 1172.92  5163.2 1175.56  5362.4 1181.81  5528.5 1186.03
  5667.8 1189.90  5728.3 1192.54  5739.5 1192.27  5884.3 1196.34  5980.7 1200.06
#Mann=5,-1,0
  4260.3    0.05       0  4958.9     0.1       0  4992.0    0.07       0
  4998.0     0.1       0  5528.5    0.05       0
Bank Sta=4992,4998
Exp/Cntr=0.3,0.1

Type RM Length L Ch R = 1,11233,549,549,549
BEGIN DESCRIPTION:
UNT 1037 IN LATR 25.0
END DESCRIPTION:
XS GIS Cut Line= 4
      2929336.35     10093620.90      2928539.45     10093172.97
      2928081.12     10093402.14      2927263.41     10093459.43
#Sta/Elev= 30
  3865.1 1214.99  3961.4 1206.55  4065.3 1200.29  4194.5 1193.82  4292.7 1188.60
  4415.6 1182.64  4516.5 1178.47  4581.7 1174.07  4690.1 1173.80  4861.7 1169.09
  4884.1 1168.02  4914.5 1163.43  4959.2 1163.54  4981.6 1160.65  5001.0 1160.25
  5003.7 1159.75  5007.0 1160.25  5012.7 1162.53  5018.2 1162.94  5107.7 1165.89
  5263.8 1174.97  5272.5 1175.04  5334.4 1176.00  5448.9 1180.27  5484.8 1182.61
  5529.5 1182.62  5585.1 1185.76  5665.3 1187.74  5735.4 1188.06  6111.4 1199.30
#Mann=11,-1,0
  3865.1    0.05       0  3961.4     0.1       0  4065.3    0.05       0
  4194.5     0.1       0  4292.7    0.05       0  4415.6     0.1       0
  5001.0    0.07       0  5007.0     0.1       0  5263.8    0.05       0
  5272.5     0.1       0  5448.9    0.05       0
Bank Sta=5001,5007
Exp/Cntr=0.3,0.1

Type RM Length L Ch R = 1,10684,427,427,427
BEGIN DESCRIPTION:
UNT 1037 IN LATR 24.0
END DESCRIPTION:
XS GIS Cut Line= 4
      2929049.84     10093251.07      2928529.04     10092839.64
      2928086.33     10092631.30      2927226.93     10092855.27
#Sta/Elev= 30
  4128.5 1188.36  4169.9 1186.79  4195.7 1185.62  4256.3 1180.86  4297.9 1181.00
  4351.9 1178.77  4359.5 1178.46  4498.4 1173.55  4604.9 1171.53  4761.2 1168.39
  4903.4 1163.90  4969.7 1157.78  4998.5 1153.80  5001.3 1153.30  5004.5 1153.80
  5013.9 1155.53  5036.0 1157.32  5080.9 1157.67  5113.4 1159.63  5149.3 1160.16
  5194.9 1162.51  5212.2 1162.38  5389.0 1169.55  5579.0 1175.66  5667.3 1178.05
  5787.1 1179.76  5802.6 1179.86  6026.3 1182.76  6109.8 1184.59  6169.6 1185.23
#Mann=13,-1,0
  4128.5    0.05       0  4169.9     0.1       0  4195.7    0.05       0
  4351.9     0.1       0  4359.5    0.05       0  4604.9     0.1       0
  4998.5    0.07       0  5004.5     0.1       0  5579.0    0.16       0
  5787.1     0.1       0  5802.6    0.05       0  6026.3     0.1       0
  6109.8    0.05       0
Bank Sta=4998.5,5004.5
Exp/Cntr=0.3,0.1

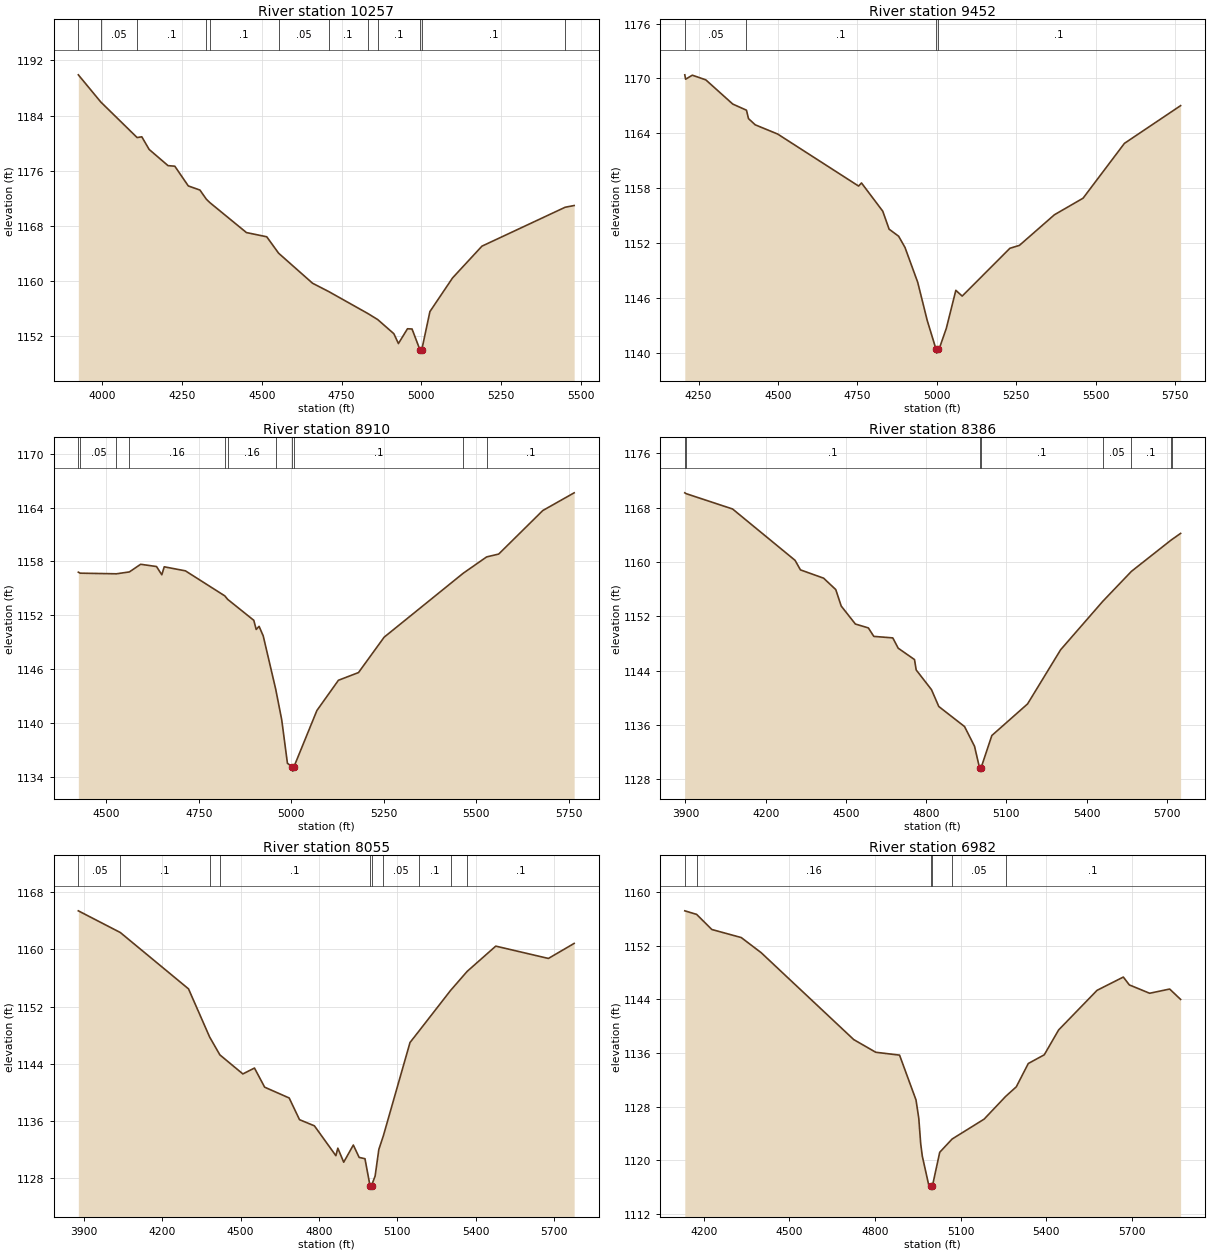
Type RM Length L Ch R = 1,10257,805,805,805
BEGIN DESCRIPTION:
UNT 1037 IN LATR 23.0
END DESCRIPTION:
XS GIS Cut Line= 4
      2929325.91     10093032.35      2928799.87     10092699.01
      2928305.08     10092146.93      2928128.00     10092079.22
#Sta/Elev= 30
  3924.9 1189.92  3995.3 1185.98  4109.1 1180.83  4123.8 1180.94  4146.8 1179.11
  4206.0 1176.76  4227.2 1176.68  4269.5 1173.82  4306.0 1173.22  4325.8 1171.91
  4336.6 1171.42  4451.7 1167.06  4515.3 1166.45  4552.5 1164.07  4658.8 1159.72
  4709.2 1158.52  4831.8 1155.34  4863.1 1154.45  4913.7 1152.40  4927.9 1150.98
  4956.3 1153.12  4970.6 1153.09  4995.2 1150.09  4997.9 1149.59  5001.2 1150.09
  5026.6 1155.61  5097.6 1160.49  5189.6 1165.09  5450.4 1170.73  5478.6 1170.98
#Mann=12,-1,0
  3924.9     0.1       0  3995.3    0.05       0  4109.1     0.1       0
  4325.8    0.05       0  4336.6     0.1       0  4552.5    0.05       0
  4709.2     0.1       0  4831.8    0.05       0  4863.1     0.1       0
  4995.2    0.07       0  5001.2     0.1       0  5450.4    0.05       0
Bank Sta=4995.2,5001.2
Exp/Cntr=0.3,0.1

Type RM Length L Ch R = 1,9452,542,542,542
BEGIN DESCRIPTION:
UNT 1037 IN LATR 21.0
END DESCRIPTION:
XS GIS Cut Line= 4
      2929706.10     10092339.62      2929315.49     10091943.80
      2928872.79     10091943.80      2928311.86     10091912.64
#Sta/Elev= 30
  4206.8 1170.39  4209.3 1169.91  4230.5 1170.35  4272.9 1169.84  4357.8 1167.19
  4400.9 1166.52  4407.3 1165.60  4428.5 1164.92  4499.2 1163.91  4753.8 1158.22
  4762.9 1158.56  4829.9 1155.47  4849.9 1153.50  4879.9 1152.73  4899.9 1151.50
  4939.9 1147.69  4969.9 1143.51  4996.9 1140.44  4999.7 1139.94  5002.9 1140.44
  5009.9 1140.65  5029.9 1142.65  5059.9 1146.81  5079.9 1146.18  5230.0 1151.41
  5260.0 1151.73  5370.2 1155.08  5460.3 1156.89  5590.5 1162.89  5767.4 1167.02
#Mann=4,-1,0
  4206.8    0.05       0  4400.9     0.1       0  4996.9    0.07       0
  5002.9     0.1       0
Bank Sta=4996.9,5002.9
Exp/Cntr=0.3,0.1

Type RM Length L Ch R = 1,8910,524,524,524
BEGIN DESCRIPTION:
UNT 1037 IN LATR 20.0
END DESCRIPTION:
XS GIS Cut Line= 4
      2929388.44     10091761.54      2929070.70     10091381.30
      2928846.74     10091516.72      2928336.34     10091797.96
#Sta/Elev= 30
  4424.3 1156.80  4429.4 1156.69  4527.3 1156.62  4562.3 1156.83  4592.7 1157.68
  4635.6 1157.43  4649.9 1156.51  4656.5 1157.40  4713.7 1156.95  4820.2 1154.16
  4828.0 1153.77  4898.5 1151.44  4905.0 1150.42  4912.8 1150.77  4924.0 1149.70
  4957.6 1143.79  4973.9 1140.38  4989.4 1135.52  5001.2 1135.14  5004.0 1134.64
  5007.2 1135.14  5069.0 1141.39  5127.2 1144.76  5181.5 1145.62  5250.8 1149.56
  5464.7 1156.69  5527.7 1158.50  5560.4 1158.82  5679.6 1163.67  5764.3 1165.64
#Mann=11,-1,0
  4424.3     0.1       0  4429.4    0.05       0  4527.3     0.1       0
  4562.3    0.16       0  4820.2     0.1       0  4828.0    0.16       0
  4957.6     0.1       0  5001.2    0.07       0  5007.2     0.1       0
  5464.7    0.05       0  5527.7     0.1       0
Bank Sta=5001.2,5007.2
Exp/Cntr=0.3,0.1

Type RM Length L Ch R = 1,8386,331,331,331
BEGIN DESCRIPTION:
UNT 1037 IN LATR 19.0
END DESCRIPTION:
XS GIS Cut Line= 3
      2929664.49     10090699.00      2928773.83     10090855.26
      2928299.87     10091678.17
#Sta/Elev= 30
  3897.6 1170.18  3902.5 1170.06  4076.3 1167.80  4309.8 1160.25  4330.1 1158.84
  4416.6 1157.62  4462.1 1155.94  4482.4 1153.52  4535.4 1150.87  4583.9 1150.30
  4604.3 1149.05  4675.3 1148.83  4695.6 1147.31  4756.5 1145.64  4762.8 1144.11
  4820.0 1141.21  4847.3 1138.73  4943.6 1135.78  4980.9 1132.88  4999.5 1129.72
  5002.2 1129.22  5005.5 1129.72  5045.6 1134.46  5179.2 1139.11  5302.8 1147.08
  5460.4 1154.21  5567.5 1158.62  5715.4 1163.21  5717.8 1163.28  5751.5 1164.21
#Mann=8,-1,0
  3897.6    0.05       0  3902.5     0.1       0  4999.5    0.07       0
  5005.5     0.1       0  5460.4    0.05       0  5567.5     0.1       0
  5715.4    0.05       0  5717.8     0.1       0
Bank Sta=4999.5,5005.5
Exp/Cntr=0.3,0.1

Type RM Length L Ch R = 1,8055,1073,1073,1073
BEGIN DESCRIPTION:
UNT 1037 IN LATR 18.0
END DESCRIPTION:
XS GIS Cut Line= 3
      2929424.88     10090313.59      2927935.29     10091068.80
      2927795.60     10091249.88
#Sta/Elev= 30
  3878.7 1165.38  4039.5 1162.35  4300.7 1154.48  4381.6 1147.75  4420.8 1145.26
  4508.7 1142.60  4553.3 1143.42  4592.2 1140.75  4686.2 1139.24  4725.8 1136.21
  4782.8 1135.35  4865.0 1131.18  4872.5 1132.23  4895.0 1130.27  4931.8 1132.67
  4954.1 1130.94  4976.4 1130.76  4995.6 1127.01  4998.4 1126.51  5001.6 1127.01
  5015.3 1128.34  5029.5 1132.05  5046.5 1133.92  5148.9 1146.99  5184.6 1148.65
  5304.0 1154.25  5367.7 1156.92  5477.3 1160.45  5678.9 1158.73  5777.5 1160.83
#Mann=10,-1,0
  3878.7    0.05       0  4039.5     0.1       0  4381.6    0.16       0
  4420.8     0.1       0  4995.6    0.07       0  5001.6     0.1       0
  5046.5    0.05       0  5184.6     0.1       0  5304.0    0.05       0
  5367.7     0.1       0
Bank Sta=4995.6,5001.6
Exp/Cntr=0.3,0.1

Type RM Length L Ch R = 1,6982,490,490,490
BEGIN DESCRIPTION:
UNT 1037 IN LATR 16.0
END DESCRIPTION:
XS GIS Cut Line= 4
      2929351.92     10089626.10      2928680.08     10089740.68
      2928461.33     10090167.76      2928029.03     10090547.98
#Sta/Elev= 30
  4133.6 1157.23  4175.0 1156.70  4228.4 1154.44  4331.3 1153.24  4400.9 1150.99
  4725.5 1138.00  4802.6 1136.11  4886.0 1135.68  4943.6 1128.99  4953.4 1126.24
  4960.1 1122.44  4965.8 1120.57  4988.0 1116.33  4995.3 1116.17  4998.1 1115.67
  5001.3 1116.17  5026.7 1121.17  5070.1 1123.15  5182.2 1126.12  5257.8 1129.52
  5295.0 1130.95  5337.0 1134.43  5393.0 1135.73  5443.3 1139.44  5578.0 1145.36
  5670.0 1147.34  5690.9 1146.17  5762.1 1144.92  5832.3 1145.55  5870.7 1144.00
#Mann=6,-1,0
  4133.6     0.1       0  4175.0    0.16       0  4995.3    0.07       0
  5001.3    0.16       0  5070.1    0.05       0  5257.8     0.1       0
Bank Sta=4995.3,5001.3
Exp/Cntr=0.3,0.1

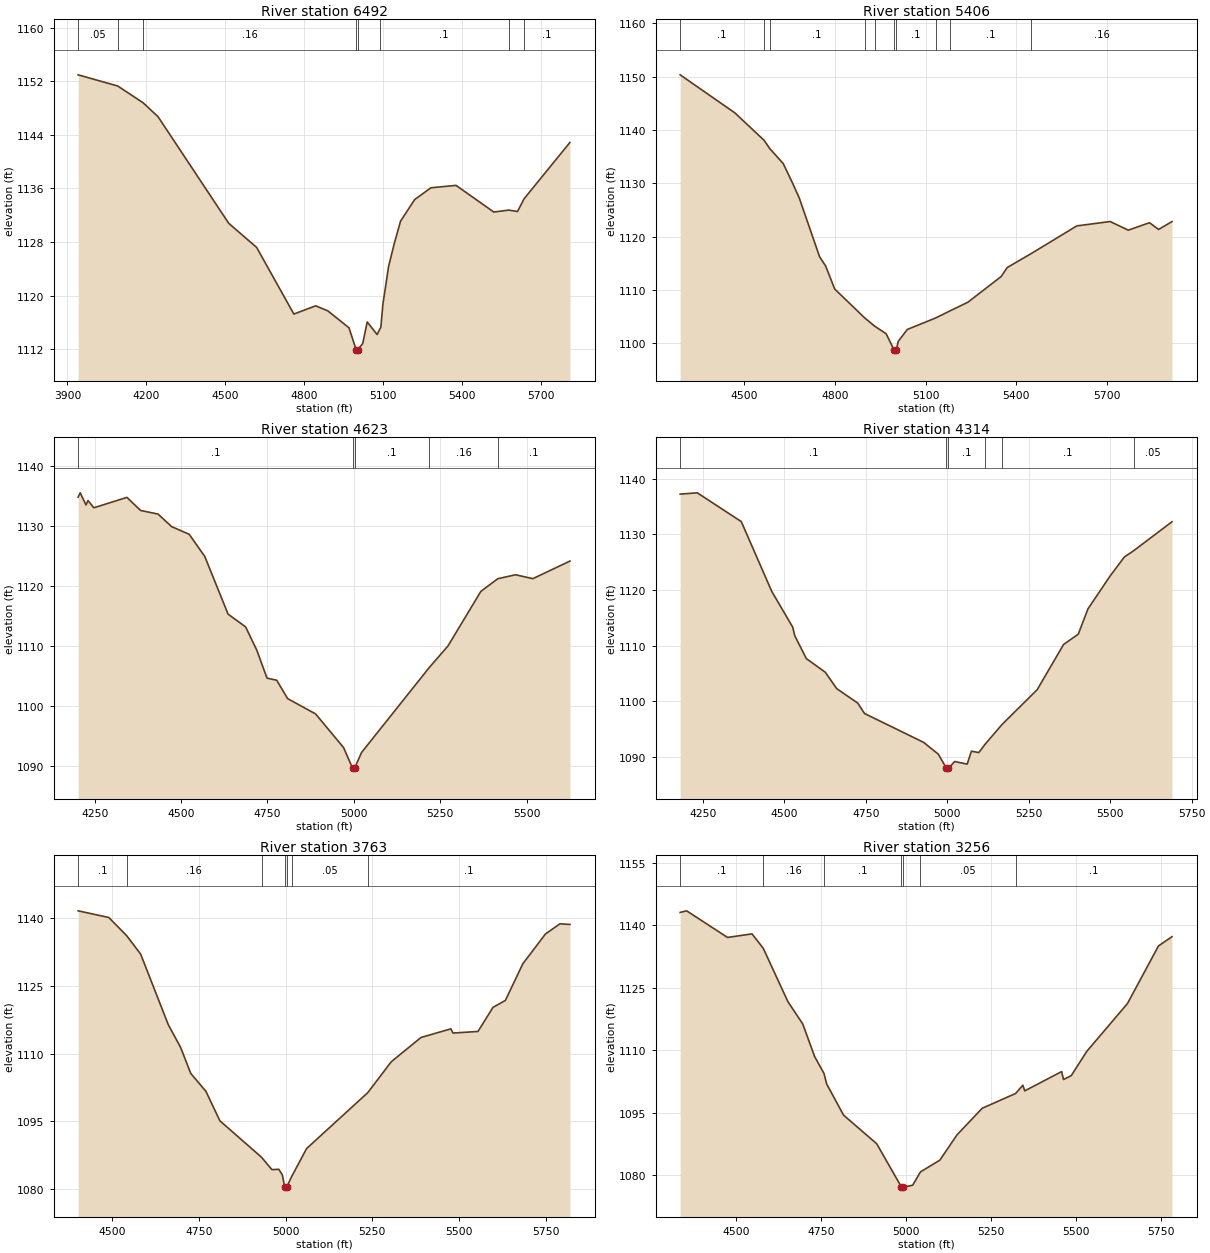
Type RM Length L Ch R = 1,6492,1086,1086,1086
BEGIN DESCRIPTION:
UNT 1037 IN LATR 14.0
END DESCRIPTION:
XS GIS Cut Line= 4
      2928815.53     10089001.06      2928221.74     10089589.64
      2928008.20     10090063.59      2927950.91     10090573.99
#Sta/Elev= 30
  3940.6 1152.94  4091.1 1151.27  4188.0 1148.76  4244.5 1146.68  4513.2 1130.77
  4619.2 1127.18  4760.7 1117.23  4843.5 1118.46  4889.8 1117.71  4970.2 1115.18
  4997.5 1111.90  5000.3 1111.40  5003.5 1111.90  5022.5 1112.84  5039.6 1116.05
  5077.3 1114.17  5086.6 1114.93  5091.3 1115.23  5099.2 1118.72  5121.2 1124.42
  5143.1 1127.87  5166.2 1131.09  5219.9 1134.32  5281.9 1136.08  5377.1 1136.44
  5520.7 1132.46  5577.5 1132.75  5610.8 1132.54  5636.1 1134.45  5810.1 1142.85
#Mann=8,-1,0
  3940.6    0.05       0  4091.1     0.1       0  4188.0    0.16       0
  4997.5    0.07       0  5003.5    0.16       0  5086.6     0.1       0
  5577.5    0.05       0  5636.1     0.1       0
Bank Sta=4997.5,5003.5
Exp/Cntr=0.3,0.1

Type RM Length L Ch R = 1,5406,783,783,783
BEGIN DESCRIPTION:
UNT 1037 IN LATR 12.0
END DESCRIPTION:
XS GIS Cut Line= 3
      2927877.99     10088173.01      2927867.58     10089074.01
      2927841.53     10089797.98
#Sta/Elev= 30
  4288.8 1150.34  4469.5 1143.21  4566.0 1138.07  4585.1 1136.50  4629.5 1133.69
  4659.5 1130.12  4682.5 1127.24  4749.5 1116.24  4769.6 1114.49  4799.6 1110.17
  4898.3 1104.78  4931.1 1103.23  4969.6 1101.78  4996.6 1098.65  4999.3 1098.15
  5002.6 1098.65  5009.6 1100.36  5039.6 1102.59  5132.8 1104.73  5180.2 1106.06
  5239.6 1107.69  5349.7 1112.51  5369.7 1114.20  5448.7 1116.81  5599.8 1122.01
  5709.9 1122.83  5770.0 1121.21  5840.0 1122.61  5870.0 1121.34  5914.3 1122.82
#Mann=10,-1,0
  4288.8     0.1       0  4566.0    0.05       0  4585.1     0.1       0
  4898.3    0.05       0  4931.1     0.1       0  4996.6    0.07       0
  5002.6     0.1       0  5132.8    0.05       0  5180.2     0.1       0
  5448.7    0.16       0
Bank Sta=4996.6,5002.6
Exp/Cntr=0.3,0.1

Type RM Length L Ch R = 1,4623,309,309,309
BEGIN DESCRIPTION:
UNT 1037 IN LATR 11.0
END DESCRIPTION:
XS GIS Cut Line= 4
      2927523.84     10088568.78      2927216.54     10089199.01
      2927284.24     10089438.59      2927320.56     10089910.67
#Sta/Elev= 30
  4202.1 1134.82  4208.1 1135.54  4225.0 1133.52  4230.6 1134.26  4247.6 1133.05
  4343.3 1134.78  4382.8 1132.61  4433.4 1132.00  4472.9 1129.91  4523.5 1128.64
  4568.6 1124.96  4636.2 1115.34  4686.8 1113.23  4719.4 1109.33  4748.9 1104.69
  4777.0 1104.34  4808.4 1101.29  4889.6 1098.73  4970.6 1093.12  4996.4 1089.71
  4999.1 1089.21  5002.4 1089.71  5022.5 1092.31  5219.0 1106.49  5272.6 1110.04
  5368.0 1119.14  5416.9 1121.24  5468.3 1121.90  5518.4 1121.25  5625.7 1124.18
#Mann=5,-1,0
  4202.1     0.1       0  4996.4    0.07       0  5002.4     0.1       0
  5219.0    0.16       0  5416.9     0.1       0
Bank Sta=4996.4,5002.4
Exp/Cntr=0.3,0.1

Type RM Length L Ch R = 1,4314,551,551,551
BEGIN DESCRIPTION:
UNT 1037 IN LATR 10.0
END DESCRIPTION:
XS GIS Cut Line= 4
      2927435.28     10088646.93      2927008.20     10089204.22
      2926841.54     10089521.93      2926441.96     10089724.31
#Sta/Elev= 30
  4180.8 1137.21  4233.3 1137.44  4368.3 1132.28  4461.8 1119.75  4526.1 1113.33
  4532.4 1111.79  4567.8 1107.69  4625.8 1105.25  4661.2 1102.29  4725.6 1099.70
  4746.4 1097.83  4927.5 1092.66  4972.7 1090.54  4997.8 1087.99  5000.6 1087.49
  5003.8 1087.99  5022.9 1089.21  5061.4 1088.75  5074.3 1091.07  5096.9 1090.82
  5116.6 1092.34  5168.6 1095.88  5276.0 1102.10  5357.2 1110.23  5402.1 1112.07
  5431.9 1116.61  5498.8 1122.43  5543.3 1125.91  5572.6 1127.07  5689.6 1132.25
#Mann=6,-1,0
  4180.8     0.1       0  4997.8    0.07       0  5003.8     0.1       0
  5116.6    0.16       0  5168.6     0.1       0  5572.6    0.05       0
Bank Sta=4997.8,5003.8
Exp/Cntr=0.3,0.1

Type RM Length L Ch R = 1,3763,507,507,507
BEGIN DESCRIPTION:
UNT 1037 IN LATR 9.0
END DESCRIPTION:
XS GIS Cut Line= 4
      2927362.35     10088594.85      2927091.54     10088792.76
      2926669.66     10088792.76      2926284.39     10089329.01
#Sta/Elev= 30
  4402.2 1141.54  4490.5 1140.07  4541.9 1136.07  4582.4 1131.98  4662.0 1116.39
  4697.5 1111.38  4726.8 1105.62  4770.7 1101.63  4810.7 1095.15  4930.9 1087.08
  4960.7 1084.35  4980.7 1084.42  4990.7 1083.20  4997.7 1080.54  5000.4 1080.04
  5003.7 1080.54  5017.5 1082.79  5060.7 1089.00  5237.2 1101.37  5304.8 1108.19
  5390.7 1113.56  5476.6 1115.46  5482.8 1114.53  5554.7 1114.88  5598.2 1120.22
  5633.8 1121.74  5684.1 1129.85  5749.2 1136.42  5791.0 1138.67  5819.8 1138.53
#Mann=7,-1,0
  4402.2     0.1       0  4541.9    0.16       0  4930.9     0.1       0
  4997.7    0.07       0  5003.7     0.1       0  5017.5    0.05       0
  5237.2     0.1       0
Bank Sta=4997.7,5003.7
Exp/Cntr=0.3,0.1

Type RM Length L Ch R = 1,3256,479,479,479
BEGIN DESCRIPTION:
UNT 1037 IN LATR 7.0
END DESCRIPTION:
XS GIS Cut Line= 4
      2926935.27     10088084.44      2926492.58     10088433.39
      2926508.20     10088678.18      2926237.37     10089256.30
#Sta/Elev= 30
  4334.6 1143.12  4353.7 1143.50  4473.9 1137.11  4546.1 1137.96  4579.3 1134.48
  4651.8 1121.66  4695.2 1116.36  4730.4 1108.49  4757.9 1104.44  4765.7 1101.93
  4815.4 1094.44  4913.0 1087.56  4985.8 1077.16  4988.6 1076.66  4991.8 1077.16
  5018.9 1077.60  5041.7 1080.79  5099.0 1083.63  5149.5 1089.71  5223.5 1096.08
  5321.8 1099.63  5343.1 1101.62  5348.7 1100.26  5457.3 1104.89  5462.8 1102.99
  5485.6 1103.92  5531.3 1109.75  5651.0 1121.23  5742.3 1135.07  5782.0 1137.29
#Mann=7,-1,0
  4334.6     0.1       0  4579.3    0.16       0  4757.9     0.1       0
  4985.8    0.07       0  4991.8     0.1       0  5041.7    0.05       0
  5321.8     0.1       0
Bank Sta=4985.8,4991.8
Exp/Cntr=0.3,0.1

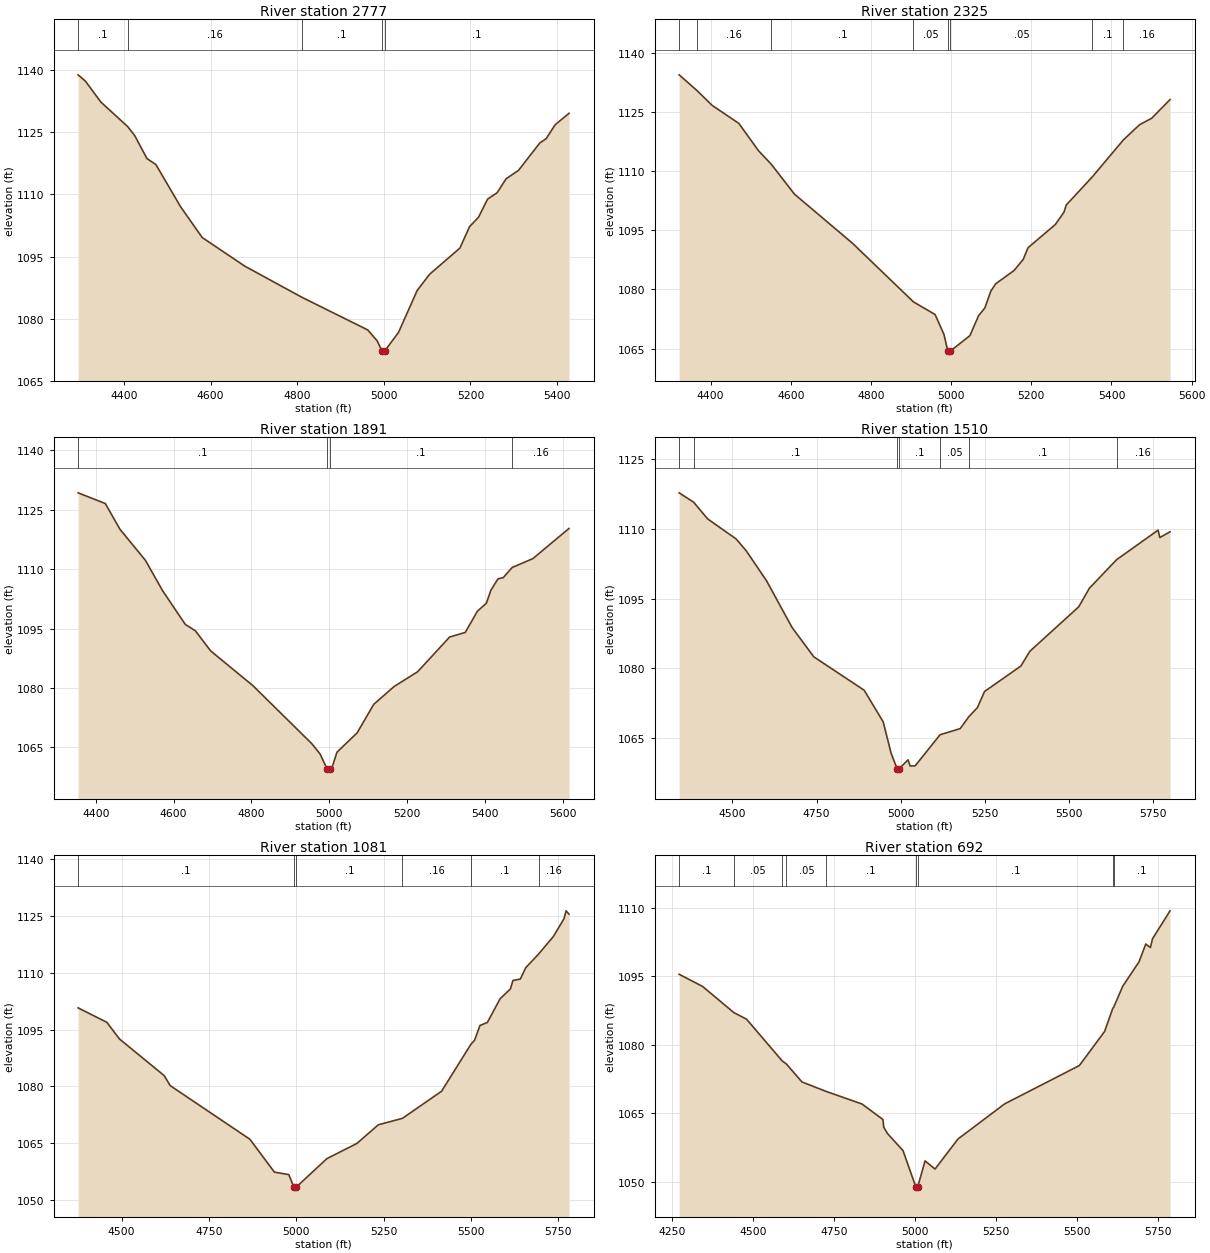
Type RM Length L Ch R = 1,2777,452,452,452
BEGIN DESCRIPTION:
UNT 1037 IN LATR 6.0
END DESCRIPTION:
XS GIS Cut Line= 3
      2926549.83     10087990.71      2926232.16     10088282.34
      2925779.07     10088818.76
#Sta/Elev= 30
  4294.2 1138.85  4311.2 1137.32  4347.0 1132.25  4408.6 1126.37  4424.7 1124.23
  4453.1 1118.66  4474.0 1117.17  4530.7 1107.04  4580.7 1099.59  4679.3 1092.66
  4810.9 1085.16  4962.9 1077.28  4984.7 1074.65  4996.0 1072.18  4998.7 1071.68
  5002.0 1072.18  5034.1 1076.70  5077.0 1086.78  5105.6 1090.70  5175.8 1097.04
  5197.9 1102.19  5218.7 1104.48  5239.6 1108.85  5261.6 1110.38  5282.4 1113.76
  5311.0 1115.79  5360.5 1122.44  5374.8 1123.43  5395.6 1126.80  5427.6 1129.56
#Mann=5,-1,0
  4294.2     0.1       0  4408.6    0.16       0  4810.9     0.1       0
  4996.0    0.07       0  5002.0     0.1       0
Bank Sta=4996,5002
Exp/Cntr=0.3,0.1

Type RM Length L Ch R = 1,2325,434,434,434
BEGIN DESCRIPTION:
UNT 1037 IN LATR 5.0
END DESCRIPTION:
XS GIS Cut Line= 2
      2926409.26     10087771.92      2925352.72     10088391.27
#Sta/Elev= 30
  4321.4 1134.42  4366.0 1130.43  4403.5 1126.69  4470.3 1122.11  4519.4 1115.18
  4551.1 1111.77  4609.0 1104.18  4753.6 1091.74  4906.0 1076.85  4959.9 1073.66
  4982.3 1068.54  4991.6 1064.36  4994.4 1063.86  4997.6 1064.36  5046.8 1068.29
  5068.2 1073.33  5083.9 1075.29  5099.0 1079.59  5111.2 1081.45  5156.9 1084.81
  5179.7 1087.61  5191.7 1090.58  5259.8 1096.46  5281.3 1099.56  5287.1 1101.41
  5352.6 1108.60  5429.8 1117.94  5469.9 1121.76  5500.2 1123.40  5546.1 1128.15
#Mann=8,-1,0
  4321.4     0.1       0  4366.0    0.16       0  4551.1     0.1       0
  4906.0    0.05       0  4991.6   0.035       0  4997.6    0.05       0
  5352.6     0.1       0  5429.8    0.16       0
Bank Sta=4991.6,4997.6
Exp/Cntr=0.3,0.1

Type RM Length L Ch R = 1,1891,381,381,381
BEGIN DESCRIPTION:
UNT 1037 IN LATR 4.0
END DESCRIPTION:
XS GIS Cut Line= 4
      2926206.09     10087516.73      2925737.37     10087662.55
      2925435.29     10087844.84      2925274.17     10088229.45
#Sta/Elev= 30
  4354.8 1129.30  4424.6 1126.60  4462.4 1120.09  4527.5 1112.28  4572.2 1104.52
  4630.3 1096.04  4656.0 1094.45  4695.4 1089.35  4803.5 1080.61  4954.9 1065.94
  4976.2 1063.33  4994.6 1059.49  4997.4 1058.99  5000.6 1059.49  5007.3 1060.02
  5019.6 1063.77  5071.4 1068.66  5114.1 1075.87  5166.5 1080.38  5226.8 1084.10
  5308.9 1092.87  5349.1 1094.03  5380.3 1099.40  5403.3 1101.41  5414.9 1104.69
  5433.3 1107.58  5446.7 1107.88  5469.6 1110.44  5522.6 1112.67  5615.5 1120.30
#Mann=4,-1,0
  4354.8     0.1       0  4994.6    0.07       0  5000.6     0.1       0
  5469.6    0.16       0
Bank Sta=4994.6,5000.6
Exp/Cntr=0.3,0.1

Type RM Length L Ch R = 1,1510,429,429,429
BEGIN DESCRIPTION:
UNT 1037 IN LATR 3.0
END DESCRIPTION:
XS GIS Cut Line= 4
      2926107.19     10087271.92      2925586.33     10087313.59
      2925331.12     10087495.89      2925164.44     10088094.87
#Sta/Elev= 30
  4342.0 1117.79  4385.0 1115.77  4426.7 1112.17  4511.3 1107.85  4541.4 1105.28
  4601.6 1098.83  4677.5 1088.75  4742.0 1082.44  4891.6 1075.24  4948.1 1068.41
  4971.5 1061.66  4989.4 1058.31  4992.1 1057.81  4995.4 1058.31  5021.7 1060.25
  5028.0 1058.93  5042.8 1058.94  5116.8 1065.65  5176.7 1066.98  5202.2 1069.53
  5227.8 1071.50  5248.9 1074.97  5356.7 1080.45  5383.5 1083.64  5528.8 1093.23
  5560.0 1097.20  5640.9 1103.37  5764.3 1109.75  5769.5 1108.16  5799.9 1109.39
#Mann=7,-1,0
  4342.0    0.16       0  4385.0     0.1       0  4989.4    0.07       0
  4995.4     0.1       0  5116.8    0.05       0  5202.2     0.1       0
  5640.9    0.16       0
Bank Sta=4989.4,4995.4
Exp/Cntr=0.3,0.1

Type RM Length L Ch R = 1,1081,389,389,389
BEGIN DESCRIPTION:
UNT 1037 IN LATR 2.0
END DESCRIPTION:
XS GIS Cut Line= 4
      2925904.01     10087068.80      2925492.58     10086964.64
      2924919.66     10087094.84      2924586.35     10087303.16
#Sta/Elev= 30
  4375.7 1100.71  4458.1 1096.90  4494.0 1092.52  4622.1 1082.86  4639.3 1080.22
  4867.4 1066.08  4937.6 1057.41  4978.7 1056.76  4993.6 1053.43  4996.3 1052.93
  4999.6 1053.43  5087.8 1060.97  5173.5 1064.96  5235.0 1069.89  5304.0 1071.59
  5416.2 1078.75  5499.8 1091.09  5510.5 1092.18  5525.9 1096.06  5547.1 1096.87
  5583.6 1103.13  5613.1 1105.70  5620.2 1107.92  5641.4 1108.30  5656.8 1111.29
  5693.7 1114.90  5735.8 1119.50  5766.4 1124.21  5772.3 1126.29  5780.7 1125.41
#Mann=6,-1,0
  4375.7     0.1       0  4993.6    0.07       0  4999.6     0.1       0
  5304.0    0.16       0  5499.8     0.1       0  5693.7    0.16       0
Bank Sta=4993.6,4999.6
Exp/Cntr=0.3,0.1

Type RM Length L Ch R = 1,692,599,599,599
BEGIN DESCRIPTION:
Mapping XS 216f4831
END DESCRIPTION:
XS GIS Cut Line= 4
      2925879.30     10086983.79      2925371.36     10086605.78
      2925005.16     10086691.42      2924674.39     10087075.35
#Sta/Elev= 30
  4272.4 1095.45  4344.9 1092.78  4441.6 1087.04  4480.5 1085.61  4590.3 1076.49
  4603.6 1075.79  4651.5 1071.86  4726.9 1069.76  4837.1 1067.02  4901.8 1063.62
  4904.2 1061.93  4916.1 1060.52  4963.7 1056.81  5003.2 1048.86  5006.0 1048.36
  5009.2 1048.86  5031.8 1054.55  5062.6 1052.76  5133.7 1059.36  5277.4 1067.04
  5508.3 1075.45  5586.2 1082.91  5611.8 1088.04  5613.9 1088.16  5642.1 1092.81
  5692.6 1098.18  5713.4 1102.09  5727.7 1101.31  5734.3 1103.25  5788.4 1109.36
#Mann=9,-1,0
  4272.4     0.1       0  4441.6    0.05       0  4590.3     0.1       0
  4603.6    0.05       0  4726.9     0.1       0  5003.2    0.07       0
  5009.2     0.1       0  5611.8    0.16       0  5613.9     0.1       0
Bank Sta=5003.2,5009.2
Exp/Cntr=0.3,0.1

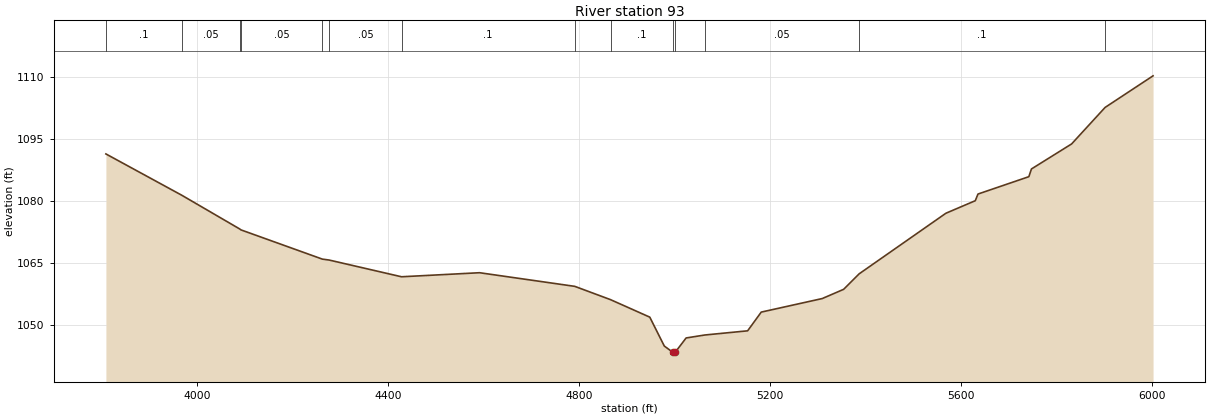
Type RM Length L Ch R = 1,93,0,0,0
BEGIN DESCRIPTION:
UNT 1037 IN LATR 1.0
END DESCRIPTION:
XS GIS Cut Line= 4
      2925876.37     10086942.46      2925200.07     10086053.54
      2925049.46     10086077.16      2924638.96     10086904.08
#Sta/Elev= 30
  3809.3 1091.41  3968.5 1081.39  4090.2 1073.20  4091.8 1073.04  4262.6 1065.95
  4277.1 1065.72  4428.3 1061.68  4591.7 1062.66  4791.1 1059.36  4866.0 1056.14
  4948.1 1051.91  4978.5 1044.92  4995.7 1043.46  4998.5 1042.96  5001.7 1043.46
  5024.2 1046.87  5063.4 1047.59  5153.0 1048.60  5181.5 1053.13  5309.3 1056.41
  5354.0 1058.64  5386.5 1062.39  5568.1 1077.05  5629.7 1080.09  5635.3 1081.70
  5741.8 1085.90  5747.3 1087.77  5831.4 1093.83  5901.5 1102.66  6001.9 1110.31
#Mann=14,-1,0
  3809.3     0.1       0  3968.5    0.05       0  4090.2     0.1       0
  4091.8    0.05       0  4262.6     0.1       0  4277.1    0.05       0
  4428.3     0.1       0  4791.1    0.05       0  4866.0     0.1       0
  4995.7    0.07       0  5001.7     0.1       0  5063.4    0.05       0
  5386.5     0.1       0  5901.5    0.16       0
Bank Sta=4995.7,5001.7
Exp/Cntr=0.3,0.1

Chan Stop Cuts=-1