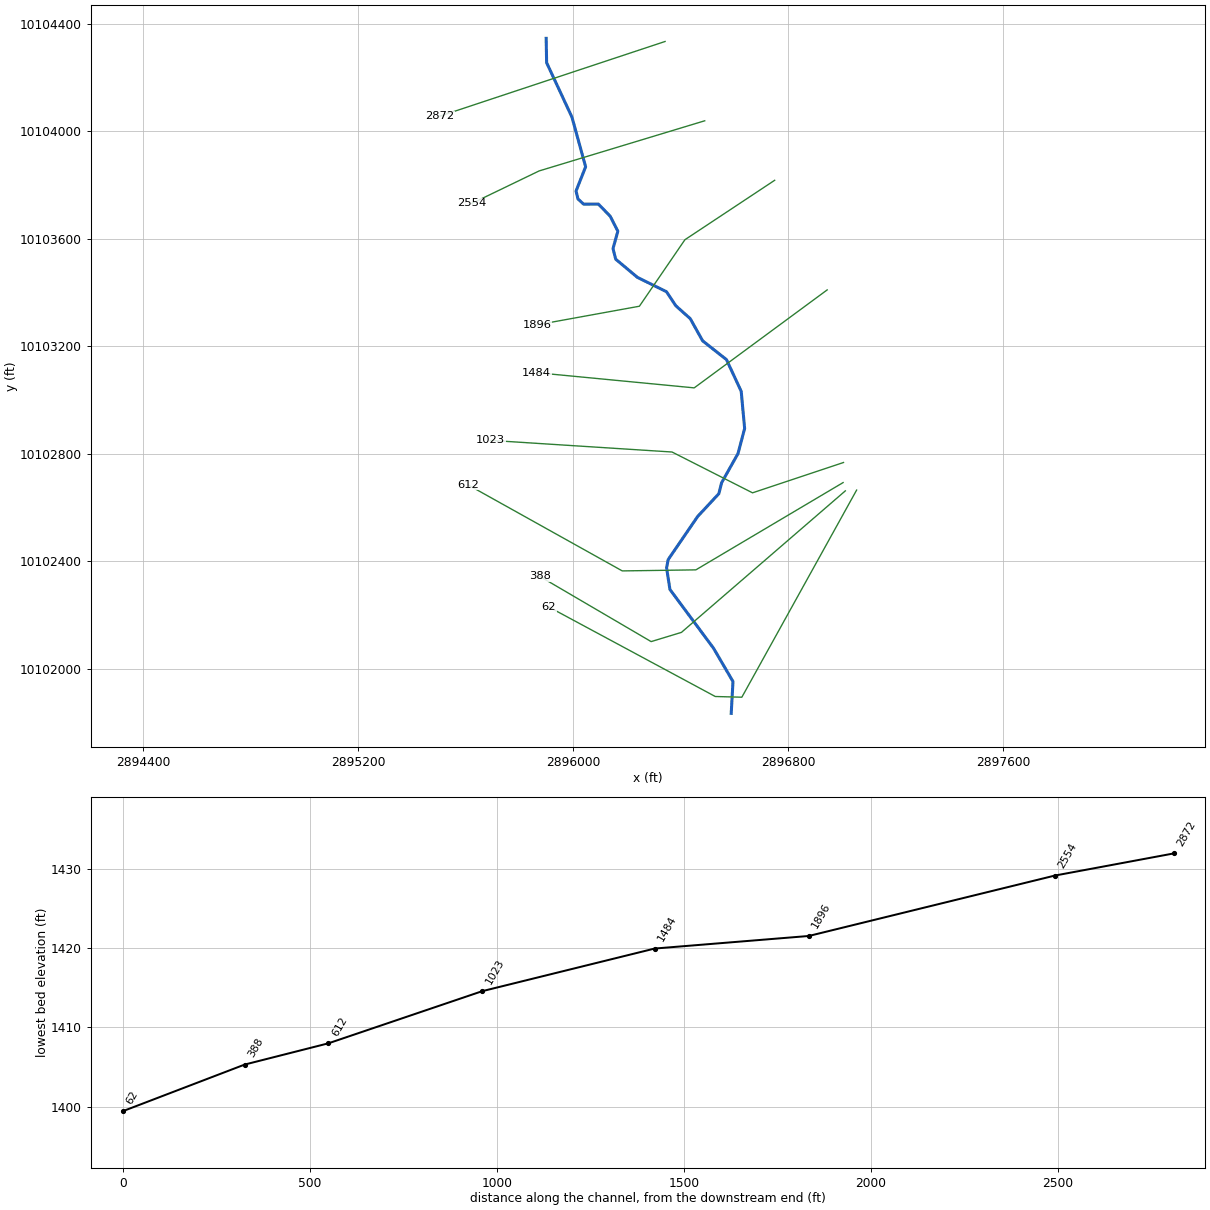
--- UNT 0040 IN LATR.prj (project) ---

Proj Title=UNT 1040 IN LATR Base Level Engineering
Current Plan=p01
Default Exp/Contr=0.3,0.1
English Units
Geom File=g01
Flow File=f01
Plan File=p01
Y Axis Title=Elevation
X Axis Title(PF)=Main Channel Distance
X Axis Title(XS)=Station
BEGIN DESCRIPTION:
UNT 1040 IN LATR
END DESCRIPTION:
DSS Export Rating Curves= 0
DSS Export Rating Curve Sorted= 0
DSS Export Volume Flow Curves= 0
DXF OffsetX= 0
DXF OffsetY= 0
DXF ScaleX= 1
DXF ScaleY= 10

--- UNT 0040 IN LATR.p01 (plan) ---

Plan Title=Multiple Run
Short Identifier=Multiple
Geom File=g01
Flow File=f01
Subcritical Flow
K Sum by GR= 0
Std Step Tol= 0.01
Critical Tol= 0.01
Num of Std Step Trials= 20
Max Error Tol= 0.3
Flow Tol Ratio= 0.001
Split Flow NTrial= 30
Split Flow Tol= 0.02
Split Flow Ratio= 0.02
Log Output Level= 0
Friction Slope Method= 1
Unsteady Friction Slope Method= 2
Unsteady Bridges Friction Slope Method= 1
Parabolic Critical Depth
Global Vel Dist=  1 , 1 , 1
Global Log Level= 0
CheckData=True
Encroach Param= -1, 0, 0, 0
BEGIN DESCRIPTION:
Multiple Run
END DESCRIPTION:

--- UNT 0040 IN LATR.f01 (steady flow) ---

Flow Title=Multiple
Number of Profiles=7
Profile Names=10-year,25-year,50-year,1pct_min,100-year,1pct_plu,500-year
River Rch & RM= UNT 1040 IN LATR,Reach-1,2872
     833    1209    1535    1429    1932    2613    3071
Boundary for River Rch & Prof#=UNT 1040 IN LATR,Reach-1,1
Up Type=0
Dn Type=3
Dn Slope=0.005
Boundary for River Rch & Prof#=UNT 1040 IN LATR,Reach-1,2
Up Type=0
Dn Type=3
Dn Slope=0.005
Boundary for River Rch & Prof#=UNT 1040 IN LATR,Reach-1,3
Up Type=0
Dn Type=3
Dn Slope=0.005
Boundary for River Rch & Prof#=UNT 1040 IN LATR,Reach-1,4
Up Type=0
Dn Type=3
Dn Slope=0.005
Boundary for River Rch & Prof#=UNT 1040 IN LATR,Reach-1,5
Up Type=0
Dn Type=3
Dn Slope=0.005
Boundary for River Rch & Prof#=UNT 1040 IN LATR,Reach-1,6
Up Type=0
Dn Type=3
Dn Slope=0.005
Boundary for River Rch & Prof#=UNT 1040 IN LATR,Reach-1,7
Up Type=0
Dn Type=3
Dn Slope=0.005

--- UNT 0040 IN LATR.g01 (geometry) ---

Geom Title=Existing Conditions
Program Version=4.10

River Reach=UNT 1040 IN LATR,Reach-1
Reach XY= 30
      2895899.84     10104345.87      2895901.55     10104255.12
      2895995.78     10104052.62      2896046.66     10103867.95
      2896011.02     10103777.58      2896018.09     10103748.38
      2896039.12     10103728.86      2896094.36     10103728.97
      2896138.17     10103683.79      2896166.58     10103628.06
      2896148.57     10103563.41      2896158.72     10103523.89
      2896239.49     10103456.25      2896347.57     10103402.94
      2896382.28     10103350.64       2896436.1     10103302.66
      2896482.07     10103220.18      2896570.79     10103150.28
      2896625.67     10103032.38      2896638.41     10102893.97
      2896613.86     10102800.93      2896552.72     10102691.97
       2896542.5     10102651.31      2896463.61      10102566.5
      2896353.94     10102406.12       2896347.9     10102375.34
      2896360.56     10102294.63      2896522.59     10102076.31
      2896595.07     10101952.25      2896588.47     10101833.73

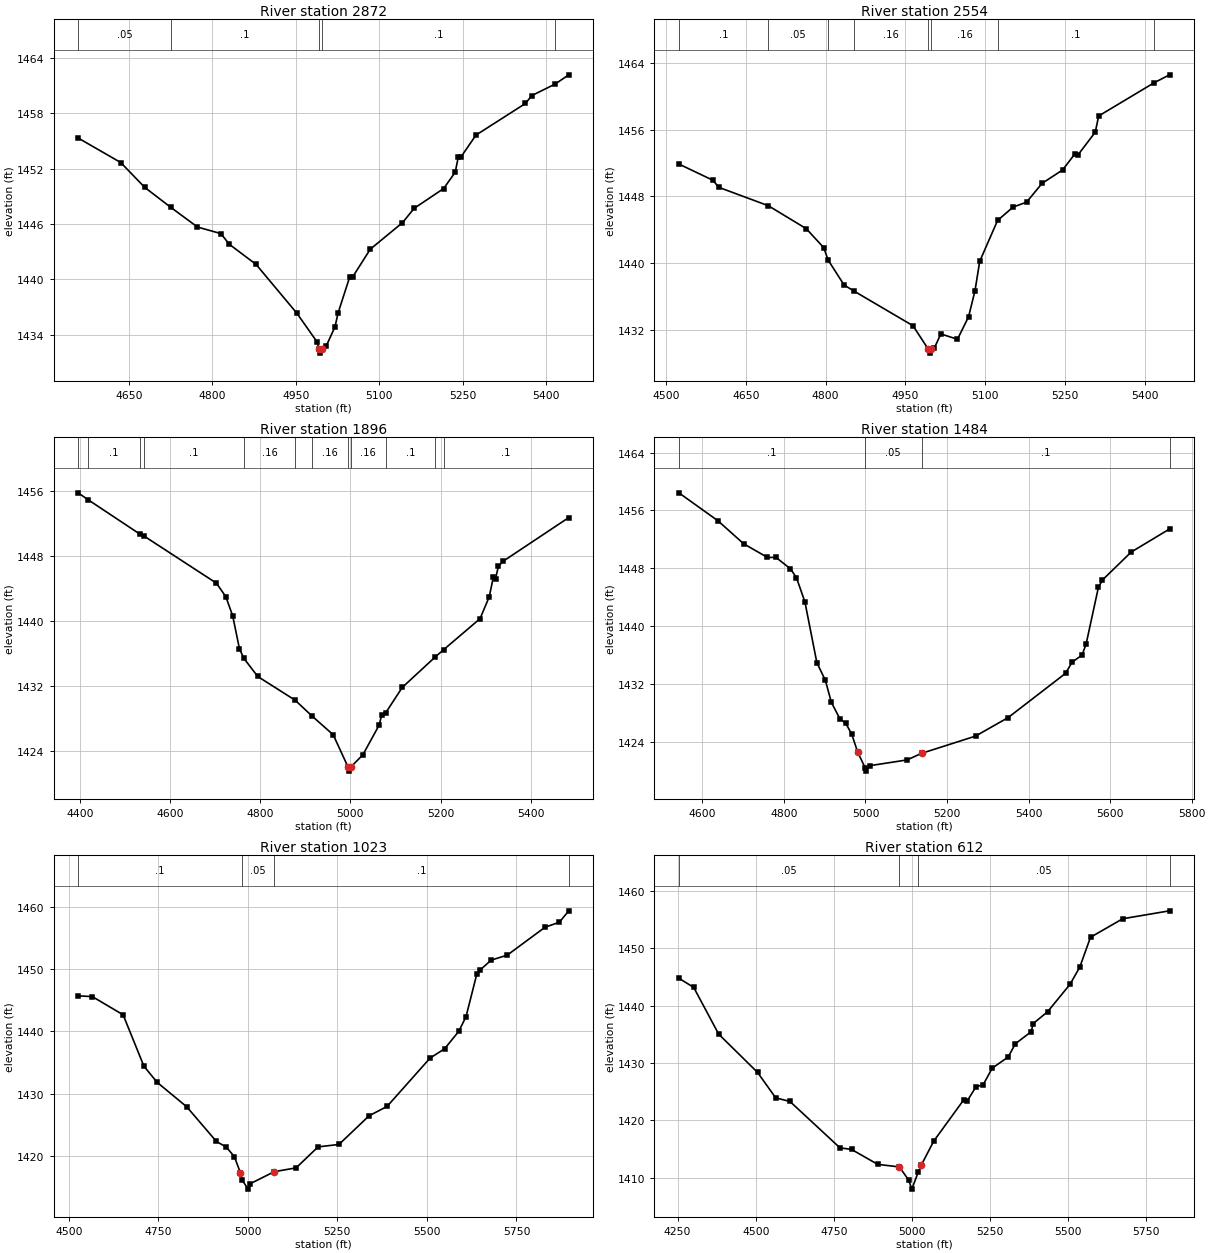
Type RM Length L Ch R = 1 ,2872    ,318,318,318
BEGIN DESCRIPTION:
UNT 1040 IN LATR 6.0
END DESCRIPTION:
XS GIS Cut Line= 2
      2896342.35     10104334.18       2895504.6     10104056.38
#Sta/Elev= 30
  4558.2 1455.32  4634.9 1452.66  4678.2 1449.96  4724.6 1447.82    4773 1445.67
  4815.1 1444.96  4830.3  1443.8  4878.4 1441.62  4951.8 1436.33  4988.7 1433.17
  4991.2 1432.51    4994 1432.01  4997.2 1432.51  5004.8 1432.81  5020.4 1434.87
  5025.8 1436.34  5046.9 1440.28  5052.1 1440.26  5083.8 1443.27  5141.7 1446.14
  5162.8  1447.7  5215.8 1449.84  5236.6 1451.61  5242.3 1453.31  5247.5 1453.31
  5273.9 1455.63    5363 1459.06  5374.3 1459.91  5416.4 1461.16  5440.8 1462.16
#Mann= 5 ,-1 , 0
  4558.2     .05       0  4724.6      .1       0  4991.2     .07       0
  4997.2      .1       0  5416.4     .05       0
Bank Sta=4991.2,4997.2
XS Rating Curve= 0 ,0
Exp/Cntr=0.3,0.1

Type RM Length L Ch R = 1 ,2554    ,658,658,658
BEGIN DESCRIPTION:
UNT 1040 IN LATR 5.0
END DESCRIPTION:
XS GIS Cut Line= 3
      2896489.91     10104039.03      2895873.55     10103852.39
      2895622.65     10103731.27
#Sta/Elev= 30
  4524.1 1451.87  4588.3 1449.92  4599.1 1449.08  4692.5 1446.87  4763.7 1444.12
  4796.6 1441.84  4804.7 1440.37  4834.8 1437.37  4854.1 1436.62  4964.4 1432.49
  4992.8 1429.71  4995.5 1429.21  4998.8 1429.71  5004.6 1429.84  5016.7 1431.51
    5048 1430.87  5068.9 1433.58  5080.9 1436.68  5089.8 1440.21  5123.4 1445.11
  5152.5 1446.71  5177.9  1447.3  5207.1 1449.56  5245.7 1451.16  5268.3 1453.05
  5273.9 1452.91    5307 1455.68  5313.5 1457.63  5417.5  1461.6  5446.7 1462.56
#Mann= 8 ,-1 , 0
  4524.1      .1       0  4692.5     .05       0  4804.7      .1       0
  4854.1     .16       0  4992.8     .07       0  4998.8     .16       0
  5123.4      .1       0  5417.5     .05       0
Bank Sta=4992.8,4998.8
XS Rating Curve= 0 ,0
Exp/Cntr=0.3,0.1

Type RM Length L Ch R = 1 ,1896    ,412,412,412
BEGIN DESCRIPTION:
UNT 1040 IN LATR 4.0
END DESCRIPTION:
XS GIS Cut Line= 4
      2896750.27     10103817.66      2896416.09     10103596.31
      2896246.81     10103348.92      2895864.88     10103279.48
#Sta/Elev= 30
  4395.7 1455.74  4418.3 1454.88  4533.4 1450.65  4541.1 1450.47  4702.7 1444.65
  4723.7 1442.97  4738.8 1440.64  4753.8 1436.59  4763.6 1435.42  4794.4 1433.19
  4877.3 1430.28    4914 1428.38  4961.9 1426.03  4994.8 1422.07  4997.5 1421.57
  5000.8 1422.07  5027.6 1423.57  5063.5 1427.19  5069.6 1428.48  5078.5 1428.74
    5115 1431.84  5187.5 1435.55  5206.7 1436.47  5287.7 1440.29  5308.1 1442.98
  5317.1 1445.36  5322.1 1445.22  5328.4 1446.71  5338.6 1447.33  5484.5  1452.7
#Mann= 12 ,-1 , 0
  4395.7     .05       0  4418.3      .1       0  4533.4     .05       0
  4541.1      .1       0  4763.6     .16       0  4877.3      .1       0
    4914     .16       0  4994.8     .07       0  5000.8     .16       0
  5078.5      .1       0  5187.5     .05       0  5206.7      .1       0
Bank Sta=4994.8,5000.8
XS Rating Curve= 0 ,0
Exp/Cntr=0.3,0.1

Type RM Length L Ch R = 1 ,1484    ,461,461,461
BEGIN DESCRIPTION:
UNT 1040 IN LATR 3.0
END DESCRIPTION:
XS GIS Cut Line= 3
      2896945.61     10103409.69      2896450.81      10103045.1
      2895864.83     10103101.53
#Sta/Elev= 30
  4542.4 1458.44  4638.2 1454.58  4701.1 1451.41  4759.7 1449.51  4780.5 1449.52
    4816 1447.94  4830.7 1446.73  4851.5 1443.37  4880.8 1434.98  4901.7 1432.52
  4916.3  1429.5  4937.1 1427.23  4951.8 1426.58  4966.4 1425.08  4981.1 1422.58
  4998.9 1420.48  5001.7 1419.98  5010.3 1420.73  5102.2 1421.53  5137.7 1422.44
  5269.9 1424.82  5350.2 1427.39  5490.9  1433.5  5506.9 1435.05  5531.1 1436.01
  5541.1 1437.53  5571.3 1445.38  5581.3  1446.4  5651.6 1450.25  5745.7 1453.44
#Mann= 4 ,-1 , 0
  4542.4      .1       0  4998.9     .05       0  5137.7      .1       0
  5745.7     .05       0
Bank Sta=4981.1,5137.7
XS Rating Curve= 0 ,0
Exp/Cntr=0.3,0.1

Type RM Length L Ch R = 1 ,1023    ,411,411,411
BEGIN DESCRIPTION:
UNT 1040 IN LATR 2.0
END DESCRIPTION:
XS GIS Cut Line= 4
      2897006.33     10102767.31      2896667.82     10102654.47
      2896368.34     10102806.38      2895692.35     10102849.72
#Sta/Elev= 30
    4526 1445.75  4565.9 1445.62  4651.8 1442.69  4709.7 1434.42  4746.6 1431.81
  4829.4 1427.86  4912.2 1422.28  4940.1 1421.35  4962.4 1419.83    4979 1417.26
  4984.6    1416    5001 1414.59  5006.9 1415.47  5073.7  1417.4  5134.9 1418.02
  5196.1  1421.4  5254.4 1421.79  5338.7 1426.42  5388.8 1427.92  5509.1 1435.73
  5549.2  1437.2  5589.3 1440.05  5609.3 1442.41  5639.4 1449.28  5649.4 1449.96
  5679.4  1451.5  5724.4 1452.31  5829.7  1456.8  5869.8 1457.61    5896 1459.45
#Mann= 4 ,-1 , 0
    4526      .1       0  4984.6     .05       0  5073.7      .1       0
    5896     .05       0
Bank Sta=4979,5073.7
XS Rating Curve= 0 ,0
Exp/Cntr=0.3,0.1

Type RM Length L Ch R = 1 ,612     ,224,224,224
BEGIN DESCRIPTION:
Mapping XS 3ff448ae
END DESCRIPTION:
XS GIS Cut Line= 4
      2897004.89     10102692.65      2896456.98     10102367.82
      2896183.02     10102363.91      2895607.72     10102684.82
#Sta/Elev= 30
  4254.2 1444.77  4301.7 1443.17  4381.6 1435.02  4505.8 1428.36  4563.9 1423.92
  4609.7 1423.28  4769.5  1415.2  4806.6 1414.92  4890.3 1412.32  4959.7 1411.87
  4989.7 1409.55  4999.4    1408  5019.7 1410.91  5029.7 1412.18  5069.7 1416.38
  5164.9 1423.52  5175.6 1423.28  5204.7 1425.84  5227.6 1426.19  5256.7 1429.09
  5307.8 1431.04  5330.7 1433.34  5381.3 1435.45  5387.9 1436.87  5433.7 1438.92
  5505.8 1443.72  5536.8 1446.71  5571.1 1451.91  5674.2 1455.14  5823.9 1456.52
#Mann= 4 ,-1 , 0
  4254.2     .05       0  4959.7    .035       0  5019.7     .05       0
  5823.9      .1       0
Bank Sta=4959.7,5029.7
XS Rating Curve= 0 ,0
Exp/Cntr=0.3,0.1

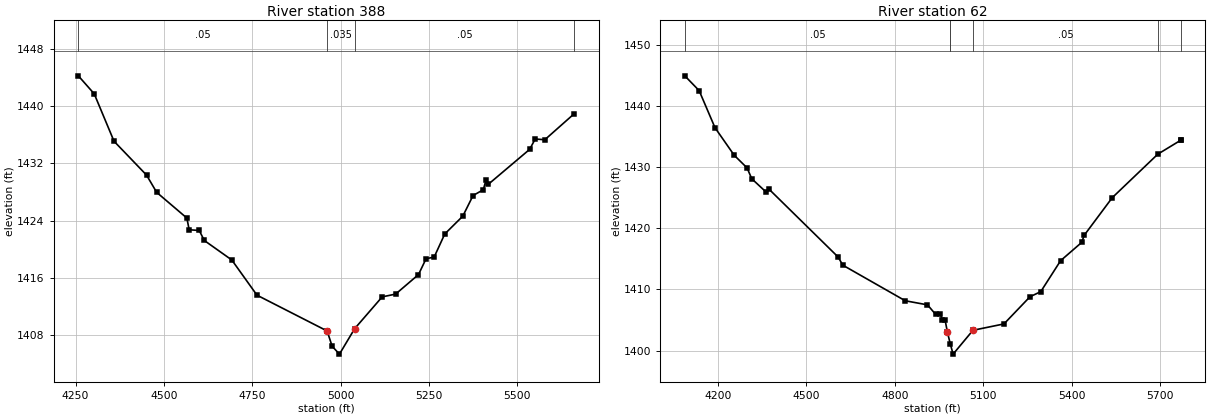
Type RM Length L Ch R = 1 ,388     ,326,326,326
BEGIN DESCRIPTION:
Mapping XS 2dcafaca
END DESCRIPTION:
XS GIS Cut Line= 4
      2897013.24     10102661.86      2896403.23     10102135.14
      2896290.53     10102100.84      2895876.49     10102343.39
#Sta/Elev= 30
  4257.8 1444.25  4302.8 1441.73  4358.8  1435.1  4450.9 1430.36  4479.5 1427.95
    4565 1424.35  4571.6 1422.71  4600.1 1422.61  4614.4 1421.21  4692.3 1418.48
  4763.5 1413.56  4962.1 1408.55  4976.3 1406.41    4997 1405.31    5040 1408.87
  5117.9 1413.32    5156 1413.71  5220.7 1416.44  5242.2 1418.66  5265.1 1418.89
  5295.1 1422.12  5346.2 1424.62  5375.2  1427.5  5404.1 1428.31  5412.4 1429.74
  5418.1 1429.06  5535.4 1433.96  5551.1 1435.41  5578.4 1435.31  5661.4 1438.94
#Mann= 4 ,-1 , 0
  4257.8     .05       0  4962.1    .035       0    5040     .05       0
  5661.4      .1       0
Bank Sta=4962.1,5040
XS Rating Curve= 0 ,0
Exp/Cntr=0.3,0.1

Type RM Length L Ch R = 1 ,62      ,0,0,0
BEGIN DESCRIPTION:
UNT 1040 IN LATR 1.0
END DESCRIPTION:
XS GIS Cut Line= 4
      2897055.17     10102664.73       2896628.1     10101893.92
      2896529.15     10101896.53      2895910.36     10102229.32
#Sta/Elev= 30
  4087.5 1444.94  4136.2 1442.52    4190 1436.45  4255.3 1431.94  4298.8 1429.88
  4314.8  1428.1    4364  1425.9  4374.3 1426.35  4607.8  1415.3  4623.9 1413.96
  4835.7 1408.14  4911.2 1407.47  4938.7 1405.92  4954.7 1406.05  4960.4 1405.05
    4971 1404.98  4978.4 1403.09  4988.4 1401.11  4998.1 1399.41  5065.5 1403.31
  5170.7 1404.35  5259.1  1408.8  5295.6 1409.63    5363  1414.7  5434.4 1417.68
  5443.2 1418.86  5538.3 1425.01    5693 1432.13  5769.9 1434.38  5770.3 1434.49
#Mann= 6 ,-1 , 0
  4087.5     .05       0  4988.4      .1       0  4988.4    .035       0
  5065.5     .05       0    5693     .05       0  5769.9      .1       0
Bank Sta=4978.4,5065.5
XS Rating Curve= 0 ,0
Exp/Cntr=0.3,0.1

Chan Stop Cuts=-1
Use User Specified Reach Order=0
Composite Channel Slope=5