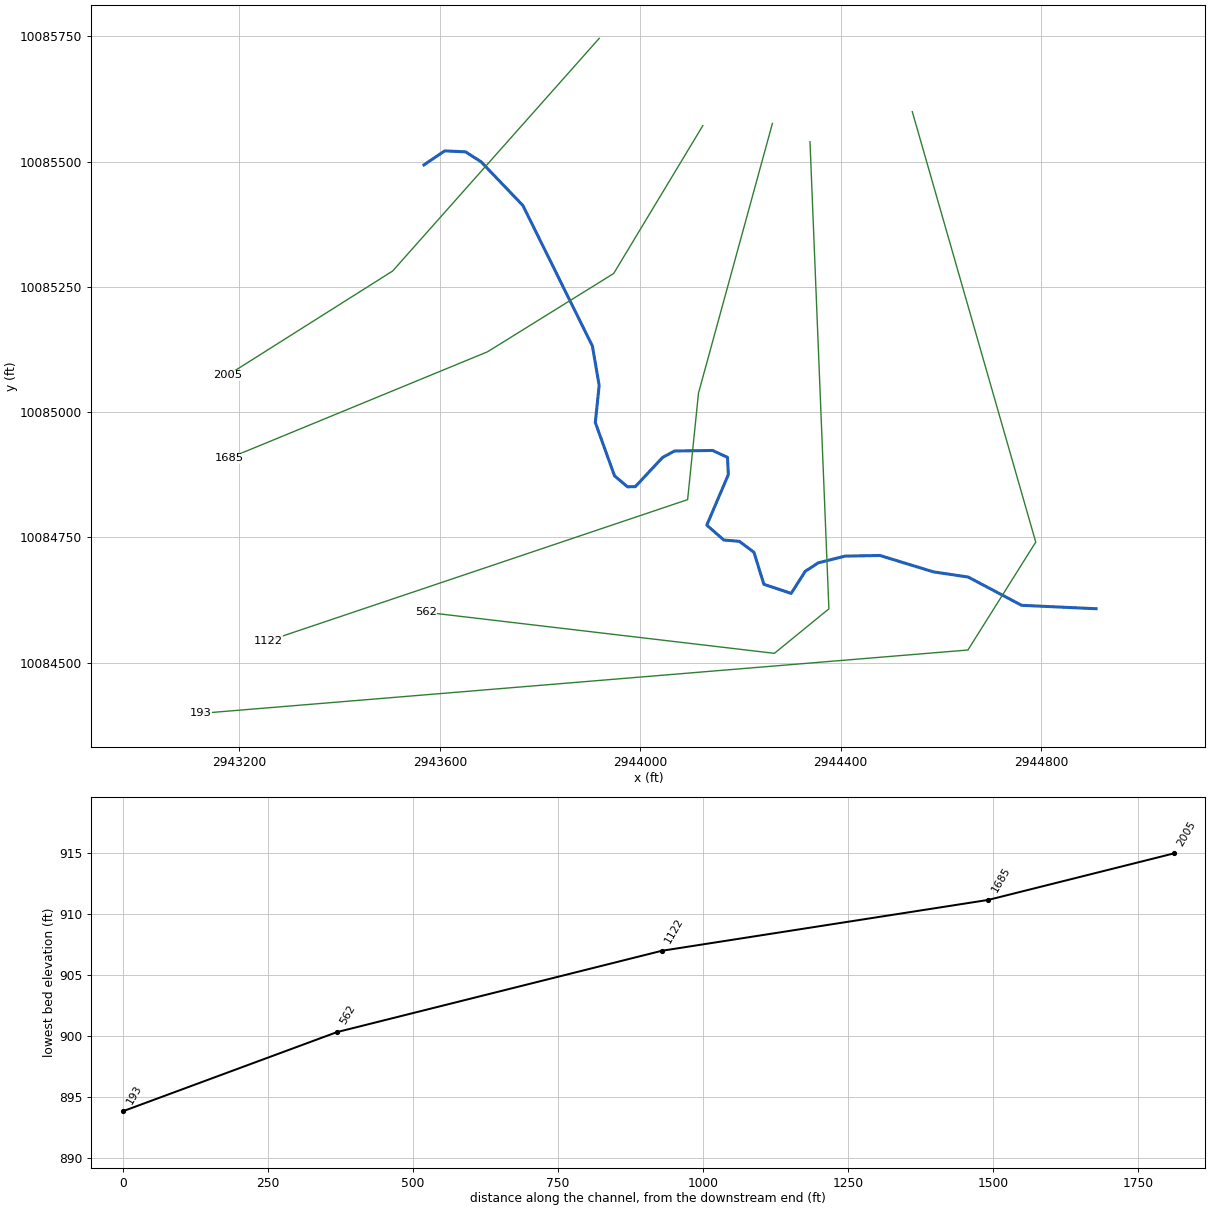
--- UNT 0041 IN LATR.prj (project) ---

Proj Title=UNT 1041 IN LATR Base Level Engineering
Current Plan=p01
Default Exp/Contr=0.3,0.1
English Units
Geom File=g01
Flow File=f01
Plan File=p01
BEGIN DESCRIPTION:
UNT 1041 IN LATR
END DESCRIPTION:

--- UNT 0041 IN LATR.p01 (plan) ---

Plan Title=Multiple Run
Short Identifier=Multiple
Geom File=g01
Flow File=f01
Subcritical Flow
K Sum by GR= 0
Std Step Tol= 0.01
Critical Tol= 0.01
Num of Std Step Trials= 20
Max Error Tol= 0.3
Flow Tol Ratio= 0.001
Split Flow NTrial= 30
Split Flow Tol= 0.02
Split Flow Ratio= 0.02
Log Output Level= 0
Friction Slope Method= 1
Unsteady Friction Slope Method= 2
Unsteady Bridges Friction Slope Method= 1
Parabolic Critical Depth
Global Vel Dist=  1 , 1 , 1
Global Log Level= 0
CheckData=True
Encroach Param= -1, 0, 0, 0
BEGIN DESCRIPTION:
Multiple Run
END DESCRIPTION:

--- UNT 0041 IN LATR.f01 (steady flow) ---

Flow Title=Multiple
Number of Profiles=7
Profile Names=10-year,25-year,50-year,1pct_min,100-year,1pct_plu,500-year
River Rch & RM= UNT 1041 IN LATR,Reach-1,2005
     842    1215    1538    1426    1928    2608    3041
Boundary for River Rch & Prof#=UNT 1041 IN LATR,Reach-1,1
Up Type=0
Dn Type=3
Dn Slope=0.005
Boundary for River Rch & Prof#=UNT 1041 IN LATR,Reach-1,2
Up Type=0
Dn Type=3
Dn Slope=0.005
Boundary for River Rch & Prof#=UNT 1041 IN LATR,Reach-1,3
Up Type=0
Dn Type=3
Dn Slope=0.005
Boundary for River Rch & Prof#=UNT 1041 IN LATR,Reach-1,4
Up Type=0
Dn Type=3
Dn Slope=0.005
Boundary for River Rch & Prof#=UNT 1041 IN LATR,Reach-1,5
Up Type=0
Dn Type=3
Dn Slope=0.005
Boundary for River Rch & Prof#=UNT 1041 IN LATR,Reach-1,6
Up Type=0
Dn Type=3
Dn Slope=0.005
Boundary for River Rch & Prof#=UNT 1041 IN LATR,Reach-1,7
Up Type=0
Dn Type=3
Dn Slope=0.005

--- UNT 0041 IN LATR.g01 (geometry) ---

Geom Title=Existing Conditions

River Reach=UNT 1041 IN LATR,Reach-1
Reach XY= 30
      2943568.47     10085493.73      2943609.88     10085521.65
      2943651.35     10085519.78      2943682.27     10085500.09
      2943765.94     10085412.69      2943904.67     10085132.15
      2943918.16     10085053.52      2943910.49     10084979.39
      2943948.88     10084873.06      2943974.75     10084851.15
      2943990.37     10084851.49      2944044.51     10084909.53
      2944068.55     10084922.64      2944144.60     10084923.67
      2944174.29     10084909.94      2944176.05     10084875.54
      2944133.01     10084774.62      2944167.11     10084744.90
      2944198.01     10084742.29      2944227.18     10084720.42
      2944246.96     10084656.50      2944301.44     10084638.43
      2944329.54     10084682.50      2944355.34     10084699.32
      2944408.85     10084712.78      2944478.54     10084714.09
      2944585.20     10084681.41      2944654.70     10084671.03
      2944761.47     10084614.60      2944910.04     10084607.80

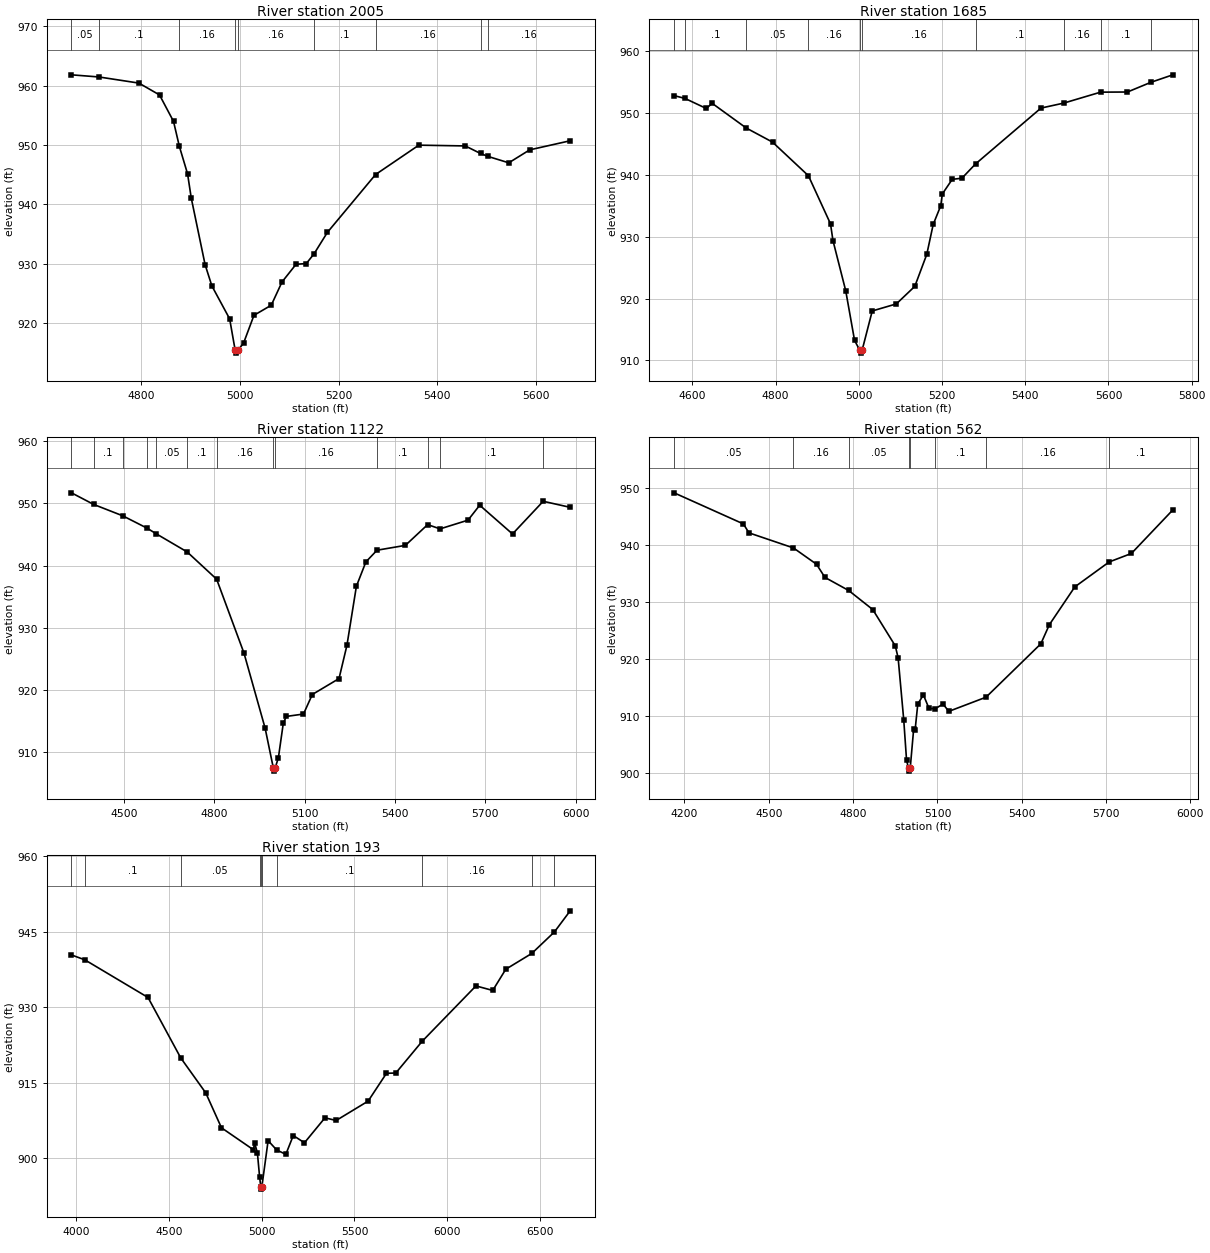
Type RM Length L Ch R = 1,2005,320,320,320
BEGIN DESCRIPTION:
UNT 1041 IN LATR 4.0
END DESCRIPTION:
XS GIS Cut Line= 3
      2943918.31     10085746.32      2943505.97     10085281.89
      2943176.11     10085073.56
#Sta/Elev= 30
  4658.4  961.81  4714.2  961.45  4795.1  960.42  4836.9  958.43  4865.3  953.98
  4877.1  949.79  4893.8  945.15  4901.3  941.07  4929.3  929.89  4943.1  926.30
  4979.1  920.77  4990.3  915.50  4993.0  915.00  4996.3  915.50  5007.5  916.72
  5028.4  921.36  5063.5  923.06  5085.3  926.97  5113.7  929.94  5134.6  930.07
  5150.4  931.72  5177.3  935.31  5275.0  945.04  5362.7  949.98  5456.9  949.85
  5487.8  948.58  5503.2  948.08  5545.1  947.01  5587.5  949.19  5669.6  950.72
#Mann=9,-1,0
  4658.4    0.05       0  4714.2     0.1       0  4877.1    0.16       0
  4990.3    0.07       0  4996.3    0.16       0  5150.4     0.1       0
  5275.0    0.16       0  5487.8     0.1       0  5503.2    0.16       0
Bank Sta=4990.3,4996.3
Exp/Cntr=0.3,0.1

Type RM Length L Ch R = 1,1685,563,563,563
BEGIN DESCRIPTION:
UNT 1041 IN LATR 3.0
END DESCRIPTION:
XS GIS Cut Line= 4
      2944125.12     10085572.11      2943947.16     10085276.95
      2943695.42     10085120.70      2943179.76     10084908.37
#Sta/Elev= 30
  4556.1  952.83  4582.3  952.37  4633.4  950.75  4647.6  951.58  4729.4  947.59
  4792.6  945.31  4878.9  939.87  4932.0  932.09  4937.9  929.39  4968.6  921.26
  4989.8  913.24  5002.1  911.68  5004.9  911.18  5008.1  911.68  5032.3  918.00
  5090.2  919.14  5134.6  921.98  5163.4  927.16  5178.8  931.99  5197.0  935.03
  5200.7  936.92  5224.6  939.29  5247.8  939.47  5280.6  941.78  5437.8  950.81
  5492.7  951.62  5581.2  953.39  5645.6  953.41  5702.4  954.99  5754.7  956.19
#Mann=10,-1,0
  4556.1    0.05       0  4582.3     0.1       0  4729.4    0.05       0
  4878.9    0.16       0  5002.1    0.07       0  5008.1    0.16       0
  5280.6     0.1       0  5492.7    0.16       0  5581.2     0.1       0
  5702.4    0.16       0
Bank Sta=5002.1,5008.1
Exp/Cntr=0.3,0.1

Type RM Length L Ch R = 1,1122,560,560,560
BEGIN DESCRIPTION:
UNT 1041 IN LATR 2.0
END DESCRIPTION:
XS GIS Cut Line= 4
      2944264.00     10085576.46      2944116.43     10085038.24
      2944094.73     10084825.56      2943257.03     10084543.44
#Sta/Elev= 30
  4326.2  951.71  4399.7  949.85  4496.8  948.01  4577.3  946.03  4607.2  945.14
  4710.4  942.21  4808.2  937.83  4898.9  925.97  4969.2  913.89  4996.4  907.50
  4999.1  907.00  5002.4  907.50  5013.2  909.15  5029.5  914.70  5039.6  915.79
  5096.5  916.17  5125.8  919.31  5214.5  921.87  5240.7  927.19  5272.2  936.70
  5303.7  940.61  5340.6  942.49  5434.9  943.27  5508.7  946.60  5550.1  945.92
  5642.8  947.32  5681.6  949.72  5790.5  945.10  5892.4  950.35  5982.0  949.38
#Mann=13,-1,0
  4326.2    0.05       0  4399.7     0.1       0  4496.8    0.05       0
  4577.3     0.1       0  4607.2    0.05       0  4710.4     0.1       0
  4808.2    0.16       0  4996.4    0.07       0  5002.4    0.16       0
  5340.6     0.1       0  5508.7    0.16       0  5550.1     0.1       0
  5892.4    0.16       0
Bank Sta=4996.4,5002.4
Exp/Cntr=0.3,0.1

Type RM Length L Ch R = 1,562,369,369,369
BEGIN DESCRIPTION:
Mapping XS 4303869f
END DESCRIPTION:
XS GIS Cut Line= 4
      2944338.98     10085539.94      2944376.72     10084607.54
      2944267.94     10084518.75      2943572.23     10084600.73
#Sta/Elev= 30
  4163.1  949.11  4409.5  943.66  4429.5  942.09  4587.6  939.45  4669.7  936.59
  4699.7  934.28  4784.1  931.99  4869.9  928.64  4949.9  922.28  4960.0  920.19
  4980.0  909.31  4990.0  902.25  4997.0  900.82  4999.7  900.32  5003.0  900.82
  5015.4  907.74  5020.4  907.52  5030.0  912.10  5050.0  913.68  5070.0  911.30
  5092.3  911.27  5119.7  912.08  5140.5  910.80  5272.7  913.28  5467.7  922.64
  5497.9  925.98  5588.6  932.62  5710.7  936.99  5789.9  938.48  5937.2  946.11
#Mann=8,-1,0
  4163.1    0.05       0  4587.6    0.16       0  4784.1    0.05       0
  4997.0   0.035       0  5003.0    0.05       0  5092.3     0.1       0
  5272.7    0.16       0  5710.7     0.1       0
Bank Sta=4997,5003
Exp/Cntr=0.3,0.1

Type RM Length L Ch R = 1,193,0,0,0
BEGIN DESCRIPTION:
UNT 1041 IN LATR 1.0
END DESCRIPTION:
XS GIS Cut Line= 4
      2944543.21     10085599.84      2944789.62     10084740.74
      2944654.20     10084525.41      2943122.93     10084398.91
#Sta/Elev= 30
  3976.7  940.35  4048.3  939.39  4388.8  931.90  4564.8  919.90  4699.4  912.95
  4784.1  906.01  4956.3  901.64  4962.2  903.06  4977.5  901.03  4989.7  896.15
  4995.7  894.32  4998.5  893.82  5001.7  894.32  5035.2  903.45  5081.1  901.61
  5130.6  900.73  5170.7  904.47  5230.9  903.03  5341.3  907.99  5401.5  907.46
  5573.7  911.31  5672.4  916.84  5722.6  916.89  5864.4  923.19  6154.0  934.20
  6244.4  933.30  6314.6  937.51  6454.5  940.65  6576.3  944.92  6661.3  949.12
#Mann=10,-1,0
  3976.7    0.05       0  4048.3     0.1       0  4564.8    0.05       0
  4989.7     0.1       0  4995.7   0.035       0  5001.7     0.1       0
  5081.1     0.1       0  5864.4    0.16       0  6454.5     0.1       0
  6576.3    0.05       0
Bank Sta=4995.7,5001.7
Exp/Cntr=0.3,0.1

Chan Stop Cuts=-1