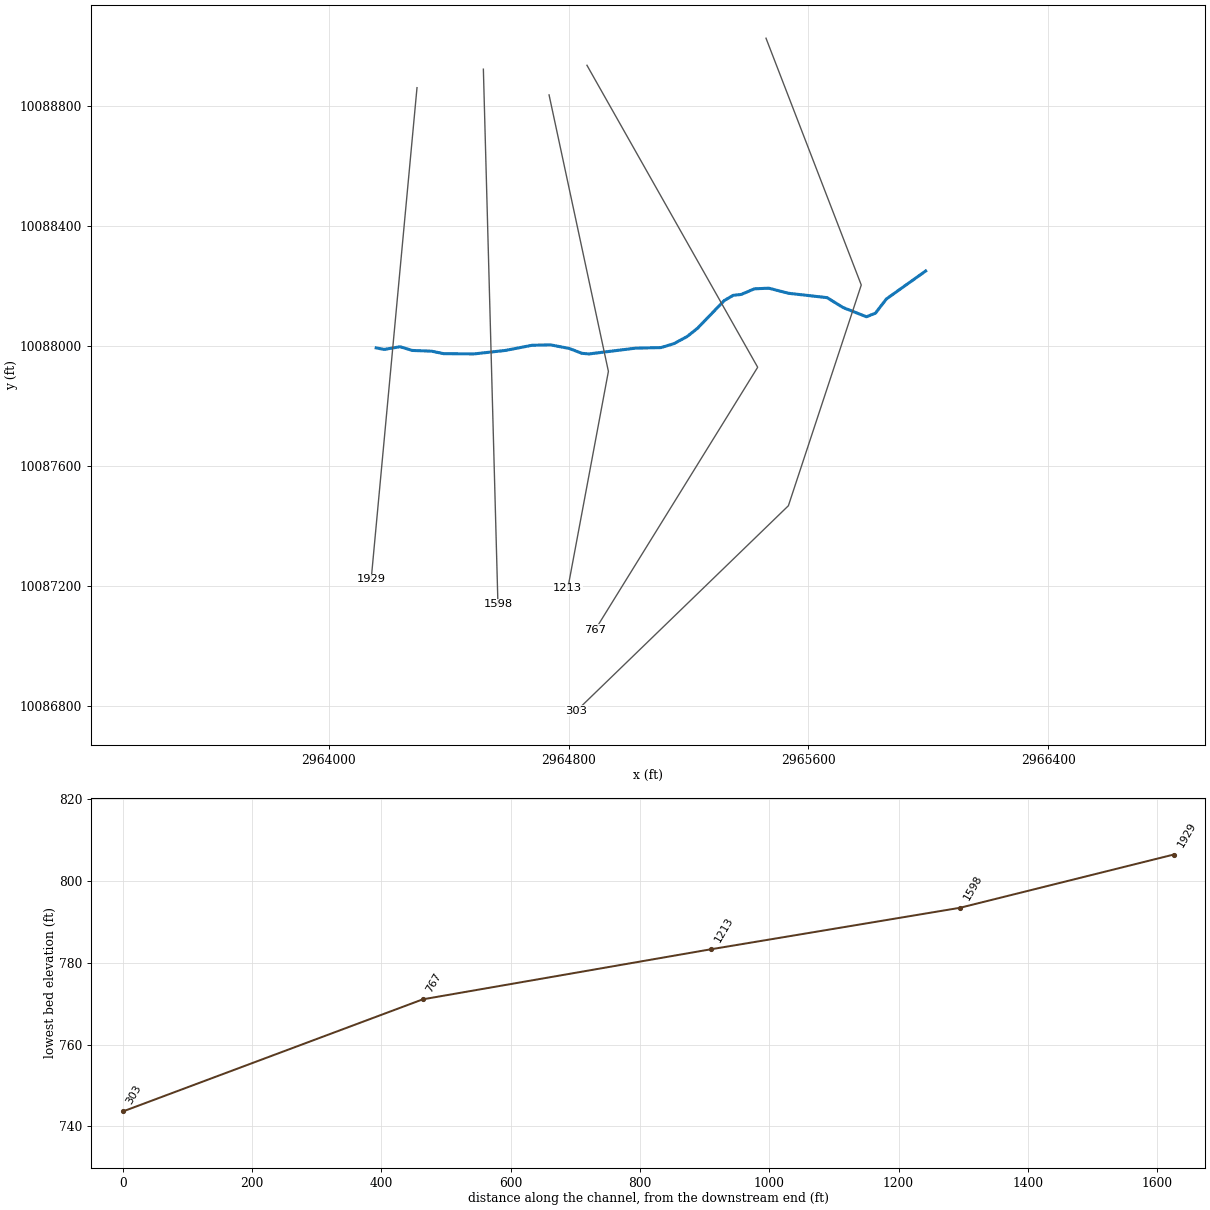
--- UNT 0042 IN LATR.prj (project) ---

Proj Title=UNT 1042 IN LATR Base Level Engineering
Current Plan=p01
Default Exp/Contr=0.3,0.1
English Units
Geom File=g01
Flow File=f01
Plan File=p01
Y Axis Title=Elevation
X Axis Title(PF)=Main Channel Distance
X Axis Title(XS)=Station
BEGIN DESCRIPTION:
UNT 1042 IN LATR
END DESCRIPTION:
DSS Export Rating Curves= 0
DSS Export Rating Curve Sorted= 0
DSS Export Volume Flow Curves= 0
DXF OffsetX= 0
DXF OffsetY= 0
DXF ScaleX= 1
DXF ScaleY= 10

--- UNT 0042 IN LATR.p01 (plan) ---

Plan Title=Multiple Run
Short Identifier=Multiple
Geom File=g01
Flow File=f01
Subcritical Flow
K Sum by GR= 0
Std Step Tol= 0.01
Critical Tol= 0.01
Num of Std Step Trials= 20
Max Error Tol= 0.3
Flow Tol Ratio= 0.001
Split Flow NTrial= 30
Split Flow Tol= 0.02
Split Flow Ratio= 0.02
Log Output Level= 0
Friction Slope Method= 1
Unsteady Friction Slope Method= 2
Unsteady Bridges Friction Slope Method= 1
Parabolic Critical Depth
Global Vel Dist=  1 , 1 , 1
Global Log Level= 0
CheckData=True
Encroach Param= -1, 0, 0, 0
BEGIN DESCRIPTION:
Multiple Run
END DESCRIPTION:

--- UNT 0042 IN LATR.f01 (steady flow) ---

Flow Title=Multiple
Number of Profiles=7
Profile Names=10-year,25-year,50-year,1pct_min,100-year,1pct_plu,500-year
River Rch & RM= UNT 1042 IN LATR,Reach-1,1929
    1054    1558    2005    1890    2556    3457    4170
Boundary for River Rch & Prof#=UNT 1042 IN LATR,Reach-1,1
Up Type=0
Dn Type=3
Dn Slope=0.005
Boundary for River Rch & Prof#=UNT 1042 IN LATR,Reach-1,2
Up Type=0
Dn Type=3
Dn Slope=0.005
Boundary for River Rch & Prof#=UNT 1042 IN LATR,Reach-1,3
Up Type=0
Dn Type=3
Dn Slope=0.005
Boundary for River Rch & Prof#=UNT 1042 IN LATR,Reach-1,4
Up Type=0
Dn Type=3
Dn Slope=0.005
Boundary for River Rch & Prof#=UNT 1042 IN LATR,Reach-1,5
Up Type=0
Dn Type=3
Dn Slope=0.005
Boundary for River Rch & Prof#=UNT 1042 IN LATR,Reach-1,6
Up Type=0
Dn Type=3
Dn Slope=0.005
Boundary for River Rch & Prof#=UNT 1042 IN LATR,Reach-1,7
Up Type=0
Dn Type=3
Dn Slope=0.005

--- UNT 0042 IN LATR.g01 (geometry) ---

Geom Title=Existing Conditions
Program Version=4.10

River Reach=UNT 1042 IN LATR,Reach-1
Reach XY= 30
      2964158.47     10087993.73       2964184.8      10087988.6
      2964238.23     10087997.61      2964278.93     10087985.22
      2964343.08     10087982.83      2964383.32     10087974.54
      2964484.61     10087973.67      2964588.54     10087985.16
      2964678.54     10088002.52      2964739.87     10088003.88
      2964802.69      10087991.8      2964844.36     10087975.62
       2964868.4     10087973.65      2965023.18     10087992.84
      2965108.46      10087994.8      2965151.48     10088007.86
      2965194.87     10088031.21      2965230.02     10088059.07
      2965319.42     10088151.68      2965349.34     10088169.01
      2965375.66     10088171.94      2965419.74     10088190.73
      2965467.86     10088192.82      2965533.99     10088175.84
      2965662.45     10088161.28      2965715.71     10088128.28
      2965793.53     10088097.61      2965823.66     10088109.59
      2965860.12      10088156.9      2965991.03     10088250.12

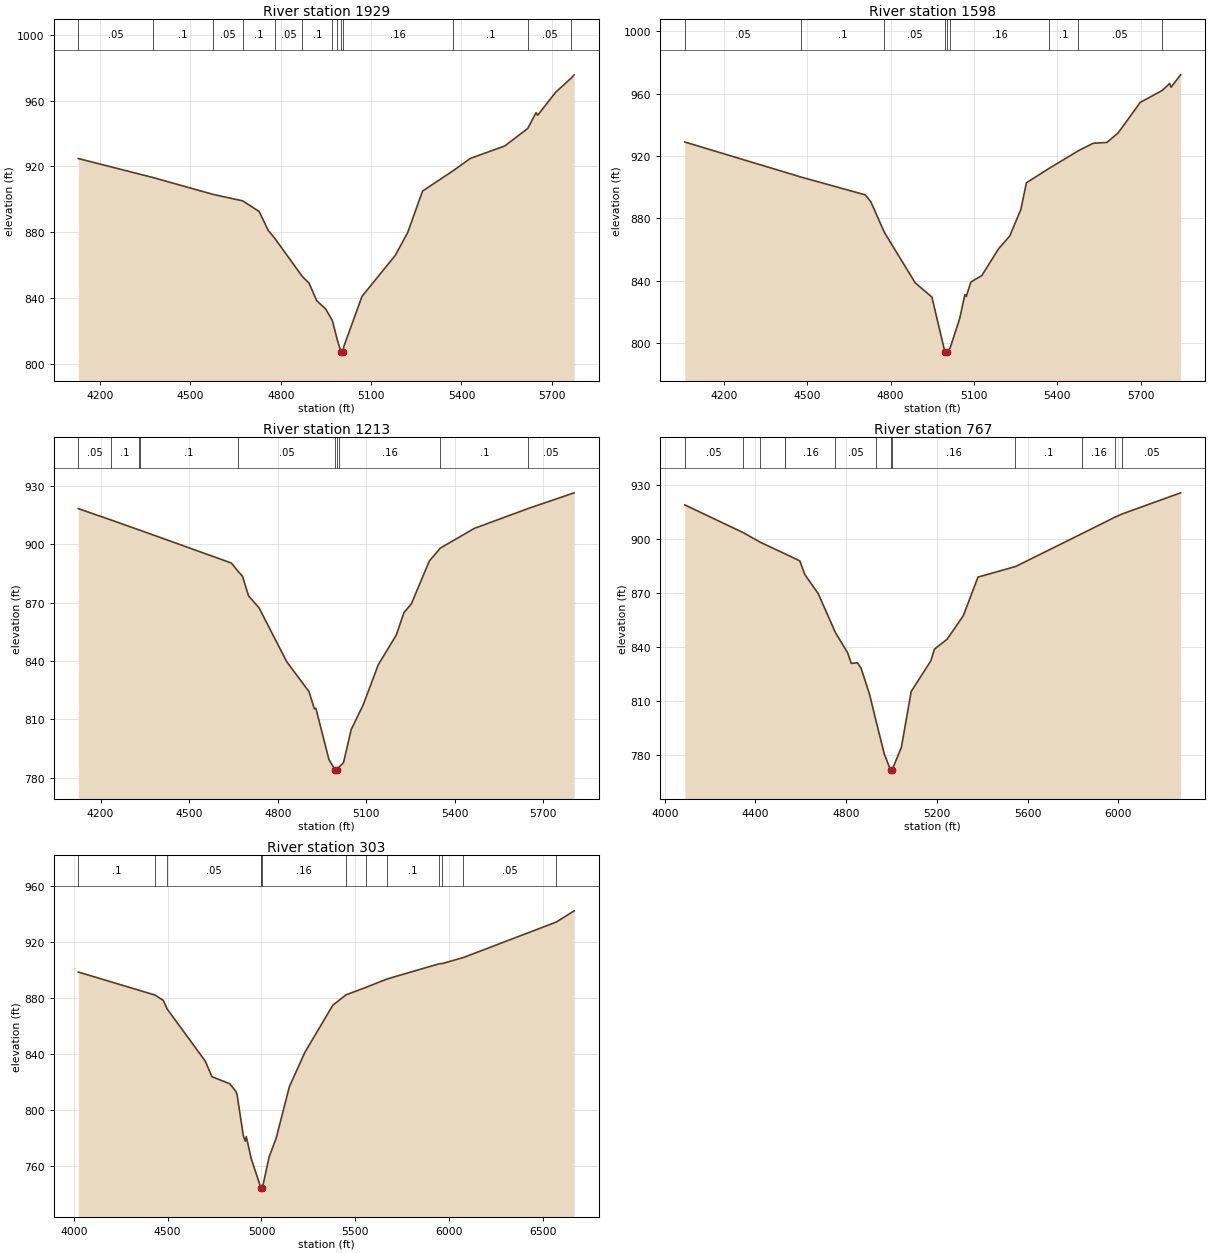
Type RM Length L Ch R = 1 ,1929    ,331,331,331
BEGIN DESCRIPTION:
UNT 1042 IN LATR 4.0
END DESCRIPTION:
XS GIS Cut Line= 2
      2964294.56      10088861.5      2964141.78     10087222.61
#Sta/Elev= 30
  4128.2  924.73  4376.5  913.16  4574.8  902.97    4674  898.99  4728.6  892.54
  4758.7     881  4780.1  876.31  4872.3   852.9  4894.2     849  4919.4  838.36
  4949.5  833.26  4971.4  826.32  4988.2  814.32  5000.3  806.95  5003.1  806.45
  5006.3  806.95  5009.8  810.62    5070  840.97  5180.5  865.91  5221.5   879.7
  5270.9  904.96  5371.8  917.23  5429.7  924.82  5543.8  932.36  5620.1  943.02
  5647.9  952.63  5652.9  950.97  5712.8  965.02  5764.7  973.67  5774.2  975.61
#Mann= 13 ,-1 , 0
  4128.2     .05       0  4376.5      .1       0  4574.8     .05       0
    4674      .1       0  4780.1     .05       0  4872.3      .1       0
  4971.4     .05       0  4988.2     .16       0  5000.3     .07       0
  5006.3     .16       0  5371.8      .1       0  5620.1     .05       0
  5764.7     .16       0
Bank Sta=5000.3,5006.3
XS Rating Curve= 0 ,0
Exp/Cntr=0.3,0.1

Type RM Length L Ch R = 1 ,1598    ,385,385,385
BEGIN DESCRIPTION:
UNT 1042 IN LATR 3.0
END DESCRIPTION:
XS GIS Cut Line= 2
      2964515.91     10088923.15      2964564.52     10087138.61
#Sta/Elev= 30
  4058.9     929  4477.1  906.52  4708.6  895.06  4728.6  890.66  4777.6  870.94
  4888.6  838.54  4948.6  829.43  4995.7  793.93  4998.4  793.43  5001.7  793.93
  5013.7  796.51  5048.7  815.65  5067.3  831.05  5072.3  829.78  5088.7  839.02
  5128.7  843.33  5188.7  860.45  5228.7   868.6  5268.8  885.62  5288.8  902.81
    5370  912.01  5476.1  923.41  5528.9  928.16  5578.9  928.75  5618.9  934.78
  5698.9  954.46  5777.5  962.06  5804.7  966.62  5809.7  964.22  5844.1  972.14
#Mann= 9 ,-1 , 0
  4058.9     .05       0  4477.1      .1       0  4777.6     .05       0
  4995.7    .035       0  5001.7     .05       0  5013.7     .16       0
    5370      .1       0  5476.1     .05       0  5777.5     .16       0
Bank Sta=4995.7,5001.7
XS Rating Curve= 0 ,0
Exp/Cntr=0.3,0.1

Type RM Length L Ch R = 1 ,1213    ,446,446,446
BEGIN DESCRIPTION:
Mapping XS 6d9163bb
END DESCRIPTION:
XS GIS Cut Line= 3
      2964735.02      10088837.4      2964932.95     10087915.48
      2964797.54     10087191.56
#Sta/Elev= 30
  4124.7  918.34    4235  912.53  4331.4  907.34  4334.8  907.17  4643.1  890.36
  4665.1  886.18  4680.8  883.58  4701.2  873.47  4736.8  867.31  4830.5   839.6
  4905.8  824.26  4924.1  815.37  4929.3  815.61  4973.5  789.29  4994.8   783.8
  4997.6   783.3  5000.8   783.8  5007.6  785.31  5022.9  787.68    5049  804.72
  5089.7  817.43  5140.6  838.04  5201.7  853.32  5227.5  864.85  5252.5   869.3
  5313.6   891.4  5351.2  898.08  5466.2  908.19  5649.2  918.44  5804.1  926.47
#Mann= 10 ,-1 , 0
  4124.7     .05       0    4235      .1       0  4331.4     .05       0
  4334.8      .1       0  4665.1     .05       0  4994.8    .035       0
  5000.8     .05       0  5007.6     .16       0  5351.2      .1       0
  5649.2     .05       0
Bank Sta=4994.8,5000.8
XS Rating Curve= 0 ,0
Exp/Cntr=0.3,0.1

Type RM Length L Ch R = 1 ,767     ,464,464,464
BEGIN DESCRIPTION:
UNT 1042 IN LATR 2.0
END DESCRIPTION:
XS GIS Cut Line= 3
      2964861.39     10088936.16      2965430.84     10087929.19
      2964889.19     10087054.22
#Sta/Elev= 30
  4088.6  919.16    4347  903.68  4421.8  898.37  4532.1  891.83  4595.9  887.99
  4617.6  880.43  4676.8  869.83  4752.8   848.1  4806.6  836.88  4822.5     831
  4849.9  831.33  4865.8   828.3  4903.4  813.65    4933  798.29  4968.3  780.53
    4996  771.56  4998.7  771.06    5002  771.56  5043.4  784.31  5086.7  815.38
  5173.3  832.41  5189.2  838.89  5245.4   844.5  5316.5  857.51  5381.2  879.01
  5546.5  884.86  5841.3  903.28  5984.1  912.27  6016.5   914.1  6274.5  925.87
#Mann= 13 ,-1 , 0
  4088.6     .05       0    4347      .1       0  4421.8     .05       0
  4532.1      .1       0  4532.1     .16       0  4752.8     .05       0
    4933     .16       0    4996     .07       0    5002     .16       0
  5546.5      .1       0  5841.3     .16       0  5984.1      .1       0
  6016.5     .05       0
Bank Sta=4996,5002
XS Rating Curve= 0 ,0
Exp/Cntr=0.3,0.1

Type RM Length L Ch R = 1 ,303     ,0,0,0
BEGIN DESCRIPTION:
UNT 1042 IN LATR 1.0
END DESCRIPTION:
XS GIS Cut Line= 4
      2965458.62     10089026.41      2965776.33      10088203.5
      2965533.27     10087467.39      2964826.65     10086783.34
#Sta/Elev= 30
  4024.5  898.59  4432.6  882.18  4477.2  878.34  4497.8  872.19  4700.8  834.98
  4736.1  823.89  4831.3  818.84  4863.5  813.41  4869.9  811.11  4903.8   781.4
  4913.7  777.88    4919  781.19  4945.4  765.42  4997.1  744.39  4998.1  744.16
  5000.9  743.66  5004.1  744.16  5040.7  766.58  5077.7  779.81  5148.6  816.76
  5231.1  841.28  5380.3  874.98  5450.2  882.32  5555.2  887.58  5668.7  893.63
  5947.1   904.5  5962.9  904.65  6074.1  908.87  6570.4  934.27  6665.3  942.27
#Mann= 13 ,-1 , 0
  4024.5      .1       0  4432.6     .16       0  4497.8     .05       0
  4997.1     .16       0  4998.1     .07       0  5004.1     .16       0
  5450.2      .1       0  5555.2     .05       0  5668.7      .1       0
  5947.1     .16       0  5962.9      .1       0  6074.1     .05       0
  6570.4      .1       0
Bank Sta=4998.1,5004.1
XS Rating Curve= 0 ,0
Exp/Cntr=0.3,0.1

Chan Stop Cuts=-1
Use User Specified Reach Order=0
Composite Channel Slope=5