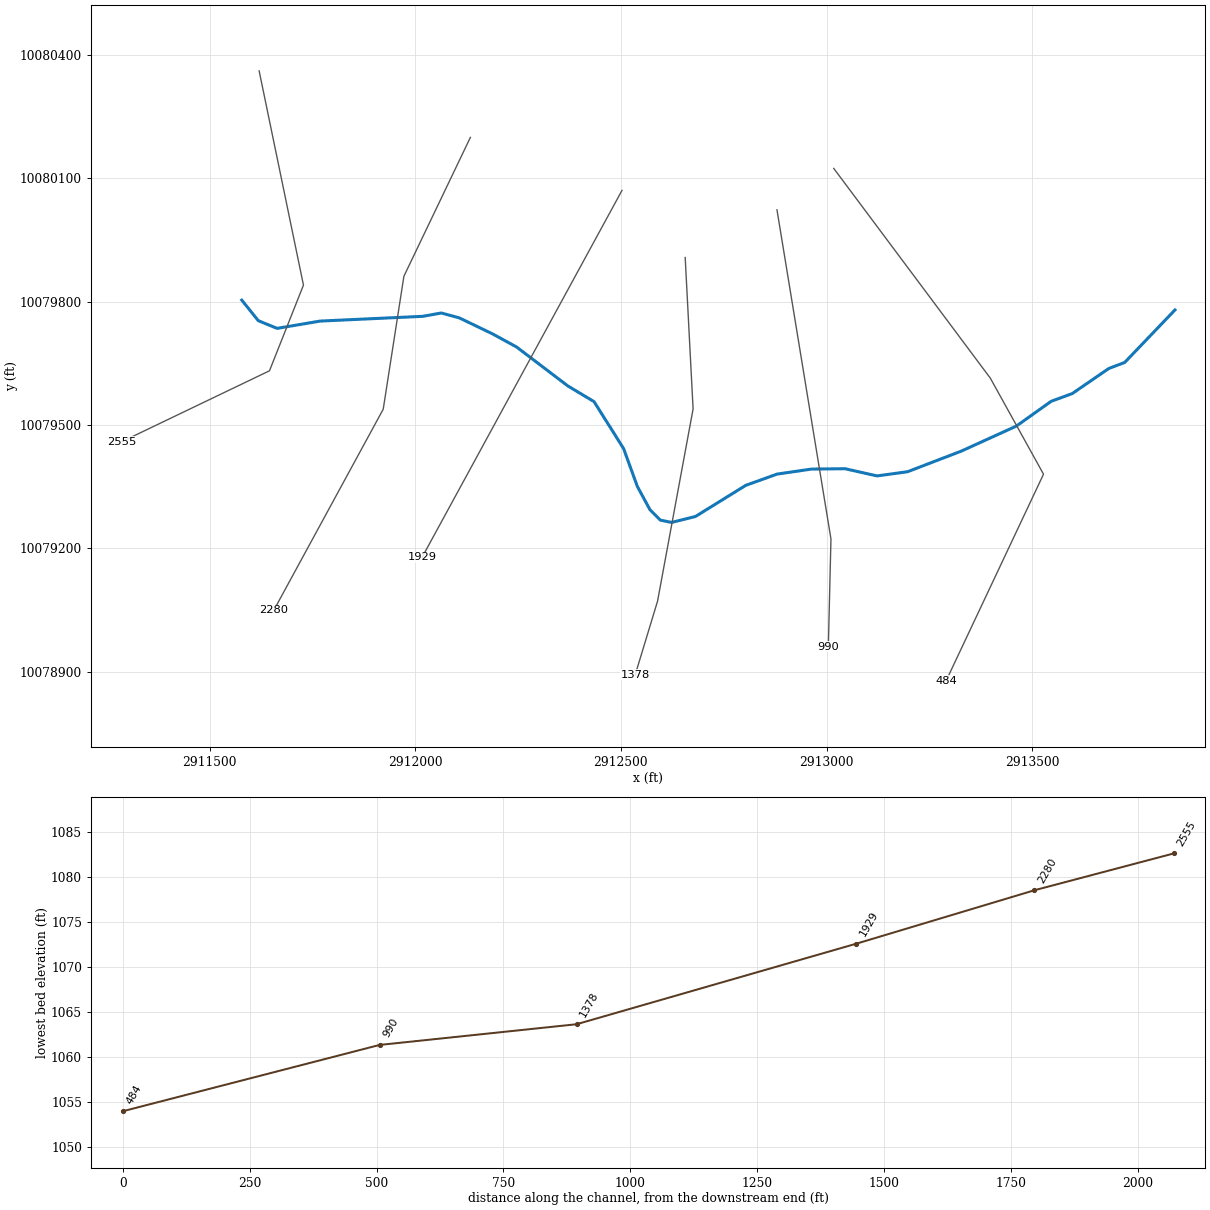
--- UNT 0043 IN LATR.prj (project) ---

Proj Title=UNT 1043 IN LATR Base Level Engineering
Current Plan=p01
Default Exp/Contr=0.3,0.1
English Units
Geom File=g01
Flow File=f01
Plan File=p01
BEGIN DESCRIPTION:
UNT 1043 IN LATR
END DESCRIPTION:

--- UNT 0043 IN LATR.p01 (plan) ---

Plan Title=Multiple Run
Short Identifier=Multiple
Geom File=g01
Flow File=f01
Subcritical Flow
K Sum by GR= 0
Std Step Tol= 0.01
Critical Tol= 0.01
Num of Std Step Trials= 20
Max Error Tol= 0.3
Flow Tol Ratio= 0.001
Split Flow NTrial= 30
Split Flow Tol= 0.02
Split Flow Ratio= 0.02
Log Output Level= 0
Friction Slope Method= 1
Unsteady Friction Slope Method= 2
Unsteady Bridges Friction Slope Method= 1
Parabolic Critical Depth
Global Vel Dist=  1 , 1 , 1
Global Log Level= 0
CheckData=True
Encroach Param= -1, 0, 0, 0
BEGIN DESCRIPTION:
Multiple Run
END DESCRIPTION:

--- UNT 0043 IN LATR.f01 (steady flow) ---

Flow Title=Multiple
Number of Profiles=7
Profile Names=10-year,25-year,50-year,1pct_min,100-year,1pct_plu,500-year
River Rch & RM= UNT 1043 IN LATR,Reach-1,2555
     812    1168    1474    1363    1843    2493    2891
Boundary for River Rch & Prof#=UNT 1043 IN LATR,Reach-1,1
Up Type=0
Dn Type=3
Dn Slope=0.005
Boundary for River Rch & Prof#=UNT 1043 IN LATR,Reach-1,2
Up Type=0
Dn Type=3
Dn Slope=0.005
Boundary for River Rch & Prof#=UNT 1043 IN LATR,Reach-1,3
Up Type=0
Dn Type=3
Dn Slope=0.005
Boundary for River Rch & Prof#=UNT 1043 IN LATR,Reach-1,4
Up Type=0
Dn Type=3
Dn Slope=0.005
Boundary for River Rch & Prof#=UNT 1043 IN LATR,Reach-1,5
Up Type=0
Dn Type=3
Dn Slope=0.005
Boundary for River Rch & Prof#=UNT 1043 IN LATR,Reach-1,6
Up Type=0
Dn Type=3
Dn Slope=0.005
Boundary for River Rch & Prof#=UNT 1043 IN LATR,Reach-1,7
Up Type=0
Dn Type=3
Dn Slope=0.005

--- UNT 0043 IN LATR.g01 (geometry) ---

Geom Title=Existing Conditions

River Reach=UNT 1043 IN LATR,Reach-1
Reach XY= 30
      2911578.47     10079803.73      2911618.53     10079753.83
      2911664.20     10079735.10      2911769.04     10079752.79
      2912018.25     10079764.34      2912063.57     10079772.44
      2912107.09     10079760.65      2912187.72     10079721.84
      2912246.36     10079689.91      2912370.99     10079595.22
      2912434.77     10079557.01      2912506.63     10079442.96
      2912540.12     10079350.77      2912570.75     10079294.27
      2912595.90     10079268.91      2912623.22     10079263.34
      2912681.39     10079277.76      2912803.60     10079353.41
      2912879.69     10079380.77      2912963.24     10079392.99
      2913044.83     10079393.88      2913122.96     10079376.37
      2913197.22     10079386.62      2913327.30     10079436.54
      2913461.58     10079497.59      2913546.20     10079557.82
      2913597.31     10079576.52      2913686.30     10079637.57
      2913724.91     10079652.27      2913847.05     10079779.83

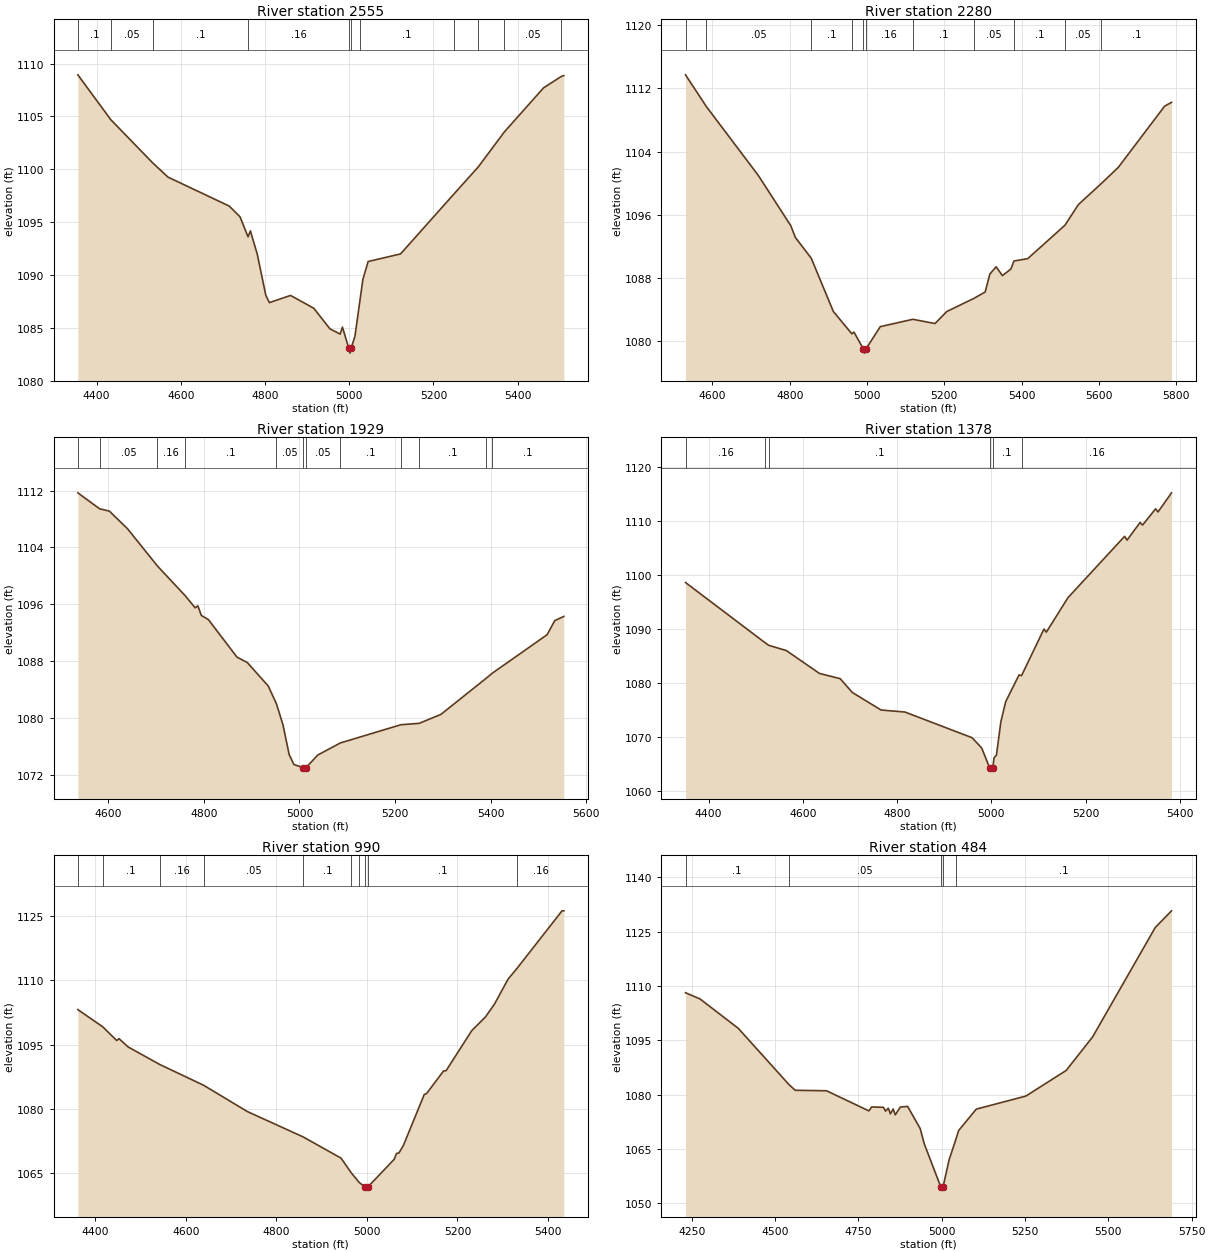
Type RM Length L Ch R = 1,2555,275,275,275
BEGIN DESCRIPTION:
UNT 1043 IN LATR 5.0
END DESCRIPTION:
XS GIS Cut Line= 4
      2911620.65     10080360.97      2911728.39     10079840.23
      2911645.80     10079631.95      2911286.66     10079459.56
#Sta/Elev= 30
  4355.4 1108.94  4433.8 1104.69  4533.3 1100.60  4569.4 1099.26  4714.9 1096.52
  4740.6 1095.50  4759.6 1093.61  4765.2 1094.17  4781.5 1091.97  4801.9 1088.06
  4810.3 1087.38  4860.5 1088.06  4915.7 1086.85  4954.1 1084.90  4978.4 1084.40
  4983.8 1085.06  4998.7 1083.10  5001.5 1082.60  5004.7 1083.10  5013.5 1084.19
  5024.9 1087.45  5032.4 1089.58  5044.8 1091.27  5121.8 1091.99  5248.6 1097.66
  5306.7 1100.24  5368.4 1103.54  5461.5 1107.71  5503.6 1108.79  5509.6 1108.87
#Mann=11,-1,0
  4355.4     0.1       0  4433.8    0.05       0  4533.3     0.1       0
  4759.6    0.16       0  4998.7    0.07       0  5004.7    0.16       0
  5024.9     0.1       0  5248.6    0.05       0  5306.7     0.1       0
  5368.4    0.05       0  5503.6     0.1       0
Bank Sta=4998.7,5004.7
Exp/Cntr=0.3,0.1

Type RM Length L Ch R = 1,2280,351,351,351
BEGIN DESCRIPTION:
Mapping XS d8ed1ba7
END DESCRIPTION:
XS GIS Cut Line= 4
      2912134.20     10080199.36      2911972.58     10079861.78
      2911922.31     10079538.58      2911656.55     10079050.16
#Sta/Elev= 30
  4530.4 1113.70  4583.8 1109.72  4718.5 1100.99  4802.7 1094.62  4814.7 1093.12
  4855.6 1090.51  4912.8 1083.77  4960.7 1080.94  4966.2 1081.16  4990.8 1079.00
  4993.5 1078.50  4996.8 1079.00  5034.3 1081.85  5118.6 1082.78  5175.9 1082.24
  5206.3 1083.76  5276.4 1085.42  5305.6 1086.23  5317.8 1088.51  5334.0 1089.42
  5350.2 1088.31  5372.0 1089.12  5380.1 1090.15  5415.7 1090.45  5512.1 1094.68
  5546.8 1097.29  5605.5 1099.92  5650.3 1102.01  5770.0 1109.74  5787.8 1110.22
#Mann=11,-1,0
  4530.4     0.1       0  4583.8    0.05       0  4855.6     0.1       0
  4960.7    0.16       0  4990.8    0.07       0  4996.8    0.16       0
  5118.6     0.1       0  5276.4    0.05       0  5380.1     0.1       0
  5512.1    0.05       0  5605.5     0.1       0
Bank Sta=4990.8,4996.8
Exp/Cntr=0.3,0.1

Type RM Length L Ch R = 1,1929,551,551,551
BEGIN DESCRIPTION:
UNT 1043 IN LATR 4.0
END DESCRIPTION:
XS GIS Cut Line= 2
      2912502.79     10080070.57      2912016.58     10079178.12
#Sta/Elev= 30
  4536.5 1111.68  4581.9 1109.44  4602.4 1109.11  4640.3 1106.64  4703.0 1101.39
  4760.7 1097.24  4781.8 1095.52  4787.5 1095.79  4794.8 1094.44  4809.4 1093.87
  4869.2 1088.59  4891.0 1087.82  4934.7 1084.52  4951.8 1082.03  4965.6 1079.04
  4978.4 1074.89  4988.4 1073.48  5007.7 1073.06  5010.4 1072.56  5013.7 1073.06
  5038.2 1074.82  5085.4 1076.52  5212.0 1079.08  5250.5 1079.28  5295.9 1080.54
  5390.9 1085.64  5403.5 1086.34  5517.7 1091.73  5533.9 1093.72  5552.8 1094.31
#Mann=12,-1,0
  4536.5    0.16       0  4581.9    0.05       0  4703.0    0.16       0
  4760.7     0.1       0  4951.8    0.05       0  5007.7   0.035       0
  5013.7    0.05       0  5085.4     0.1       0  5212.0    0.05       0
  5250.5     0.1       0  5390.9    0.05       0  5403.5     0.1       0
Bank Sta=5007.7,5013.7
Exp/Cntr=0.3,0.1

Type RM Length L Ch R = 1,1378,388,388,388
BEGIN DESCRIPTION:
UNT 1043 IN LATR 3.0
END DESCRIPTION:
XS GIS Cut Line= 4
      2912656.41     10079907.33      2912675.62     10079539.19
      2912589.20     10079071.86      2912534.79     10078892.63
#Sta/Elev= 30
  4351.0 1098.57  4520.6 1087.36  4527.7 1086.93  4564.9 1085.96  4635.0 1081.73
  4679.1 1080.75  4705.1 1078.18  4765.9 1074.94  4816.7 1074.56  4959.1 1069.80
  4979.4 1067.90  4996.8 1064.11  4999.5 1063.61  5002.8 1064.11  5005.6 1066.09
  5010.7 1066.57  5020.1 1072.76  5030.3 1076.47  5058.6 1081.44  5064.0 1081.32
  5111.5 1089.94  5116.6 1089.37  5162.5 1095.77  5282.6 1107.13  5287.8 1106.43
  5315.5 1109.71  5320.7 1109.22  5348.4 1112.23  5353.6 1111.66  5382.2 1115.20
#Mann=6,-1,0
  4351.0    0.16       0  4520.6    0.05       0  4527.7     0.1       0
  4996.8    0.07       0  5002.8     0.1       0  5064.0    0.16       0
Bank Sta=4996.8,5002.8
Exp/Cntr=0.3,0.1

Type RM Length L Ch R = 1,990,506,506,506
BEGIN DESCRIPTION:
UNT 1043 IN LATR 2.0
END DESCRIPTION:
XS GIS Cut Line= 3
      2912879.54     10080023.28      2913010.78     10079223.09
      2913004.38     10078960.65
#Sta/Elev= 30
  4361.5 1103.16  4416.4 1099.16  4447.4 1095.95  4452.4 1096.39  4472.5 1094.46
  4542.2 1090.38  4639.5 1085.51  4736.0 1079.39  4859.2 1073.48  4942.8 1068.53
  4965.9 1065.04  4983.5 1062.81  4996.0 1061.81  4998.8 1061.31  5002.0 1061.81
  5060.3 1068.27  5065.4 1069.66  5070.4 1069.69  5080.5 1071.49  5126.7 1083.40
  5131.7 1083.58  5169.5 1088.89  5174.6 1088.89  5231.8 1098.30  5261.8 1101.45
  5281.8 1104.47  5311.8 1110.28  5331.4 1112.76  5430.9 1126.19  5434.9 1126.19
#Mann=10,-1,0
  4361.5    0.16       0  4416.4     0.1       0  4542.2    0.16       0
  4639.5    0.05       0  4859.2     0.1       0  4965.9    0.05       0
  4983.5     0.1       0  4996.0    0.07       0  5002.0     0.1       0
  5331.4    0.16       0
Bank Sta=4996,5002
Exp/Cntr=0.3,0.1

Type RM Length L Ch R = 1,484,0,0,0
BEGIN DESCRIPTION:
UNT 1043 IN LATR 1.0
END DESCRIPTION:
XS GIS Cut Line= 4
      2913017.61     10080123.89      2913398.24     10079613.99
      2913527.52     10079380.58      2913290.74     10078878.31
#Sta/Elev= 30
  4231.2 1108.14  4274.7 1106.43  4389.4 1098.33  4541.6 1082.80  4560.4 1081.22
  4654.2 1081.09  4781.3 1075.54  4789.7 1076.62  4825.1 1076.52  4831.4 1075.46
  4839.7 1076.28  4846.0 1074.73  4854.3 1076.07  4860.6 1074.44  4875.9 1076.60
  4897.7 1076.77  4935.4 1070.65  4947.8 1066.40  4997.7 1054.44  5000.4 1053.94
  5003.7 1054.44  5022.4 1062.10  5041.6 1067.42  5050.7 1070.11  5103.7 1076.02
  5252.4 1079.62  5373.4 1086.69  5452.8 1095.95  5640.6 1126.12  5689.6 1130.75
#Mann=5,-1,0
  4231.2     0.1       0  4541.6    0.05       0  4997.7   0.035       0
  5003.7    0.05       0  5041.6     0.1       0
Bank Sta=4997.7,5003.7
Exp/Cntr=0.3,0.1

Chan Stop Cuts=-1