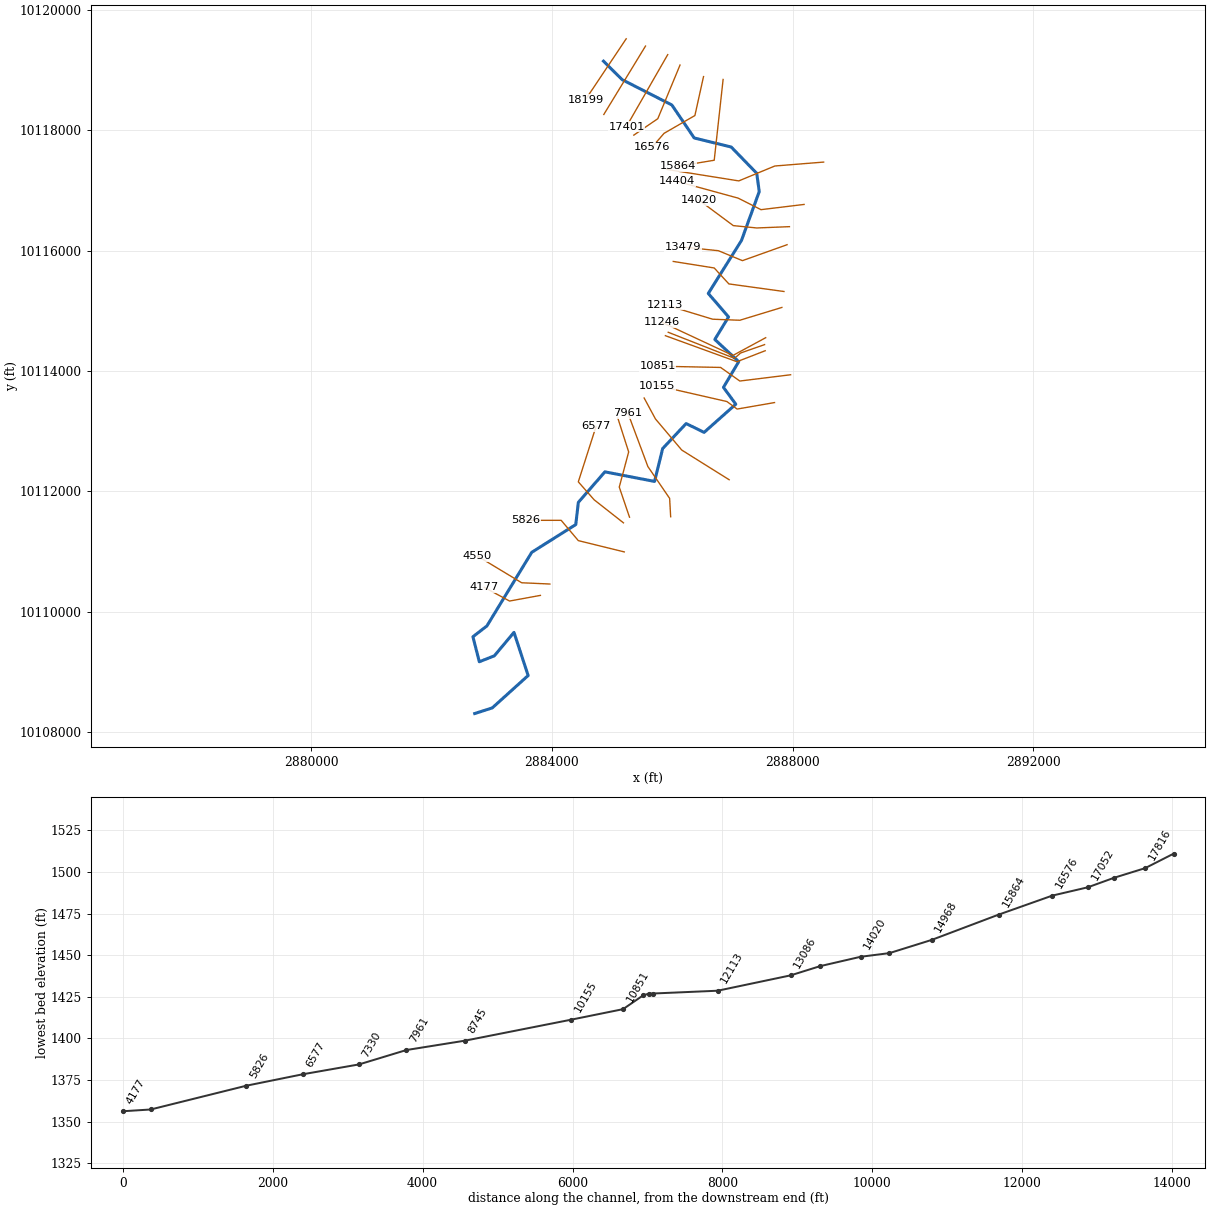
--- UNT 0044 IN LATR.prj (project) ---

Proj Title=UNT 1044 IN LATR Base Level Engineering
Current Plan=p01
Default Exp/Contr=0.3,0.1
English Units
Geom File=g01
Flow File=f01
Plan File=p01
Y Axis Title=Elevation
X Axis Title(PF)=Main Channel Distance
X Axis Title(XS)=Station
BEGIN DESCRIPTION:
UNT 1044 IN LATR
END DESCRIPTION:
DSS Export Rating Curves= 0
DSS Export Rating Curve Sorted= 0
DSS Export Volume Flow Curves= 0
DXF OffsetX= 0
DXF OffsetY= 0
DXF ScaleX= 1
DXF ScaleY= 10

--- UNT 0044 IN LATR.p01 (plan) ---

Plan Title=Multiple Run
Short Identifier=Multiple
Geom File=g01
Flow File=f01
Subcritical Flow
K Sum by GR= 0
Std Step Tol= 0.01
Critical Tol= 0.01
Num of Std Step Trials= 20
Max Error Tol= 0.3
Flow Tol Ratio= 0.001
Split Flow NTrial= 30
Split Flow Tol= 0.02
Split Flow Ratio= 0.02
Log Output Level= 0
Friction Slope Method= 1
Unsteady Friction Slope Method= 2
Unsteady Bridges Friction Slope Method= 1
Parabolic Critical Depth
Global Vel Dist=  1 , 1 , 1
Global Log Level= 0
CheckData=True
Encroach Param= -1, 0, 0, 0
BEGIN DESCRIPTION:
Multiple Run
END DESCRIPTION:

--- UNT 0044 IN LATR.f01 (steady flow) ---

Flow Title=Multiple
Number of Profiles=7
Profile Names=10-year,25-year,50-year,1pct_min,100-year,1pct_plu,500-year
River Rch & RM= UNT 1044 IN LATR,Reach-1,18199
     887    1300    1662    1558    2106    2849    3396
River Rch & RM= UNT 1044 IN LATR,Reach-1,17401
    1419    2126    2759    2618    3541    4788    5858
River Rch & RM= UNT 1044 IN LATR,Reach-1,12113
    1868    2831    3702    3535    4781    6466    8016
River Rch & RM= UNT 1044 IN LATR,Reach-1,8745
    2107    3193    4173    3981    5383    7281    9004
Boundary for River Rch & Prof#=UNT 1044 IN LATR,Reach-1,1
Up Type=0
Dn Type=3
Dn Slope=0.005
Boundary for River Rch & Prof#=UNT 1044 IN LATR,Reach-1,2
Up Type=0
Dn Type=3
Dn Slope=0.005
Boundary for River Rch & Prof#=UNT 1044 IN LATR,Reach-1,3
Up Type=0
Dn Type=3
Dn Slope=0.005
Boundary for River Rch & Prof#=UNT 1044 IN LATR,Reach-1,4
Up Type=0
Dn Type=3
Dn Slope=0.005
Boundary for River Rch & Prof#=UNT 1044 IN LATR,Reach-1,5
Up Type=0
Dn Type=3
Dn Slope=0.005
Boundary for River Rch & Prof#=UNT 1044 IN LATR,Reach-1,6
Up Type=0
Dn Type=3
Dn Slope=0.005
Boundary for River Rch & Prof#=UNT 1044 IN LATR,Reach-1,7
Up Type=0
Dn Type=3
Dn Slope=0.005

--- UNT 0044 IN LATR.g01 (geometry) ---

Geom Title=Existing Conditions
Program Version=4.10

River Reach=UNT 1044 IN LATR,Reach-1
Reach XY= 30
      2884858.47     10119143.73      2885169.37     10118836.13
      2885994.82     10118416.08      2886365.79      10117868.7
      2886980.99     10117718.44      2887404.64     10117282.15
       2887446.8     10116979.42       2887151.3     10116167.26
      2886599.64     10115287.66      2886936.71     10114898.19
      2886708.25     10114523.79      2887105.83      10114155.7
      2886851.88      10113728.6      2887056.86     10113449.18
      2886530.14     10112981.39      2886231.88     10113127.69
      2885841.55      10112712.4      2885707.15     10112167.04
      2884882.14     10112326.04      2884440.78     10111820.16
      2884397.68     10111451.06      2883666.35     10110990.31
      2882920.56     10109767.45      2882688.66     10109588.51
      2882795.04     10109173.11      2883044.39     10109271.81
      2883371.09     10109661.15       2883606.4     10108944.77
      2883009.87     10108407.13      2882718.47     10108313.73

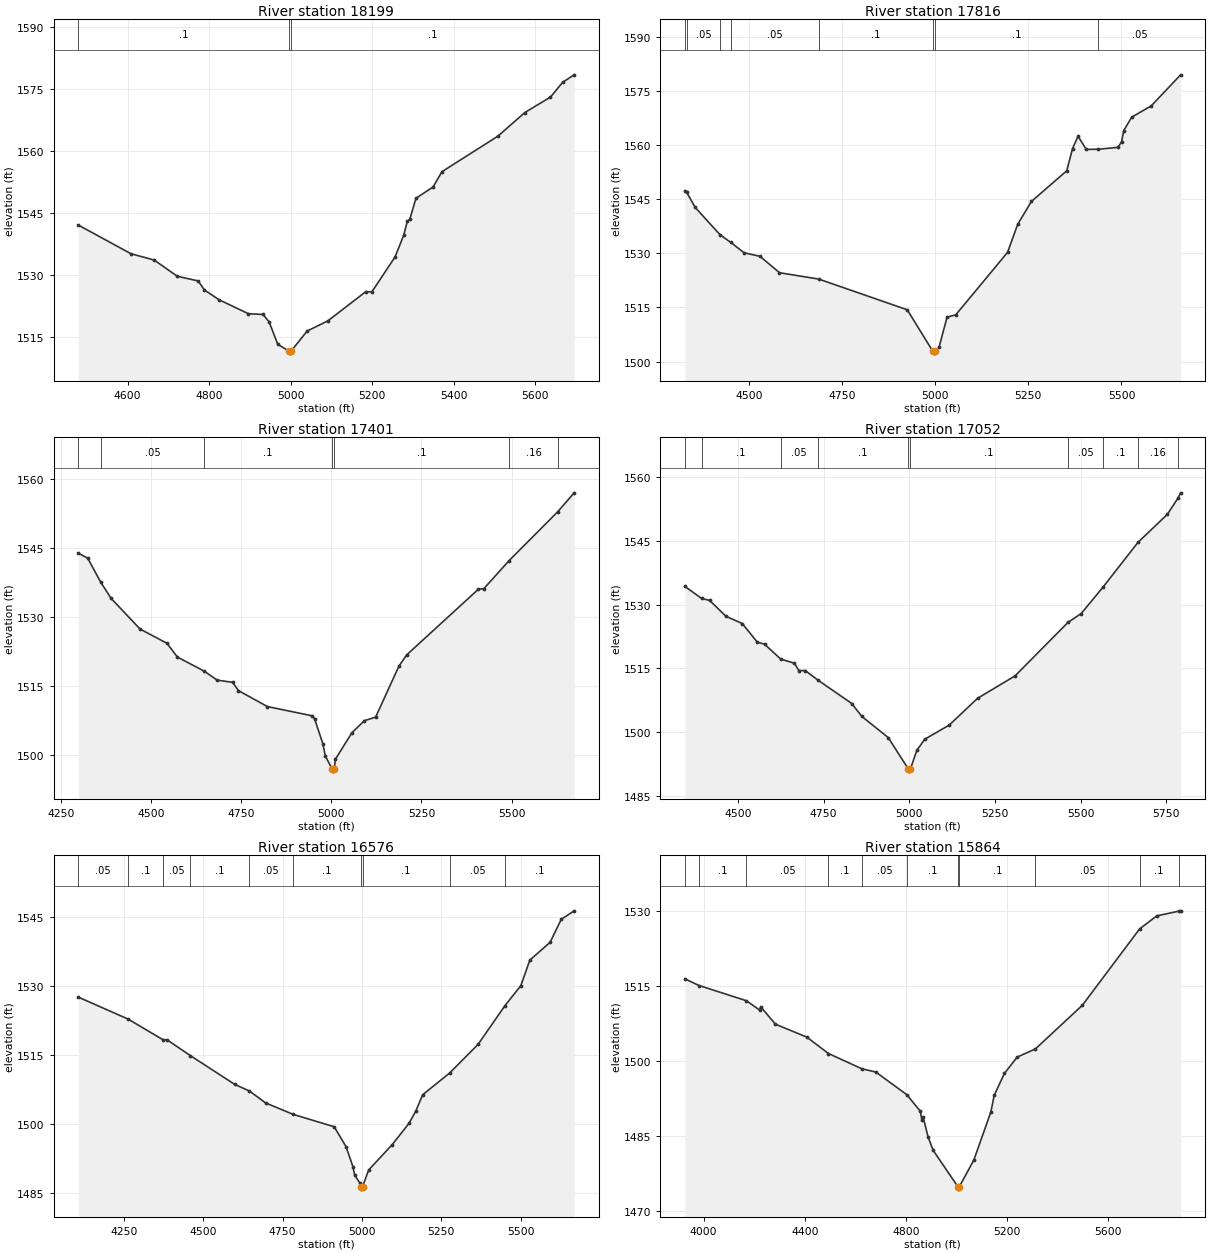
Type RM Length L Ch R = 1 ,18199   ,383,383,383
BEGIN DESCRIPTION:
UNT 1044 IN LATR 37.0
END DESCRIPTION:
XS GIS Cut Line= 2
      2885235.78     10119515.35      2884558.71     10118504.09
#Sta/Elev= 30
    4479 1542.06  4608.1 1535.13  4665.2  1533.6  4722.2 1529.67  4773.3 1528.55
  4788.3 1526.38  4824.3 1524.01  4896.4 1520.63  4932.4 1520.45  4947.4 1518.64
  4968.4 1513.25  4995.4  1511.6  4998.2  1511.1  5001.4  1511.6  5040.5 1516.43
  5091.5  1518.9  5184.6 1525.96  5199.6 1525.92  5256.6 1534.39  5277.6  1539.6
  5286.6 1542.97  5292.6 1543.45  5307.6 1548.52  5349.7 1551.27  5371.5 1554.96
  5508.8 1563.55  5574.8 1569.25  5637.9    1573  5667.9 1576.58    5696 1578.38
#Mann= 3 ,-1 , 0
    4479      .1       0  4995.4     .07       0  5001.4      .1       0
Bank Sta=4995.4,5001.4
XS Rating Curve= 0 ,0
Exp/Cntr=0.3,0.1

Type RM Length L Ch R = 1 ,17816   ,415,415,415
BEGIN DESCRIPTION:
Mapping XS 99899c62
END DESCRIPTION:
XS GIS Cut Line= 2
      2885556.53      10119394.3      2884863.84     10118258.92
#Sta/Elev= 30
  4328.6 1547.18  4333.3 1546.97  4356.1 1542.75  4423.7 1535.07  4451.5 1533.05
  4487.7 1530.13  4530.4 1529.16  4582.6 1524.61  4687.6 1522.86  4925.3 1514.34
    4994 1502.83  4996.7 1502.33    5000 1502.83  5010.5 1503.93  5032.1  1512.3
  5055.5 1512.95  5194.4 1530.26  5221.6 1538.03  5258.3 1544.35  5353.2 1552.87
  5368.6    1559  5383.5 1562.43  5405.4 1558.78  5437.8 1558.83  5490.7 1559.35
  5500.3 1560.92  5506.1 1564.01  5527.4 1567.72  5579.7 1570.84  5658.6 1579.45
#Mann= 8 ,-1 , 0
  4328.6      .1       0  4333.3     .05       0  4423.7      .1       0
  4451.5     .05       0  4687.6      .1       0    4994     .07       0
    5000      .1       0  5437.8     .05       0
Bank Sta=4994,5000
XS Rating Curve= 0 ,0
Exp/Cntr=0.3,0.1

Type RM Length L Ch R = 1 ,17401   ,349,349,349
BEGIN DESCRIPTION:
UNT 1044 IN LATR 36.0
END DESCRIPTION:
XS GIS Cut Line= 2
      2885925.89     10119252.34       2885240.1     10118058.72
#Sta/Elev= 30
  4297.3 1543.98  4323.4 1542.86  4359.2 1537.68  4388.1 1534.14  4468.7 1527.44
  4543.3 1524.36  4572.5 1521.34  4646.7 1518.29  4682.8 1516.33  4725.9 1515.85
  4741.7 1514.06  4822.3 1510.58  4945.9 1508.58  4953.1 1507.95  4976.1 1502.51
  4983.3 1499.77  5001.9 1497.03  5004.6 1496.53  5007.9 1497.03  5010.7 1499.08
  5056.9 1504.89  5091.5 1507.51  5122.7 1508.28  5187.4 1519.38    5209 1521.83
  5407.4 1536.07  5423.2 1536.24  5493.5 1542.36    5628 1552.95  5673.9 1557.09
#Mann= 7 ,-1 , 0
  4297.3      .1       0  4359.2     .05       0  4646.7      .1       0
  5001.9     .07       0  5007.9      .1       0  5493.5     .16       0
    5628     .05       0
Bank Sta=5001.9,5007.9
XS Rating Curve= 0 ,0
Exp/Cntr=0.3,0.1

Type RM Length L Ch R = 1 ,17052   ,476,476,476
BEGIN DESCRIPTION:
UNT 1044 IN LATR 35.0
END DESCRIPTION:
XS GIS Cut Line= 3
      2886129.89     10119078.76      2885760.96     10118188.97
      2885362.56     10117916.15
#Sta/Elev= 30
  4345.3  1534.3  4394.2 1531.48  4417.7    1531  4465.5 1527.26  4513.1 1525.55
  4556.4 1521.21  4578.1 1520.69    4625  1517.2  4664.7 1516.23  4678.2 1514.49
  4696.6 1514.49  4733.4 1512.26  4832.3 1506.74  4861.5 1503.71  4938.6 1498.73
  4997.3 1491.33    5000 1490.83  5003.3 1491.33  5021.9 1495.69  5044.9 1498.33
  5116.6 1501.67  5199.1 1507.96  5308.5 1513.24  5462.7 1525.81  5501.5 1527.92
  5564.3 1534.05    5667 1544.66  5752.7 1551.26  5783.2 1555.01  5791.4 1556.32
#Mann= 10 ,-1 , 0
  4345.3     .05       0  4394.2      .1       0    4625     .05       0
  4733.4      .1       0  4997.3     .07       0  5003.3      .1       0
  5462.7     .05       0  5564.3      .1       0    5667     .16       0
  5783.2      .1       0
Bank Sta=4997.3,5003.3
XS Rating Curve= 0 ,0
Exp/Cntr=0.3,0.1

Type RM Length L Ch R = 1 ,16576   ,712,712,712
BEGIN DESCRIPTION:
UNT 1044 IN LATR 34.0
END DESCRIPTION:
XS GIS Cut Line= 4
      2886520.51     10118887.78      2886377.28     10118241.06
      2885865.12     10117945.92      2885662.32     10117712.91
#Sta/Elev= 30
  4106.6  1527.5  4263.6 1522.73  4372.6 1518.28  4387.3 1518.18  4459.3 1514.82
  4599.4 1508.55  4645.9 1507.11  4696.9 1504.52  4783.3 1502.05  4912.9 1499.35
  4950.2 1495.03  4971.8 1490.71  4977.5 1488.81  4993.3 1487.21  4996.1 1486.31
  4998.8 1485.81  5002.1 1486.31  5021.5 1489.98  5095.3 1495.44  5148.5 1500.09
    5170 1502.74  5191.6  1506.3  5276.6 1511.02  5366.1 1517.23  5451.2 1525.67
    5501    1530  5529.4 1535.55  5593.1 1539.39  5628.2 1544.38    5669 1546.24
#Mann= 10 ,-1 , 0
  4106.6     .05       0  4263.6      .1       0  4372.6     .05       0
  4459.3      .1       0  4645.9     .05       0  4783.3      .1       0
  4996.1     .07       0  5002.1      .1       0  5276.6     .05       0
  5451.2      .1       0
Bank Sta=4996.1,5002.1
XS Rating Curve= 0 ,0
Exp/Cntr=0.3,0.1

Type RM Length L Ch R = 1 ,15864   ,896,896,896
BEGIN DESCRIPTION:
UNT 1044 IN LATR 33.0
END DESCRIPTION:
XS GIS Cut Line= 3
      2886846.03     10118840.01      2886698.46     10117498.87
       2886095.2     10117399.05
#Sta/Elev= 30
  3925.8 1516.46  3982.1 1515.12  4169.5 1512.08  4221.2 1510.23  4226.2 1510.86
  4284.2 1507.39  4408.2 1504.81    4494 1501.53    4626 1498.48  4681.1 1497.83
  4803.9  1493.3  4857.7 1489.97  4863.1 1488.24  4868.1 1488.89  4887.8 1484.87
    4908 1482.18  5005.6 1474.94  5008.3 1474.44  5011.6 1474.94  5068.9 1480.26
  5136.1 1489.86  5149.4  1493.2  5189.7 1497.56    5240 1500.81  5312.2 1502.45
    5498 1511.18  5724.4 1526.43    5792 1529.03  5878.1 1529.96  5886.5 1530.04
#Mann= 11 ,-1 , 0
  3925.8     .05       0  3982.1      .1       0  4169.5     .05       0
    4494      .1       0    4626     .05       0  4803.9      .1       0
  5005.6     .07       0  5011.6      .1       0  5312.2     .05       0
  5724.4      .1       0  5878.1     .05       0
Bank Sta=5005.6,5011.6
XS Rating Curve= 0 ,0
Exp/Cntr=0.3,0.1

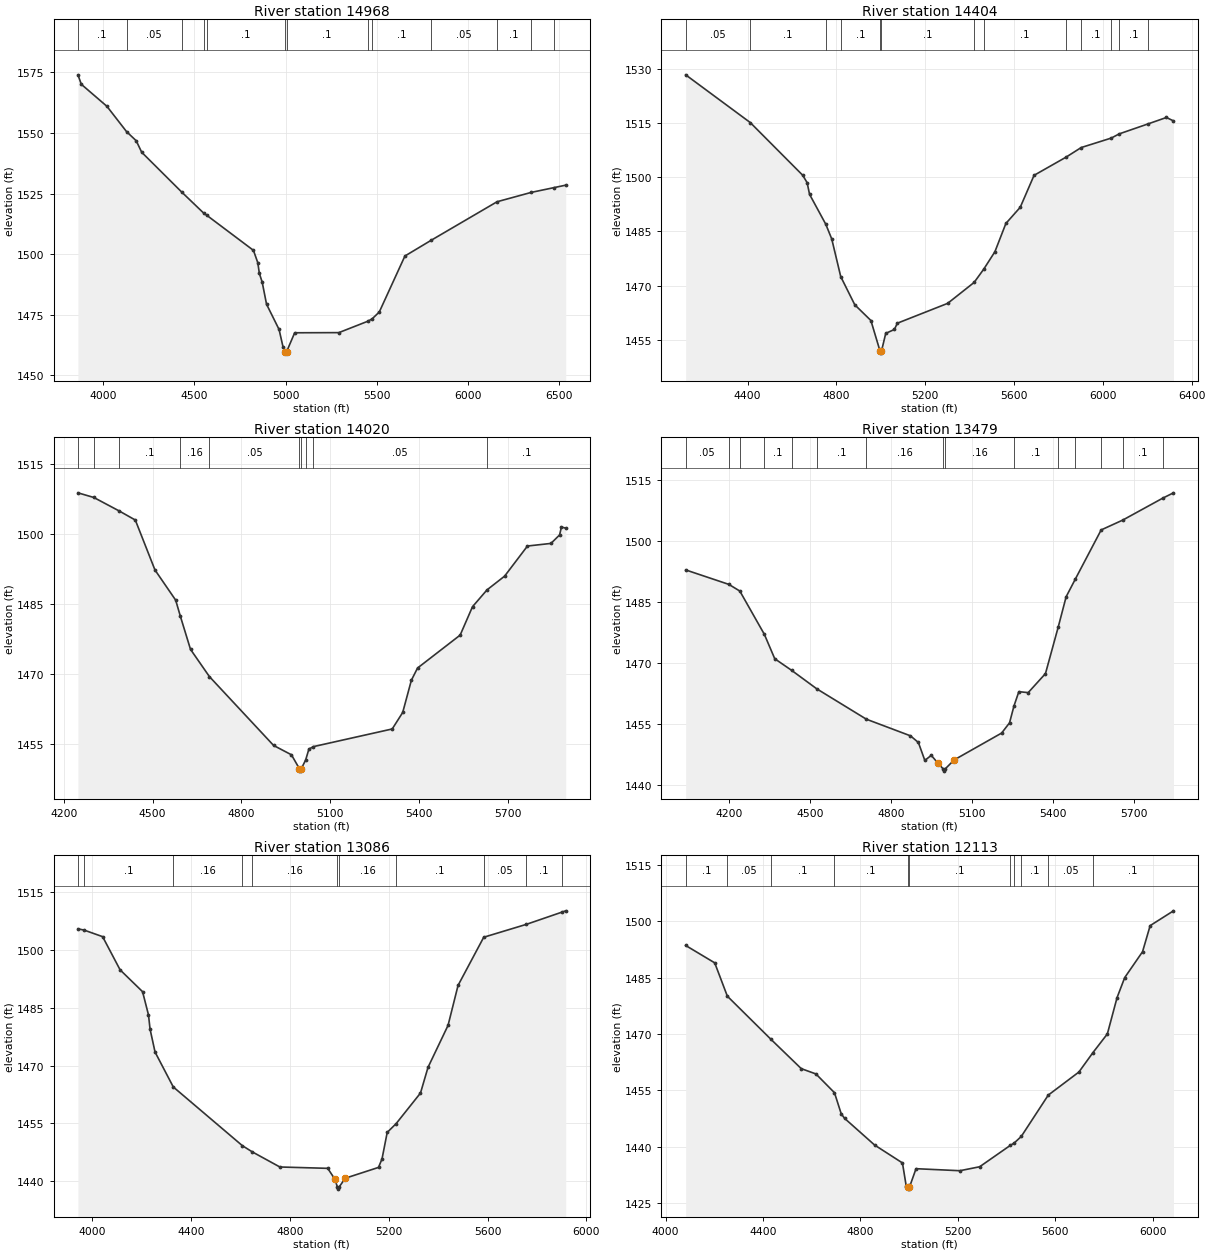
Type RM Length L Ch R = 1 ,14968   ,564,564,564
BEGIN DESCRIPTION:
UNT 1044 IN LATR 30.0
END DESCRIPTION:
XS GIS Cut Line= 4
      2888517.05     10117468.49       2887705.4     10117403.38
      2887106.44     10117155.99      2885908.57     10117346.95
#Sta/Elev= 30
  3860.9 1574.03  3879.5 1570.12    4020 1561.03  4127.5  1550.6  4180.5 1546.83
  4210.6 1542.08  4431.1 1525.58  4552.1 1516.86  4567.2 1516.09  4823.5  1501.6
  4847.4 1496.48  4855.8 1492.12  4871.4  1488.5  4895.3 1479.38    4964 1468.96
  4985.6  1461.8  4998.8  1459.7  5001.5  1459.2  5004.8  1459.7  5049.6  1467.6
  5291.9 1467.66  5450.9 1472.36  5474.5 1473.35  5513.6 1476.17  5654.2 1499.27
    5799  1505.8  6159.5 1521.66    6347 1525.52  6474.5 1527.53  6536.2 1528.51
#Mann= 13 ,-1 , 0
  3860.9      .1       0  4127.5     .05       0  4431.1      .1       0
  4552.1     .05       0  4567.2      .1       0  4998.8     .07       0
  5004.8      .1       0  5450.9     .05       0  5474.5      .1       0
    5799     .05       0  6159.5      .1       0    6347     .05       0
  6474.5      .1       0
Bank Sta=4998.8,5004.8
XS Rating Curve= 0 ,0
Exp/Cntr=0.3,0.1

Type RM Length L Ch R = 1 ,14404   ,384,384,384
BEGIN DESCRIPTION:
UNT 1044 IN LATR 29.0
END DESCRIPTION:
XS GIS Cut Line= 4
      2888191.51     10116765.36      2887475.37     10116678.56
      2887097.76     10116869.53      2886082.78     10117147.13
#Sta/Elev= 30
  4121.4 1528.39  4412.3 1515.16  4648.3 1500.57  4668.4  1498.5  4679.3 1495.27
  4752.4 1486.98  4779.2 1482.91  4819.7 1472.47    4883 1464.66  4955.5 1460.31
    4997 1451.77  4999.8 1451.27    5003 1451.77  5022.3 1456.74  5061.3 1457.83
  5074.6 1459.56  5301.2 1465.06  5420.3 1470.86  5463.1 1474.48    5514 1479.37
  5563.4  1487.2  5628.1 1491.69  5690.3 1500.54  5834.2 1505.57  5902.6 1508.24
  6037.8 1510.86    6074 1512.03  6203.6 1514.79  6286.4 1516.57  6318.2 1515.62
#Mann= 13 ,-1 , 0
  4121.4     .05       0  4412.3      .1       0  4752.4     .16       0
  4819.7      .1       0    4997     .07       0    5003      .1       0
  5420.3     .05       0  5463.1      .1       0  5834.2     .05       0
  5902.6      .1       0  6037.8     .05       0    6074      .1       0
  6203.6     .05       0
Bank Sta=4997,5003
XS Rating Curve= 0 ,0
Exp/Cntr=0.3,0.1

Type RM Length L Ch R = 1 ,14020   ,541,541,541
BEGIN DESCRIPTION:
UNT 1044 IN LATR 28.0
END DESCRIPTION:
XS GIS Cut Line= 4
      2887948.43     10116396.44      2887405.92     10116374.74
       2887015.3      10116413.8      2886443.24     10116838.51
#Sta/Elev= 30
  4247.6 1508.87  4301.3 1507.87  4387.1 1504.97  4441.5 1503.02  4507.8  1492.3
  4577.8 1485.81  4593.8 1482.32  4627.9 1475.24  4691.7 1469.39  4908.6 1454.59
  4968.9 1452.58    4996 1449.57  4998.8 1449.07    5002 1449.57  5016.9 1451.46
  5027.9 1453.81  5043.4 1454.34  5309.4 1458.13  5344.8 1461.68  5374.1  1468.6
  5394.9 1471.22  5538.9  1478.3  5580.6  1484.4  5629.7 1488.02  5689.1 1490.97
  5766.3 1497.44  5845.6    1498  5874.8 1499.82    5881 1501.52  5895.6 1501.28
#Mann= 10 ,-1 , 0
  4247.6      .1       0  4301.3     .05       0  4387.1      .1       0
  4593.8     .16       0  4691.7     .05       0    4996    .035       0
    5002     .05       0  5016.9      .1       0  5043.4     .05       0
  5629.7      .1       0
Bank Sta=4996,5002
XS Rating Curve= 0 ,0
Exp/Cntr=0.3,0.1

Type RM Length L Ch R = 1 ,13479   ,393,393,393
BEGIN DESCRIPTION:
UNT 1044 IN LATR 27.0
END DESCRIPTION:
XS GIS Cut Line= 4
      2887909.43     10116096.97      2887167.21      10115832.2
       2886767.9     10115997.13       2886182.7     10116057.82
#Sta/Elev= 30
  4039.5 1492.84  4199.8 1489.28  4240.2 1487.65  4331.2 1477.02  4369.7 1471.03
  4432.2 1468.18  4525.7 1463.63  4709.4 1456.18  4872.8  1452.1  4902.2 1450.46
  4926.1 1446.06    4950 1447.31  4973.9 1445.44  4994.8 1443.93  4997.6 1443.43
  5000.8 1443.93    5035 1446.19  5210.8 1452.78  5240.1 1455.29  5256.5 1459.42
  5274.6 1462.94  5309.3 1462.71  5373.3 1467.38    5421 1478.91    5450 1486.26
  5484.1  1490.6  5579.8 1502.66  5659.6 1505.07  5808.3 1510.47  5847.9 1511.77
#Mann= 15 ,-1 , 0
  4039.5     .05       0  4199.8      .1       0  4240.2     .05       0
  4331.2      .1       0  4432.2     .05       0  4525.7      .1       0
  4709.4     .16       0  4994.8     .07       0  5000.8     .16       0
  5256.5      .1       0    5421     .05       0  5484.1      .1       0
  5579.8     .05       0  5659.6      .1       0  5808.3     .05       0
Bank Sta=4973.9,5035
XS Rating Curve= 0 ,0
Exp/Cntr=0.3,0.1

Type RM Length L Ch R = 1 ,13086   ,973,973,973
BEGIN DESCRIPTION:
UNT 1044 IN LATR 26.0
END DESCRIPTION:
XS GIS Cut Line= 4
      2887857.34     10115320.05      2886941.51     10115445.92
      2886698.46     10115710.67      2886018.47     10115818.95
#Sta/Elev= 30
  3943.8 1505.51  3968.6 1505.19  4043.6 1503.48  4114.3 1494.86  4205.1 1489.19
  4229.1 1483.16  4235.4 1479.47  4255.6 1473.51  4329.3 1464.44  4608.8 1449.18
  4649.2 1447.56  4760.3 1443.65  4953.8  1443.3  4982.2 1440.53  4993.3  1438.4
  4996.1  1437.9  4999.3  1438.4  5024.7 1440.73  5159.1 1443.54  5173.3 1445.74
  5194.3 1452.63  5230.2  1454.9  5328.9 1462.86  5359.3 1469.53  5440.3 1480.43
  5480.8 1490.82  5584.6 1503.33  5757.1 1506.68  5899.9 1509.83  5916.2 1510.19
#Mann= 11 ,-1 , 0
  3943.8     .05       0  3968.6      .1       0  4329.3     .16       0
  4608.8     .05       0  4649.2     .16       0  4993.3     .07       0
  4999.3     .16       0  5230.2      .1       0  5584.6     .05       0
  5757.1      .1       0  5899.9     .05       0
Bank Sta=4982.2,5024.7
XS Rating Curve= 0 ,0
Exp/Cntr=0.3,0.1

Type RM Length L Ch R = 1 ,12113   ,867,867,867
BEGIN DESCRIPTION:
UNT 1044 IN LATR 25.0
END DESCRIPTION:
XS GIS Cut Line= 4
      2887822.56     10115055.28       2887123.8     10114842.62
      2886672.42     10114859.98      2885886.81      10115098.7
#Sta/Elev= 30
  4082.8 1493.54  4202.1 1488.91  4253.9 1480.04  4433.7 1468.51  4557.5 1460.75
  4617.7 1459.34  4693.9 1454.34  4721.5 1448.74  4735.2 1447.53  4858.6 1440.42
    4973 1435.65  4988.7 1429.41  4995.7 1429.18  4998.4 1428.68  5001.7 1429.18
  5028.7 1434.12  5208.8 1433.58  5289.9 1434.63  5415.4  1440.3  5431.7 1440.95
  5460.8 1442.69  5571.8 1453.71  5697.6 1459.85  5755.2 1465.02  5814.4 1469.99
  5854.3 1479.66  5885.7 1484.99  5958.9 1491.87  5990.2 1498.82    6086 1502.76
#Mann= 11 ,-1 , 0
  4082.8      .1       0  4253.9     .05       0  4433.7      .1       0
  4693.9      .1       0  4995.7     .07       0  5001.7      .1       0
  5415.4      .1       0  5431.7     .05       0  5460.8      .1       0
  5571.8     .05       0  5755.2      .1       0
Bank Sta=4995.7,5001.7
XS Rating Curve= 0 ,0
Exp/Cntr=0.3,0.1

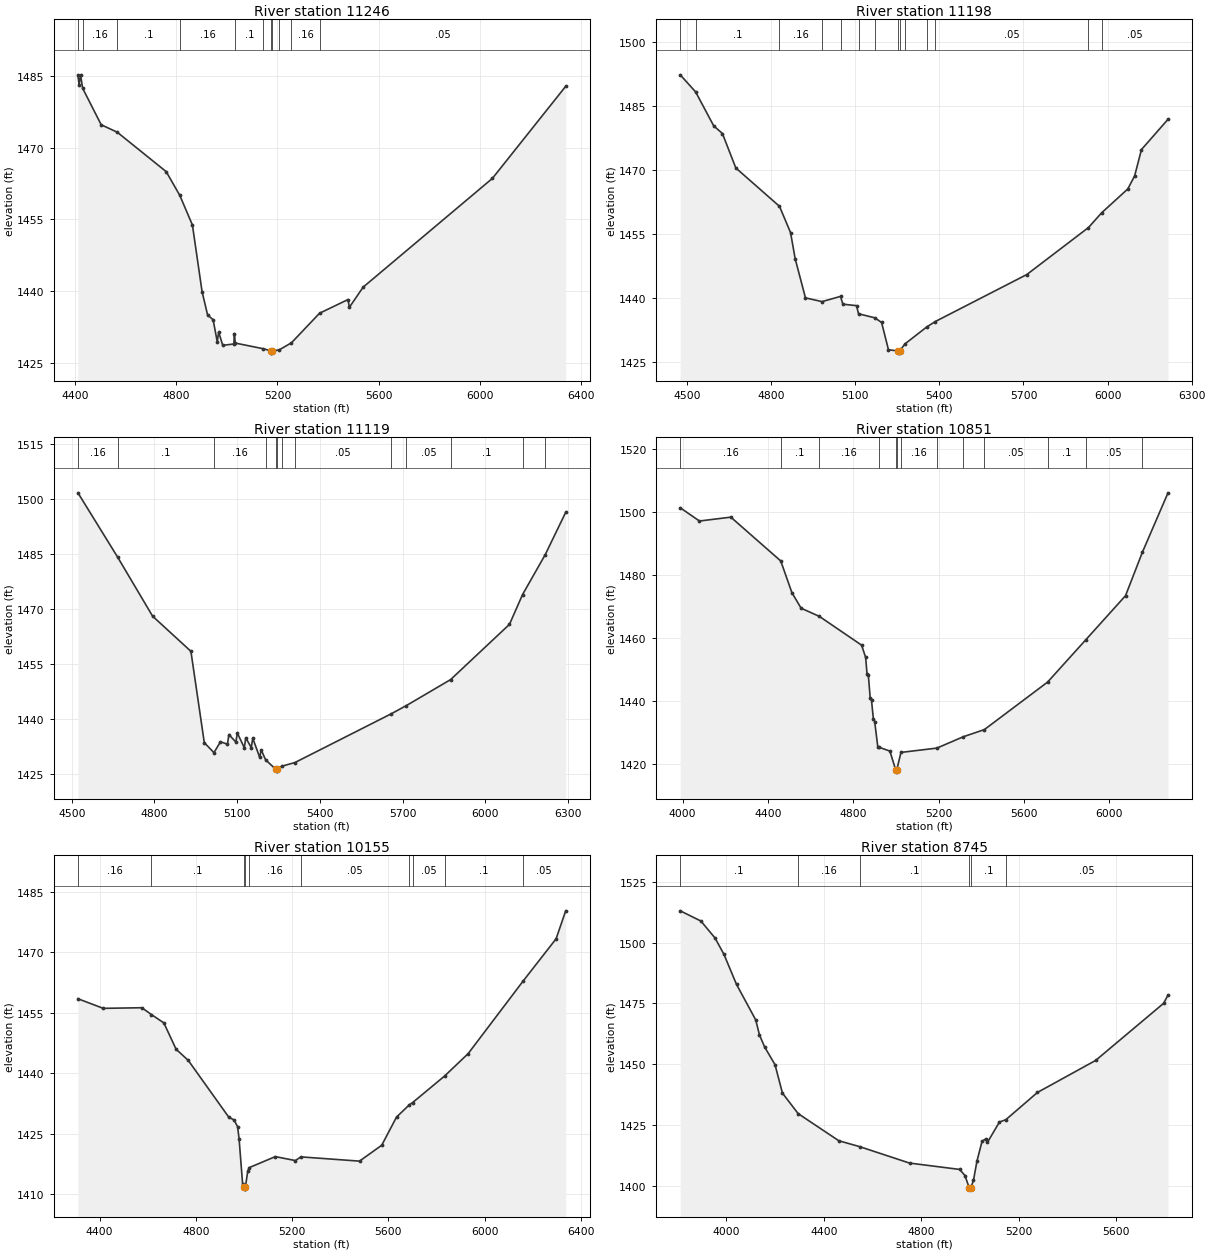
Type RM Length L Ch R = 1 ,11246   ,48,48,48
BEGIN DESCRIPTION:
UNT 1044 IN LATR 24.0
END DESCRIPTION:
XS GIS Cut Line= 3
      2887553.68     10114552.89      2887009.44     10114258.63
      2885822.62     10114811.82
#Sta/Elev= 30
  4411.2 1485.21  4415.7 1483.25  4421.4 1485.32  4429.9  1482.5  4503.2 1474.85
  4566.7 1473.29  4760.1 1465.03  4813.7 1460.07  4863.8 1453.84  4901.9  1439.9
  4923.8 1434.98  4945.7 1433.98  4961.9 1429.38  4967.5 1431.41  4983.7 1428.62
  5027.5 1428.91  5029.8 1431.09    5033  1429.1  5144.1 1427.91    5173 1427.49
  5175.8 1426.99    5179 1427.49  5205.7 1427.64  5255.2 1429.15  5366.3 1435.35
  5478.8 1438.22  5484.3  1436.6  5538.5 1440.81  6049.7 1463.62  6339.3 1482.91
#Mann= 11 ,-1 , 0
  4411.2      .1       0  4429.9     .16       0  4566.7      .1       0
  4813.7     .16       0    5033      .1       0  5144.1     .16       0
    5173     .07       0    5179     .16       0  5205.7      .1       0
  5255.2     .16       0  5366.3     .05       0
Bank Sta=5173,5179
XS Rating Curve= 0 ,0
Exp/Cntr=0.3,0.1

Type RM Length L Ch R = 1 ,11198   ,79,79,79
BEGIN DESCRIPTION:
UNT 1044 IN LATR 22.0
END DESCRIPTION:
XS GIS Cut Line= 4
      2887535.51     10114438.33      2887137.04       10114299.
      2887035.48     10114210.46      2885934.56     10114642.97
#Sta/Elev= 30
  4475.9 1492.25  4530.9 1488.23  4595.2 1480.29  4626.3 1478.49  4674.1 1470.41
  4829.9 1461.41  4869.3 1455.26  4885.9  1449.1  4922.5 1439.95  4981.5 1439.07
  5047.5 1440.29  5055.9 1438.47  5104.7 1438.12  5111.8 1436.22  5169.8 1435.27
  5194.1 1434.18  5218.5 1427.79  5252.2 1427.49  5254.9 1426.99  5258.2 1427.49
  5277.7 1429.17  5354.4 1433.09  5385.6  1434.4  5711.8 1445.41    5932 1456.44
  5978.7 1459.88  6072.2 1465.49  6096.6 1468.55    6121 1474.73  6215.6 1481.82
#Mann= 14 ,-1 , 0
  4475.9     .16       0  4530.9      .1       0  4829.9     .16       0
  4981.5      .1       0  5047.5     .16       0  5111.8      .1       0
  5169.8     .16       0  5252.2     .07       0  5258.2     .16       0
  5277.7     .05       0  5354.4     .16       0  5385.6     .05       0
    5932      .1       0  5978.7     .05       0
Bank Sta=5252.2,5258.2
XS Rating Curve= 0 ,0
Exp/Cntr=0.3,0.1

Type RM Length L Ch R = 1 ,11119   ,268,268,268
BEGIN DESCRIPTION:
UNT 1044 IN LATR 23.0
END DESCRIPTION:
XS GIS Cut Line= 3
      2887545.88     10114336.75      2887075.84     10114154.47
      2885886.86     10114586.53
#Sta/Elev= 30
  4522.6 1501.78  4667.1 1484.18  4793.5 1468.14  4932.4 1458.56    4981 1433.64
    5016 1430.92  5039.6 1433.88  5064.9 1433.24  5070.2 1435.86  5095.5  1433.8
  5100.8 1436.27  5126.1 1432.26  5131.4 1434.97  5151.3 1432.32  5156.7 1434.86
  5181.9 1429.64  5187.3 1431.68  5203.4 1428.96  5240.1 1426.38  5242.9 1425.88
  5246.1 1426.38  5261.9 1427.21    5310 1428.23  5659.4 1441.53  5714.2 1443.77
  5874.5 1450.85  6087.9 1465.91  6135.5 1474.05  6217.6 1484.92  6291.8 1496.45
#Mann= 13 ,-1 , 0
  4522.6     .16       0  4667.1      .1       0    5016     .16       0
  5203.4      .1       0  5240.1     .07       0  5246.1      .1       0
  5261.9     .16       0    5310     .05       0  5659.4     .16       0
  5714.2     .05       0  5874.5      .1       0  6135.5     .05       0
  6217.6      .1       0
Bank Sta=5240.1,5246.1
XS Rating Curve= 0 ,0
Exp/Cntr=0.3,0.1

Type RM Length L Ch R = 1 ,10851   ,696,696,696
BEGIN DESCRIPTION:
UNT 1044 IN LATR 21.0
END DESCRIPTION:
XS GIS Cut Line= 4
      2887967.81     10113937.89      2887124.02     10113833.72
      2886804.58     10114059.42      2885759.41     10114080.25
#Sta/Elev= 30
  3989.1  1501.2  4079.1    1497  4226.2 1498.23  4460.3 1484.32  4512.4 1474.28
  4555.6 1469.33  4641.4 1466.72  4839.3 1457.59  4858.3  1453.7  4864.9 1448.33
    4871 1448.02  4879.7 1440.76  4885.8 1440.07  4894.5  1434.2  4900.6 1433.35
  4915.4 1425.22  4920.1  1425.2    4972 1423.96  4998.6  1418.1  5001.3  1417.6
  5004.6  1418.1  5023.8 1423.54  5192.2 1424.91    5316 1428.51  5414.8 1430.78
  5711.2 1445.86  5889.1  1459.2  6076.7  1473.3  6155.8  1487.1  6275.8 1505.95
#Mann= 13 ,-1 , 0
  3989.1     .16       0  4460.3      .1       0  4641.4     .16       0
  4920.1     .05       0  4998.6    .035       0  5004.6     .05       0
  5023.8     .16       0  5192.2     .05       0    5316     .16       0
  5414.8     .05       0  5711.2      .1       0  5889.1     .05       0
  6155.8      .1       0
Bank Sta=4998.6,5004.6
XS Rating Curve= 0 ,0
Exp/Cntr=0.3,0.1

Type RM Length L Ch R = 1 ,10155   ,1410,1410,1410
BEGIN DESCRIPTION:
UNT 1044 IN LATR 19.0
END DESCRIPTION:
XS GIS Cut Line= 4
      2887700.43     10113476.09      2887078.88     10113368.44
      2886908.74     10113493.44      2885752.99     10113757.22
#Sta/Elev= 30
  4309.7 1458.43  4414.8 1456.05  4575.6  1456.2  4614.9 1454.52  4666.9 1452.44
  4717.7 1445.92  4768.4 1443.14  4937.3 1429.03  4958.8 1428.38  4973.4  1426.7
  4979.6 1423.69  4994.3 1412.46  4999.7 1411.74  5002.5 1411.24  5005.7 1411.74
  5015.5 1415.62  5021.9 1416.57  5130.1  1419.3  5213.5 1418.32  5236.6 1419.23
  5480.1 1418.18  5572.5 1422.12    5634  1429.1  5687.2 1432.14  5700.6 1432.68
  5834.1 1439.29  5931.5 1444.81  6159.1 1462.73  6297.3 1473.29  6337.1 1480.22
#Mann= 10 ,-1 , 0
  4309.7     .16       0  4614.9      .1       0  4999.7     .07       0
  5005.7      .1       0  5021.9     .16       0  5236.6     .05       0
  5687.2      .1       0  5700.6     .05       0  5834.1      .1       0
  6159.1     .05       0
Bank Sta=4999.7,5005.7
XS Rating Curve= 0 ,0
Exp/Cntr=0.3,0.1

Type RM Length L Ch R = 1 ,8745    ,784,784,784
BEGIN DESCRIPTION:
UNT 1044 IN LATR 17.0
END DESCRIPTION:
XS GIS Cut Line= 4
      2886946.91     10112194.85      2886158.74     10112687.89
      2885721.24     10113205.25      2885533.76     10113552.45
#Sta/Elev= 30
  3810.7 1513.06  3895.4 1508.87  3953.2 1501.92  3989.7 1495.26  4041.6 1482.82
  4120.6 1468.21  4135.9 1462.03  4157.1  1457.1  4199.6 1449.84  4230.2 1438.14
  4294.5 1429.73  4461.3 1418.58    4548 1416.12  4751.6  1409.4  4957.6 1406.78
    4979 1404.29  4996.9 1399.19  4999.6 1398.69  5002.9 1399.19  5014.2 1402.31
  5028.4 1410.19  5049.3 1418.33  5063.6 1419.26  5071.3 1417.88  5120.7 1426.27
  5146.8 1427.21  5276.8 1438.43  5515.6 1451.58  5794.5 1475.05  5812.5 1478.45
#Mann= 6 ,-1 , 0
  3810.7      .1       0  4294.5     .16       0    4548      .1       0
  4996.9     .07       0  5002.9      .1       0  5146.8     .05       0
Bank Sta=4996.9,5002.9
XS Rating Curve= 0 ,0
Exp/Cntr=0.3,0.1

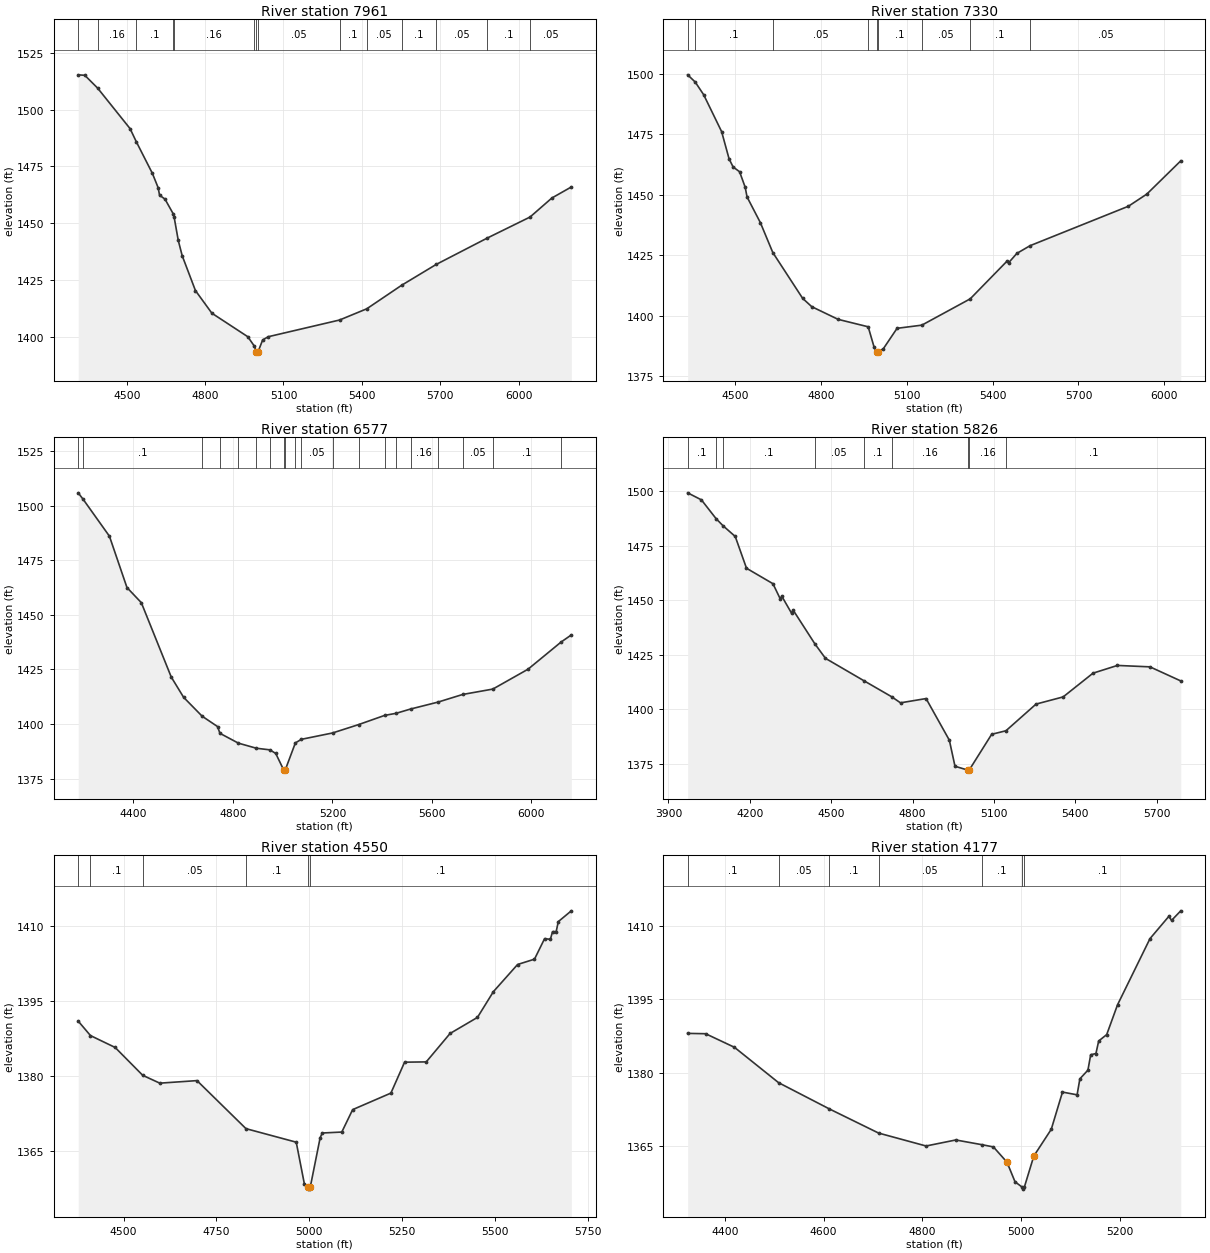
Type RM Length L Ch R = 1 ,7961    ,631,631,631
BEGIN DESCRIPTION:
UNT 1044 IN LATR 15.0
END DESCRIPTION:
XS GIS Cut Line= 4
      2885974.72     10111580.24      2885957.35      10111885.8
      2885596.24     10112413.58      2885266.37     10113295.57
#Sta/Elev= 30
  4314.4 1515.25  4339.7 1515.04  4388.7 1509.43    4513 1491.61  4536.9 1485.84
  4598.3 1471.98  4620.5 1465.65  4625.7  1462.4  4646.6 1460.66  4679.1    1454
  4681.2 1453.01  4697.4  1442.5  4712.4 1435.81  4763.1 1420.51  4826.1 1410.56
  4963.5 1400.24  4988.8 1396.06  4996.4 1393.54  4999.2 1393.04  5002.4 1393.54
  5020.4 1398.84    5042 1400.25  5314.6 1407.58  5418.8 1412.51  5552.3 1422.85
  5684.2 1431.97  5880.4  1443.6  6043.6  1452.8  6127.2 1461.16  6201.6    1466
#Mann= 14 ,-1 , 0
  4314.4      .1       0  4388.7     .16       0  4536.9      .1       0
  4679.1     .05       0  4681.2     .16       0  4988.8     .05       0
  4996.4    .035       0  5002.4     .05       0  5314.6      .1       0
  5418.8     .05       0  5552.3      .1       0  5684.2     .05       0
  5880.4      .1       0  6043.6     .05       0
Bank Sta=4996.4,5002.4
XS Rating Curve= 0 ,0
Exp/Cntr=0.3,0.1

Type RM Length L Ch R = 1 ,7330    ,753,753,753
BEGIN DESCRIPTION:
UNT 1044 IN LATR 14.0
END DESCRIPTION:
XS GIS Cut Line= 4
      2885290.68     10111573.31      2885120.55      10112073.3
       2885276.8     10112656.64      2885096.31     10113218.94
#Sta/Elev= 30
  4334.7 1499.72  4361.2 1496.73  4390.7 1491.48  4453.4  1476.2  4479.5 1464.89
  4493.6 1461.54  4516.2 1459.56  4535.8 1453.12  4542.2 1449.13  4588.7  1438.5
  4632.2 1426.09  4736.5  1407.1  4768.2 1403.66  4860.4  1398.4  4965.4 1395.32
  4986.2 1386.84  4994.9 1384.91  4997.6 1384.41  5000.9 1384.91  5018.6 1386.28
  5066.3 1394.69  5152.8    1396  5321.8  1406.9    5451  1422.6  5456.2 1421.88
  5484.7 1425.73    5531 1428.93  5874.4 1445.27  5938.6 1450.29  6057.3 1464.08
#Mann= 9 ,-1 , 0
  4334.7     .16       0  4361.2      .1       0  4632.2     .05       0
  4965.4      .1       0  4994.9     .07       0  5000.9      .1       0
  5152.8     .05       0  5321.8      .1       0    5531     .05       0
Bank Sta=4994.9,5000.9
XS Rating Curve= 0 ,0
Exp/Cntr=0.3,0.1

Type RM Length L Ch R = 1 ,6577    ,751,751,751
BEGIN DESCRIPTION:
UNT 1044 IN LATR 12.0
END DESCRIPTION:
XS GIS Cut Line= 4
      2885190.03     10111479.53      2884703.88      10111861.5
      2884439.99     10112160.11       2884734.9     10113079.51
#Sta/Elev= 30
  4178.1 1505.84  4198.4 1502.81  4303.6    1486  4374.1  1462.5  4431.9 1455.56
  4552.2 1421.52  4601.9 1412.25  4676.3 1403.61  4738.3 1398.86  4747.9 1395.77
  4822.2 1391.27  4894.5 1388.94  4948.6 1388.21  4972.2 1386.56  5004.3 1378.97
    5007 1378.47  5010.3 1378.97  5051.1 1391.38  5075.1 1393.02  5200.4 1395.93
  5305.1 1399.76  5409.8 1403.97  5456.4 1404.94  5514.5  1406.9  5624.5 1410.06
  5723.8 1413.56  5844.9 1416.02  5986.3 1425.11  6119.3 1437.55  6160.4  1440.8
#Mann= 20 ,-1 , 0
  4178.1     .16       0  4198.4      .1       0  4676.3     .05       0
  4747.9     .16       0  4822.2      .1       0  4894.5     .16       0
  4948.6      .1       0  5004.3     .07       0  5010.3      .1       0
  5051.1     .16       0  5075.1     .05       0  5200.4      .1       0
  5305.1     .05       0  5409.8     .16       0  5456.4      .1       0
  5514.5     .16       0  5624.5      .1       0  5723.8     .05       0
  5844.9      .1       0  6119.3     .05       0
Bank Sta=5004.3,5010.3
XS Rating Curve= 0 ,0
Exp/Cntr=0.3,0.1

Type RM Length L Ch R = 1 ,5826    ,1276,1276,1276
BEGIN DESCRIPTION:
UNT 1044 IN LATR 10.0
END DESCRIPTION:
XS GIS Cut Line= 4
      2885203.91     10110996.91      2884439.99     10111184.42
      2884155.27     10111521.22      2883564.99     10111521.22
#Sta/Elev= 30
  3970.7 1499.32  4021.5 1496.09  4075.5 1487.48  4101.5 1484.17  4146.2 1479.29
  4187.7 1464.71  4285.2 1457.62  4312.5 1450.55  4317.6 1451.92    4354 1444.03
  4359.2 1445.59  4439.7 1430.03  4478.7 1423.38  4619.5 1413.17  4722.3 1405.78
  4755.5 1402.95  4849.7 1404.91  4935.5 1385.81  4956.3 1373.85  5002.7 1372.11
  5005.5 1371.61  5008.7 1372.11  5091.5 1388.51  5144.1 1390.13  5255.1 1402.37
  5355.1 1405.67  5465.1 1416.56  5555.1 1420.11  5675.1 1419.46  5788.6    1413
#Mann= 9 ,-1 , 0
  3970.7      .1       0  4075.5     .05       0  4101.5      .1       0
  4439.7     .05       0  4619.5      .1       0  4722.3     .16       0
  5002.7     .07       0  5008.7     .16       0  5144.1      .1       0
Bank Sta=5002.7,5008.7
XS Rating Curve= 0 ,0
Exp/Cntr=0.3,0.1

Type RM Length L Ch R = 1 ,4550    ,373,373,373
BEGIN DESCRIPTION:
UNT 1044 IN LATR 7.0
END DESCRIPTION:
XS GIS Cut Line= 3
      2883967.74     10110463.93      2883499.02     10110484.76
      2882764.62     10110927.48
#Sta/Elev= 30
    4378 1390.97    4411 1388.07  4477.4 1385.69  4551.6 1380.11  4597.5 1378.54
  4697.6 1379.05  4829.4 1369.43  4964.6 1366.72  4986.3 1358.44  4996.6 1357.82
  4999.4 1357.32  5002.6 1357.82    5029 1367.63  5034.8 1368.56  5087.2 1368.75
  5116.4 1373.24  5219.3 1376.55  5256.1 1382.74  5314.4  1382.8  5378.5 1388.49
  5452.2 1391.71    5495 1396.86  5560.1  1402.3  5605.6 1403.37  5632.8 1407.48
  5648.3 1407.34  5654.2 1408.87  5663.9 1408.88  5669.7 1410.89  5704.7 1413.05
#Mann= 6 ,-1 , 0
    4378     .05       0    4411      .1       0  4551.6     .05       0
  4829.4      .1       0  4996.6     .07       0  5002.6      .1       0
Bank Sta=4996.6,5002.6
XS Rating Curve= 0 ,0
Exp/Cntr=0.3,0.1

Type RM Length L Ch R = 1 ,4177    ,379,379,379
BEGIN DESCRIPTION:
UNT 1044 IN LATR 6.0
END DESCRIPTION:
XS GIS Cut Line= 3
      2883810.19     10110275.12       2883297.2     10110181.38
      2882877.89     10110407.96
#Sta/Elev= 30
  4324.9 1388.07  4361.3    1388  4419.6 1385.23    4509    1378  4611.8 1372.64
  4711.4 1367.71  4807.5 1365.07  4867.7  1366.3  4920.3 1365.34  4943.8 1364.88
  4971.3 1361.76  4987.5 1357.77  5000.7 1356.76  5003.5 1356.26  5006.7 1356.76
  5025.6 1363.02  5060.9 1368.48  5083.6 1376.08  5113.2 1375.52  5118.8 1378.79
  5135.1 1380.56  5140.7  1383.7  5151.3 1383.96  5156.9 1386.52  5173.1 1387.82
    5195  1393.9  5260.7 1407.42  5298.8 1411.96  5304.4 1411.15    5323  1413.1
#Mann= 7 ,-1 , 0
  4324.9      .1       0    4509     .05       0  4611.8      .1       0
  4711.4     .05       0  4920.3      .1       0  5000.7     .07       0
  5006.7      .1       0
Bank Sta=4971.3,5025.6
XS Rating Curve= 0 ,0
Exp/Cntr=0.3,0.1