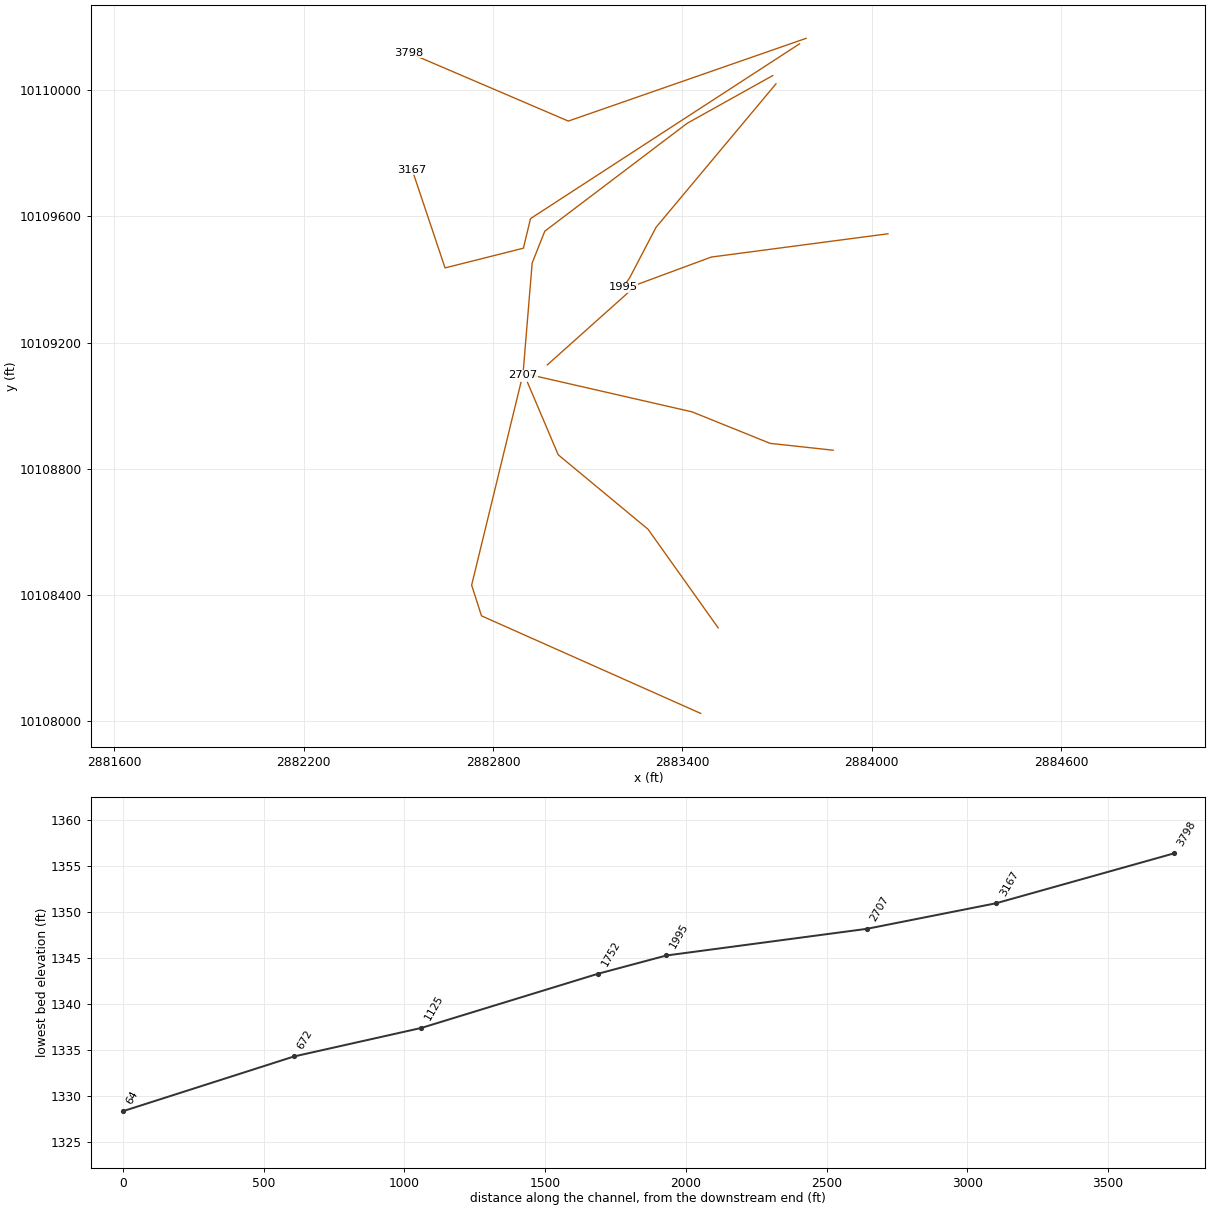
HEC-RAS study UNT 0044 IN LATR.prj: UNT 1044 IN LATR Base Level Engineering

--- UNT 0044 IN LATR.g01 (geometry) --- (continued)

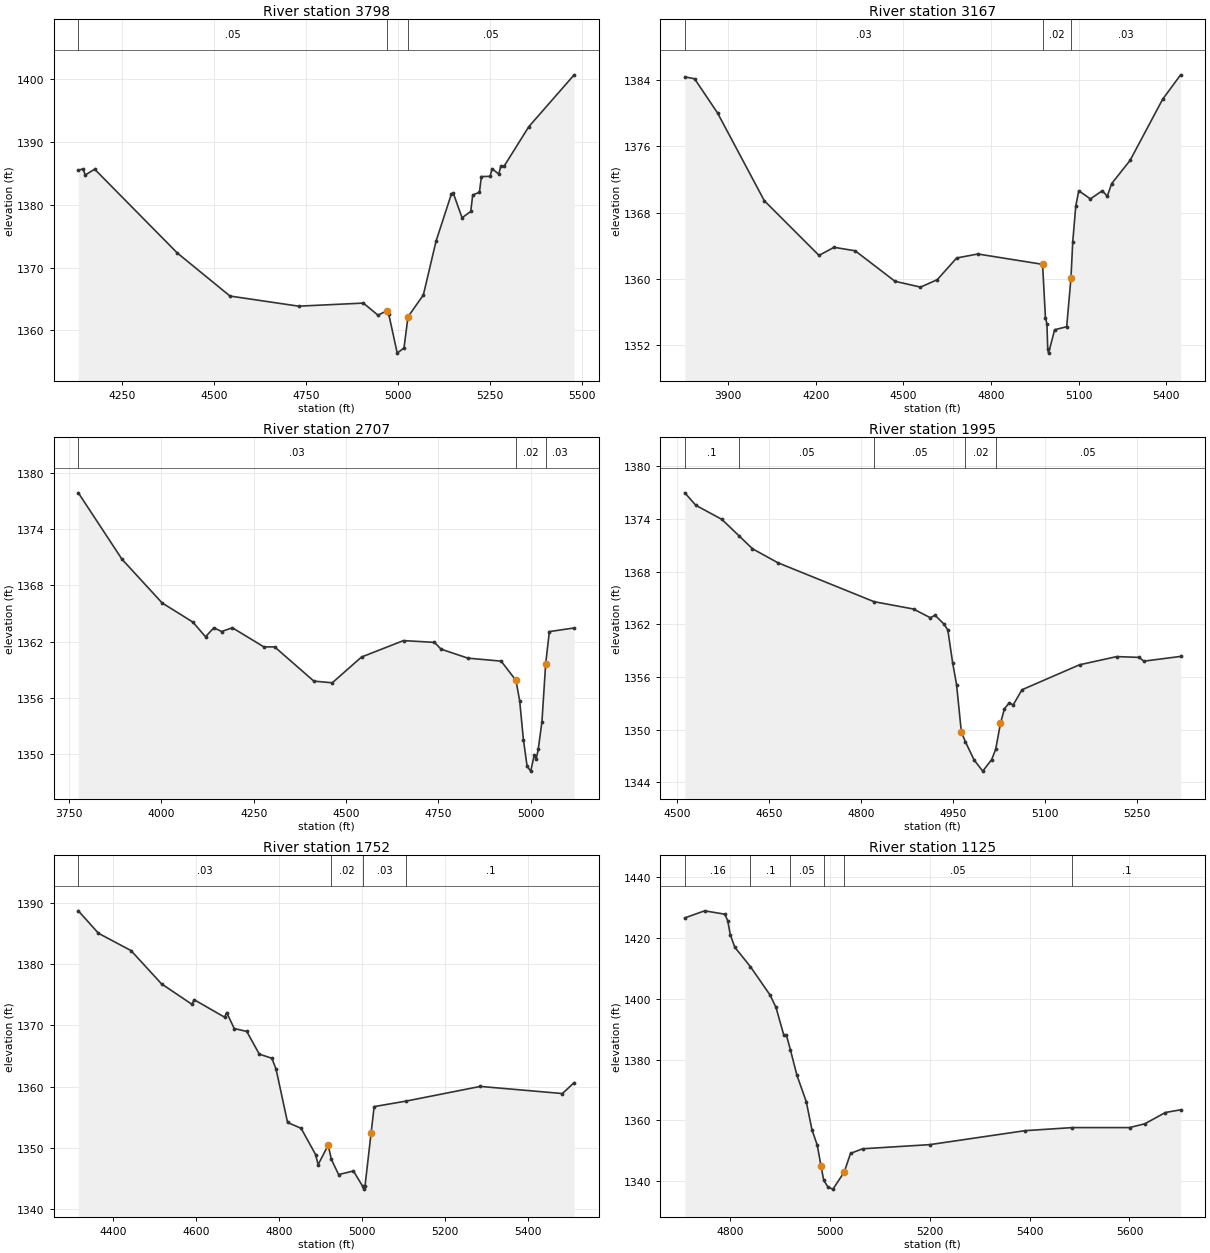
Type RM Length L Ch R = 1 ,3798    ,631,631,631
BEGIN DESCRIPTION:
UNT 1044 IN LATR 5.0
END DESCRIPTION:
XS GIS Cut Line= 3
      2883792.35     10110164.36      2883038.89     10109902.21
      2882533.33     10110118.64
#Sta/Elev= 30
  4131.1 1385.52  4144.4  1385.7  4149.7 1384.73  4175.5 1385.66  4399.9 1372.34
  4543.3 1365.48  4729.9 1363.87  4905.9 1364.36  4945.5 1362.44  4969.1 1363.11
  4974.6 1362.66  4997.9  1356.4  5016.3 1357.23  5027.2 1362.18  5068.9 1365.65
  5103.4 1374.21  5145.1 1381.71  5150.5  1381.8  5174.1 1377.94  5197.7 1378.93
  5203.1 1381.57  5221.3 1381.98  5226.7 1384.49  5250.3 1384.52  5255.7 1385.75
  5273.9 1384.87  5279.3 1386.12  5288.3 1386.13  5355.5 1392.42  5478.8 1400.67
#Mann= 3 , 0 , 0
  4131.1     .05       0  4969.1     .03       0  5027.2     .05       0
Bank Sta=4969.1,5027.2
XS Rating Curve= 0 ,0
Exp/Cntr=0.3,0.1

Type RM Length L Ch R = 1 ,3167    ,460,460,460
BEGIN DESCRIPTION:
Mapping XS d2c6d968
END DESCRIPTION:
XS GIS Cut Line= 5
      2883771.55     10110147.02       2882919.1     10109593.19
      2882896.53     10109499.44      2882648.27     10109436.94
      2882544.09     10109747.74
#Sta/Elev= 30
  3752.1 1384.43  3785.6 1384.19  3864.1 1380.06  4024.2 1369.43  4211.4 1362.81
  4262.7 1363.79  4335.2 1363.37  4471.3 1359.68  4558.7 1358.97    4616 1359.87
  4682.5  1362.5    4755 1362.98  4976.5 1361.73  4986.3 1355.26  4991.4 1354.52
  4994.1 1351.48  4996.9 1350.98  5017.8 1353.81    5059 1354.18  5073.6 1360.06
  5079.6 1364.39    5090 1368.76  5100.3 1370.64  5140.1 1369.65    5181 1370.64
    5198 1369.97  5212.6 1371.49  5275.9 1374.31  5387.3 1381.71  5448.9 1384.67
#Mann= 3 , 0 , 0
  3752.1     .03       0  4976.5     .02       0  5073.6     .03       0
Bank Sta=4976.5,5073.6
XS Rating Curve= 0 ,0
Exp/Cntr=0.3,0.1

Type RM Length L Ch R = 1 ,2707    ,712,712,712
BEGIN DESCRIPTION:
Mapping XS 7edffd53
END DESCRIPTION:
XS GIS Cut Line= 5
      2883686.49     10110046.33      2883415.63     10109895.27
      2882964.24     10109553.26      2882924.31     10109452.56
      2882894.95     10109096.86
#Sta/Elev= 30
  3775.5 1377.87  3893.6 1370.79  4002.2 1366.13  4085.6 1364.08  4119.7 1362.52
  4142.3 1363.48  4163.2 1363.08  4192.3 1363.48  4277.6 1361.44  4306.7 1361.44
  4412.8 1357.79  4462.7 1357.61  4541.8 1360.36  4655.4 1362.11  4739.2 1361.92
    4757  1361.2  4829.4 1360.24  4919.7 1359.92  4959.8 1357.86  4969.8 1355.67
  4979.9 1351.54  4989.9  1348.7  4999.7 1348.19  5009.3 1349.93  5014.3 1349.45
    5020 1350.51    5030 1353.44  5040.1 1359.64  5050.1 1363.07  5117.2 1363.46
#Mann= 3 , 0 , 0
  3775.5     .03       0  4959.8     .02       0  5040.1     .03       0
Bank Sta=4959.8,5040.1
XS Rating Curve= 0 ,0
Exp/Cntr=0.3,0.1

Type RM Length L Ch R = 1 ,1995    ,243,243,243
BEGIN DESCRIPTION:
Mapping XS 09059685
END DESCRIPTION:
XS GIS Cut Line= 4
      2883696.87     10110020.26      2883316.67     10109565.41
      2883233.33     10109405.69      2883212.51     10109376.18
#Sta/Elev= 30
  4512.6    1377  4530.6 1375.58  4573.2 1373.97  4600.8 1372.12    4623 1370.63
  4664.6 1369.03  4821.3  1364.6  4885.8 1363.76  4913.2 1362.77    4921 1363.05
  4935.3 1362.06  4941.8 1361.38  4949.6 1357.66  4956.1 1355.14  4963.9 1349.74
  4970.4 1348.65  4984.7 1346.56  4998.8 1345.29  5013.4 1346.61  5019.9 1347.78
  5027.7 1350.72  5034.2  1352.4    5042 1353.07  5048.5 1352.84  5062.8 1354.56
  5156.8 1357.41  5217.5 1358.34    5254 1358.25  5261.6 1357.82  5321.7 1358.36
#Mann= 5 ,-1 , 0
  4512.6      .1       0  4600.8     .05       0  4821.3     .05       0
  4970.4     .02       0  5019.9     .05       0
Bank Sta=4963.9,5027.7
XS Rating Curve= 0 ,0
Exp/Cntr=0.3,0.1

Type RM Length L Ch R = 1 ,1752    ,627,627,627
BEGIN DESCRIPTION:
UNT 1044 IN LATR 4.0
END DESCRIPTION:
XS GIS Cut Line= 4
      2884051.54     10109545.09      2883491.64     10109471.31
      2883257.27      10109384.5       2882972.3     10109129.76
#Sta/Elev= 30
  4315.3 1388.66  4363.9    1385  4442.5 1382.18  4516.1 1376.76  4589.6 1373.42
  4594.7 1374.18  4668.3 1371.33  4673.3 1372.08  4691.6 1369.48  4721.9    1369
  4752.1 1365.31  4782.4 1364.63  4792.5 1362.89  4820.4 1354.16    4853 1353.22
  4888.1 1348.93  4894.1 1347.29  4918.5 1350.48  4926.1 1348.15  4943.6 1345.67
  4979.4 1346.26  5001.3  1343.8  5004.1  1343.3  5007.3  1343.8  5022.1 1352.49
  5029.4 1356.75  5107.4 1357.66  5285.6 1360.04  5483.8 1358.88  5512.2 1360.66
#Mann= 4 ,-1 , 0
  4315.3     .03       0  4926.1     .02       0  5001.3     .03       0
  5107.4      .1       0
Bank Sta=4918.5,5022.1
XS Rating Curve= 0 ,0
Exp/Cntr=0.3,0.1

Type RM Length L Ch R = 1 ,1125    ,453,453,453
BEGIN DESCRIPTION:
UNT 1044 IN LATR 2.0
END DESCRIPTION:
XS GIS Cut Line= 4
      2883877.95     10108859.33      2883678.27     10108881.03
      2883430.88     10108980.86      2882918.74     10109098.04
#Sta/Elev= 30
  4709.5 1426.54  4749.2 1428.86  4789.5 1427.76  4795.5 1425.64  4800.5 1421.06
  4809.6 1416.91  4840.7 1410.56    4880 1401.26  4892.1 1397.14  4907.7 1388.06
  4912.9 1388.06  4920.9 1383.25    4934 1374.86  4952.8 1366.15  4964.1 1356.95
  4974.8 1351.86  4982.3    1345  4987.7 1340.33  4996.4 1338.05  5006.2 1337.41
  5028.8 1343.03  5041.4 1349.15  5065.5 1350.67  5200.1 1352.03  5390.8 1356.62
  5485.6 1357.63  5600.2 1357.63    5631  1358.9    5672 1362.59  5702.5 1363.48
#Mann= 6 ,-1 , 0
  4709.5     .16       0  4840.7      .1       0  4920.9     .05       0
  4987.7     .03       0  5028.8     .05       0  5485.6      .1       0
Bank Sta=4982.3,5028.8
XS Rating Curve= 0 ,0
Exp/Cntr=0.3,0.1

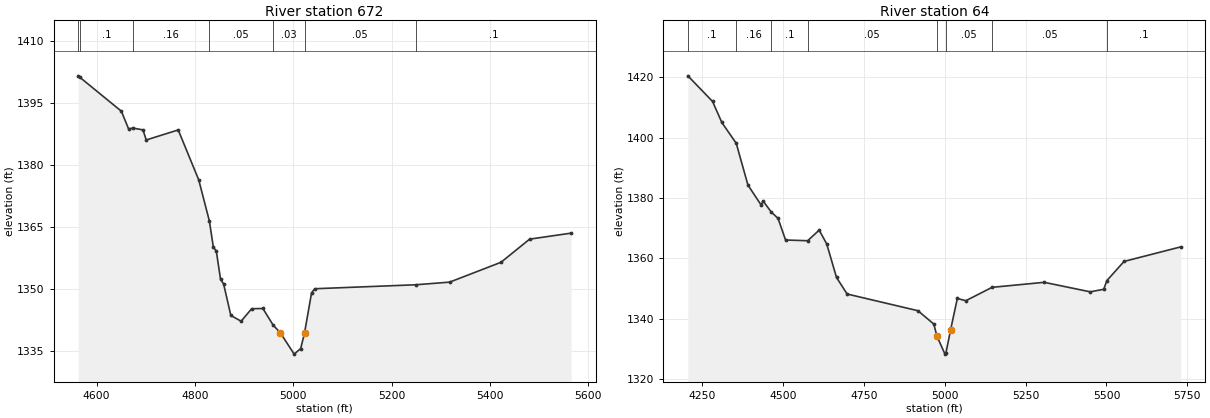
Type RM Length L Ch R = 1 ,672     ,608,608,608
BEGIN DESCRIPTION:
Mapping XS e44d242c
END DESCRIPTION:
XS GIS Cut Line= 4
      2883513.75     10108296.29      2883291.52     10108608.81
      2883006.79     10108844.92      2882909.57     10109074.08
#Sta/Elev= 30
  4562.5 1401.63    4566 1401.26  4650.3 1393.07  4665.1 1388.76  4673.4    1389
  4694.3 1388.55  4700.8 1386.11  4765.9 1388.54  4807.7 1376.43  4829.3 1366.49
  4837.3 1360.21  4843.4  1359.2    4852 1352.39  4858.2 1351.29  4872.9 1343.66
  4893.8 1342.26  4915.2 1345.28  4938.1 1345.34    4959 1341.31  4973.3  1339.5
  5001.7  1334.3    5015 1335.66  5022.8 1339.46  5037.1 1349.14  5043.6 1350.12
    5249 1351.08  5317.9 1351.72  5422.3 1356.52  5480.5 1362.12  5564.8 1363.57
#Mann= 7 ,-1 , 0
  4562.5     .05       0    4566      .1       0  4673.4     .16       0
  4829.3     .05       0    4959     .03       0  5022.8     .05       0
    5249      .1       0
Bank Sta=4973.3,5022.8
XS Rating Curve= 0 ,0
Exp/Cntr=0.3,0.1

Type RM Length L Ch R = 1 ,64      ,0,0,0
BEGIN DESCRIPTION:
UNT 1044 IN LATR 1.0
END DESCRIPTION:
XS GIS Cut Line= 4
      2883458.15     10108025.49      2882763.74      10108334.5
      2882732.49     10108431.73      2882888.74     10109074.11
#Sta/Elev= 30
  4206.3 1420.42  4282.6 1411.94  4311.3 1404.98  4355.8 1398.09    4392 1384.27
    4433 1377.63  4438.5 1379.06  4463.8 1375.38    4485 1373.25  4508.2  1366.1
  4576.5 1365.86  4612.1 1369.37  4635.4 1364.81  4665.7  1353.7  4698.5 1348.23
  4917.4  1342.7  4966.4 1338.28  4976.1 1334.26  5000.9 1328.34  5004.1 1328.84
  5018.1 1336.31  5039.1 1346.76  5065.3 1346.01  5146.4 1350.44  5307.3  1352.1
  5449.8 1348.95  5491.5  1349.8  5501.3 1352.68  5554.3 1359.01  5729.6 1363.83
#Mann= 8 ,-1 , 0
  4206.3      .1       0  4355.8     .16       0  4463.8      .1       0
  4576.5     .05       0  4976.1     .03       0  5004.1     .05       0
  5146.4     .05       0  5501.3      .1       0
Bank Sta=4976.1,5018.1
XS Rating Curve= 0 ,0
Exp/Cntr=0.3,0.1

Chan Stop Cuts=-1
Use User Specified Reach Order=0
Composite Channel Slope=5