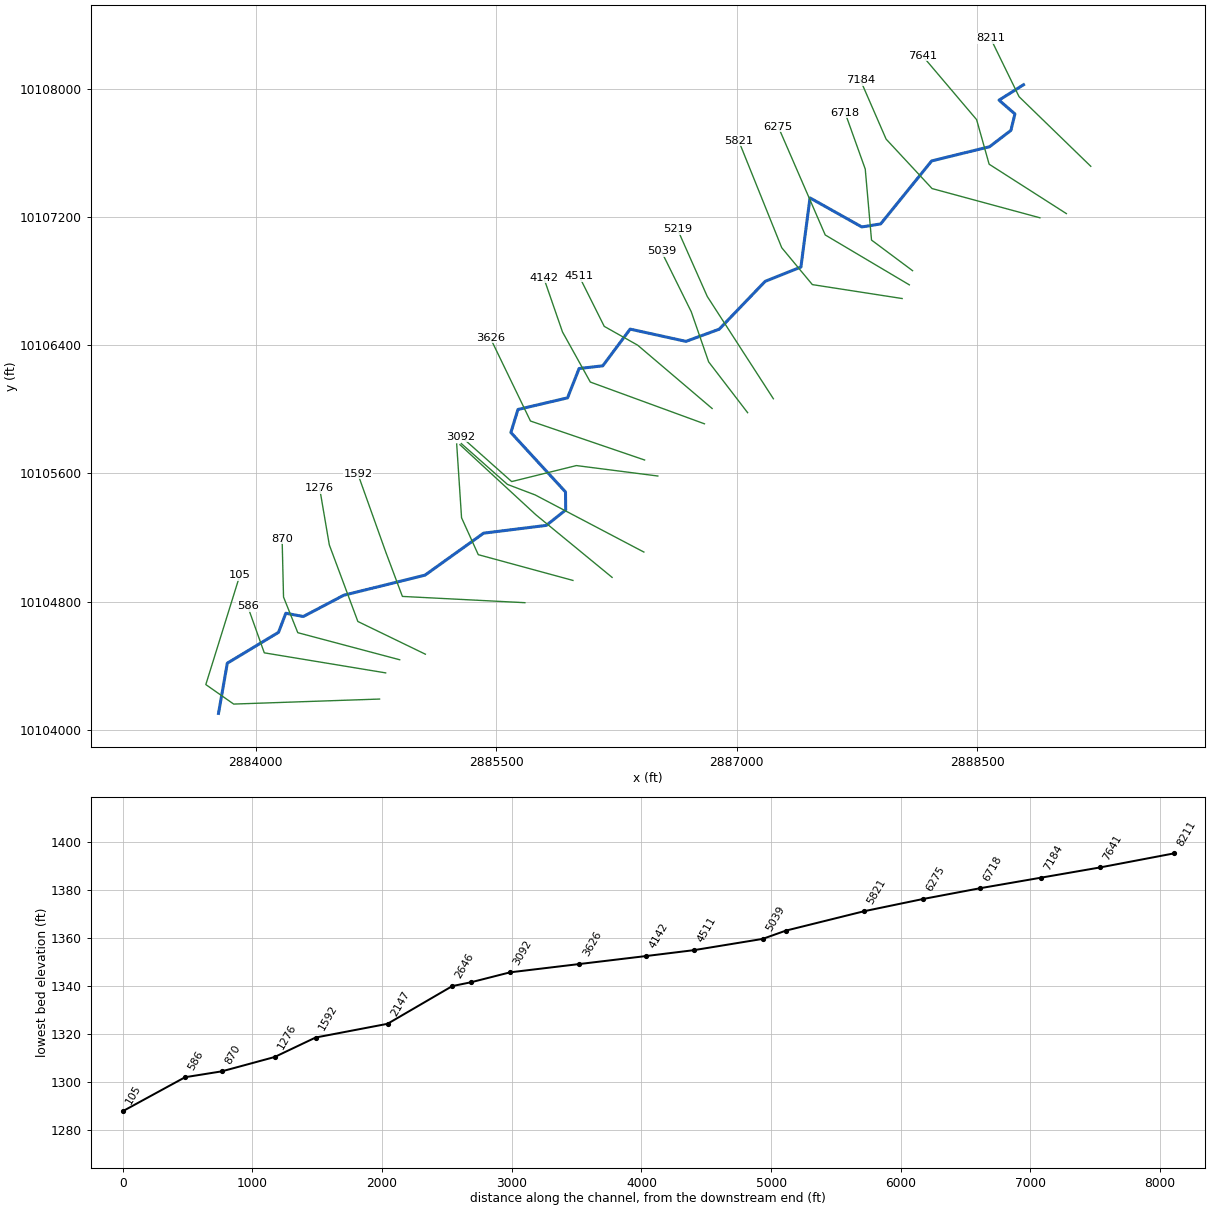
--- UNT 0046 IN LATR.prj (project) ---

Proj Title=UNT 1046 IN LATR Base Level Engineering
Current Plan=p01
Default Exp/Contr=0.3,0.1
English Units
Geom File=g01
Flow File=f01
Plan File=p01
Y Axis Title=Elevation
X Axis Title(PF)=Main Channel Distance
X Axis Title(XS)=Station
BEGIN DESCRIPTION:
UNT 1046 IN LATR
END DESCRIPTION:
DSS Export Rating Curves= 0
DSS Export Rating Curve Sorted= 0
DSS Export Volume Flow Curves= 0
DXF OffsetX= 0
DXF OffsetY= 0
DXF ScaleX= 1
DXF ScaleY= 10

--- UNT 0046 IN LATR.p01 (plan) ---

Plan Title=Multiple Run
Short Identifier=Multiple
Geom File=g01
Flow File=f01
Subcritical Flow
K Sum by GR= 0
Std Step Tol= 0.01
Critical Tol= 0.01
Num of Std Step Trials= 20
Max Error Tol= 0.3
Flow Tol Ratio= 0.001
Split Flow NTrial= 30
Split Flow Tol= 0.02
Split Flow Ratio= 0.02
Log Output Level= 0
Friction Slope Method= 1
Unsteady Friction Slope Method= 2
Unsteady Bridges Friction Slope Method= 1
Parabolic Critical Depth
Global Vel Dist=  1 , 1 , 1
Global Log Level= 0
CheckData=True
Encroach Param= -1, 0, 0, 0
BEGIN DESCRIPTION:
Multiple Run
END DESCRIPTION:

--- UNT 0046 IN LATR.f01 (steady flow) ---

Flow Title=Multiple
Number of Profiles=7
Profile Names=10-year,25-year,50-year,1pct_min,100-year,1pct_plu,500-year
River Rch & RM= UNT 1046 IN LATR,Reach-1,8211
     935    1376    1765    1659    2243    3033    3637
River Rch & RM= UNT 1046 IN LATR,Reach-1,7184
    1127    1667    2144    2018    2730    3692    4444
Boundary for River Rch & Prof#=UNT 1046 IN LATR,Reach-1,1
Up Type=0
Dn Type=3
Dn Slope=0.005
Boundary for River Rch & Prof#=UNT 1046 IN LATR,Reach-1,2
Up Type=0
Dn Type=3
Dn Slope=0.005
Boundary for River Rch & Prof#=UNT 1046 IN LATR,Reach-1,3
Up Type=0
Dn Type=3
Dn Slope=0.005
Boundary for River Rch & Prof#=UNT 1046 IN LATR,Reach-1,4
Up Type=0
Dn Type=3
Dn Slope=0.005
Boundary for River Rch & Prof#=UNT 1046 IN LATR,Reach-1,5
Up Type=0
Dn Type=3
Dn Slope=0.005
Boundary for River Rch & Prof#=UNT 1046 IN LATR,Reach-1,6
Up Type=0
Dn Type=3
Dn Slope=0.005
Boundary for River Rch & Prof#=UNT 1046 IN LATR,Reach-1,7
Up Type=0
Dn Type=3
Dn Slope=0.005

--- UNT 0046 IN LATR.g01 (geometry) ---

Geom Title=Existing Conditions
Program Version=4.10

River Reach=UNT 1046 IN LATR,Reach-1
Reach XY= 30
      2888788.47     10108023.73      2888635.88     10107927.81
      2888734.75     10107841.53      2888709.86      10107739.2
      2888576.95     10107637.39      2888215.64     10107548.78
      2887897.73     10107155.88      2887780.02     10107137.13
      2887456.96     10107318.16      2887400.38     10106886.97
      2887177.15     10106797.67      2886891.08     10106499.48
      2886683.55      10106423.5      2886335.44      10106499.9
      2886164.75     10106271.04      2886017.19     10106254.31
      2885944.95     10106071.21      2885635.78     10105998.79
      2885591.69     10105855.31      2885932.31     10105484.45
      2885933.51     10105372.07      2885812.66     10105276.01
      2885421.51     10105227.42      2885056.17     10104965.68
      2884549.79     10104840.53      2884297.19     10104707.74
       2884188.2      10104728.2      2884142.79     10104609.15
      2883823.34     10104416.68      2883768.47     10104103.73

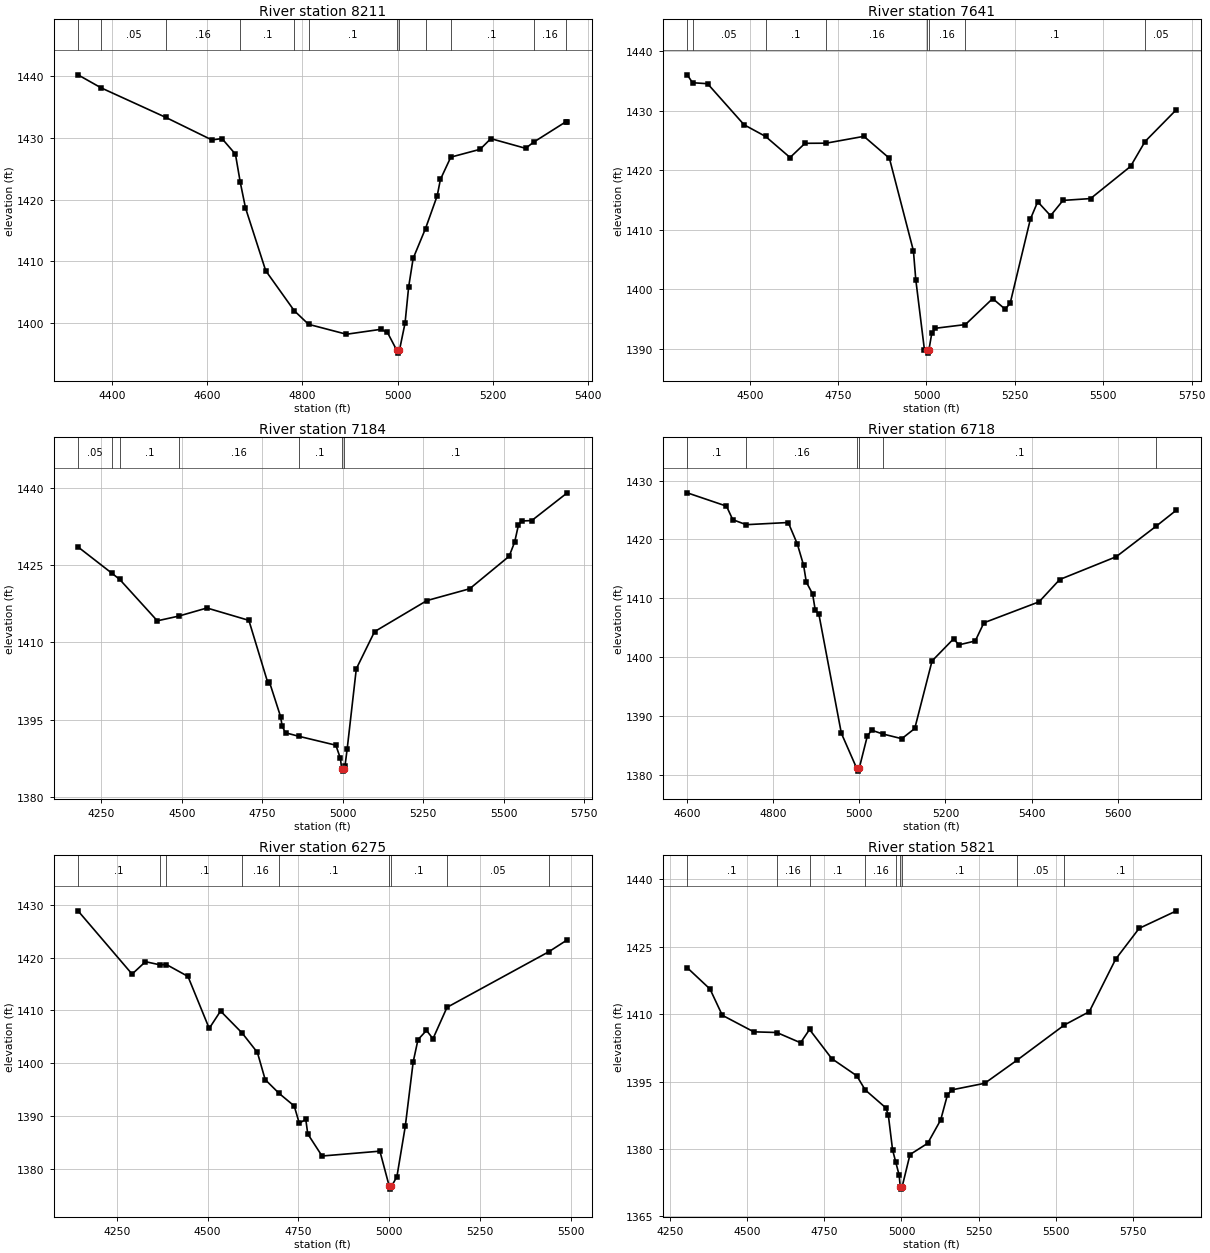
Type RM Length L Ch R = 1 ,8211    ,570,570,570
BEGIN DESCRIPTION:
UNT 1046 IN LATR 17.0
END DESCRIPTION:
XS GIS Cut Line= 3
      2889207.77     10107515.31       2888760.7     10107949.35
       2888583.1     10108313.22
#Sta/Elev= 30
  4328.5 1440.22  4377.3  1438.1  4512.5 1433.34  4609.7 1429.67    4631 1429.89
  4659.3 1427.36  4669.4 1422.82  4680.4 1418.66  4722.9 1408.48  4782.9 1401.99
  4812.9 1399.79  4892.6 1398.18  4965.1 1398.98  4978.7 1398.47    4998 1395.62
  5000.7 1395.12    5004 1395.62  5015.7 1399.99  5023.2 1405.82  5032.7 1410.47
  5058.7 1415.31  5083.3 1420.63    5090 1423.27  5111.8 1426.88  5173.4 1428.15
  5195.9 1429.88    5269 1428.31  5285.7  1429.3  5353.8 1432.62  5356.5 1432.58
#Mann= 12 ,-1 , 0
  4328.5     .16       0  4377.3     .05       0  4512.5     .16       0
  4669.4      .1       0  4782.9     .16       0  4812.9      .1       0
    4998     .07       0    5004      .1       0  5058.7     .16       0
  5111.8      .1       0  5285.7     .16       0  5353.8      .1       0
Bank Sta=4998,5004
XS Rating Curve= 0 ,0
Exp/Cntr=0.3,0.1

Type RM Length L Ch R = 1 ,7641    ,457,457,457
BEGIN DESCRIPTION:
UNT 1046 IN LATR 16.0
END DESCRIPTION:
XS GIS Cut Line= 4
      2889055.81     10107220.21      2888574.07     10107528.35
      2888495.95     10107806.12      2888157.41     10108205.42
#Sta/Elev= 30
  4323.2 1436.06  4338.3 1434.73  4380.7 1434.57  4483.9 1427.67  4544.9  1425.7
  4614.1 1422.16  4656.4 1424.55    4716 1424.57    4823 1425.72  4895.1 1422.03
    4963 1406.48  4969.7 1401.63  4994.1 1389.86  5000.7 1389.78  5003.5 1389.28
  5006.7 1389.78  5014.9 1392.61  5025.3 1393.46    5110 1394.08  5187.2 1398.45
  5222.4 1396.67  5236.7 1397.67  5293.8  1411.8  5314.6 1414.73  5350.9 1412.38
  5386.1 1414.95  5464.1 1415.26  5577.2 1420.67  5618.2 1424.85  5707.1 1430.22
#Mann= 8 ,-1 , 0
  4323.2     .16       0  4338.3     .05       0  4544.9      .1       0
    4716     .16       0  5000.7     .07       0  5006.7     .16       0
    5110      .1       0  5618.2     .05       0
Bank Sta=5000.7,5006.7
XS Rating Curve= 0 ,0
Exp/Cntr=0.3,0.1

Type RM Length L Ch R = 1 ,7184    ,466,466,466
BEGIN DESCRIPTION:
UNT 1046 IN LATR 15.0
END DESCRIPTION:
XS GIS Cut Line= 4
      2888890.87     10107194.16      2888218.17     10107376.44
      2887931.71      10107684.6       2887771.1     10108053.56
#Sta/Elev= 30
  4177.2 1428.52  4283.2 1423.38    4307  1422.2  4423.6 1414.18  4490.4  1415.1
  4577.8 1416.67  4708.1 1414.27  4766.7 1402.21  4771.8 1402.35  4806.5 1395.61
  4811.7 1393.69  4822.1 1392.45  4862.8 1391.78  4978.4 1390.04  4992.5 1387.47
  4996.4 1385.51  4999.1 1385.01  5002.4 1385.51  5006.7 1386.01  5013.5 1389.29
  5041.9 1404.87  5098.6 1412.08  5261.3 1418.11  5394.1  1420.4  5516.8 1426.71
  5533.9 1429.47  5545.7 1432.79  5555.7 1433.55  5587.1 1433.64  5697.3 1439.02
#Mann= 7 ,-1 , 0
  4177.2     .05       0  4283.2     .16       0    4307      .1       0
  4490.4     .16       0  4862.8      .1       0  4996.4     .07       0
  5002.4      .1       0
Bank Sta=4996.4,5002.4
XS Rating Curve= 0 ,0
Exp/Cntr=0.3,0.1

Type RM Length L Ch R = 1 ,6718    ,443,443,443
BEGIN DESCRIPTION:
UNT 1046 IN LATR 14.0
END DESCRIPTION:
XS GIS Cut Line= 4
      2888096.65     10106864.28      2887840.56     10107055.26
       2887801.5     10107497.96      2887675.77     10107849.15
#Sta/Elev= 30
  4599.9 1427.92  4691.1 1425.66  4705.7 1423.36  4736.9 1422.51  4834.6 1422.88
  4855.8 1419.22  4870.4 1415.59  4876.6 1412.76  4891.2 1410.76  4897.5 1407.95
  4905.8 1407.32    4958  1387.1  4993.6 1381.16  4996.4 1380.66  4999.6 1381.16
  5018.2 1386.56  5028.2 1387.62  5054.1 1386.97  5098.5 1386.17  5128.6  1387.9
  5168.8 1399.37    5219 1403.14  5230.9  1402.1  5269.2 1402.76  5289.3 1405.85
  5417.5 1409.41  5465.5  1413.2  5596.8 1417.07    5690 1422.28  5736.8 1424.99
#Mann= 6 ,-1 , 0
  4599.9      .1       0  4736.9     .16       0  4993.6     .07       0
  4999.6     .16       0  5054.1      .1       0    5690     .05       0
Bank Sta=4993.6,4999.6
XS Rating Curve= 0 ,0
Exp/Cntr=0.3,0.1

Type RM Length L Ch R = 1 ,6275    ,454,454,454
BEGIN DESCRIPTION:
Mapping XS 17400fc3
END DESCRIPTION:
XS GIS Cut Line= 3
      2888076.44     10106775.92      2887551.93     10107087.07
      2887258.57     10107762.67
#Sta/Elev= 30
  4143.4 1428.85  4292.2 1416.87  4329.1 1419.22  4367.7 1418.64  4386.7 1418.68
    4446 1416.43  4504.5 1406.58  4535.7 1409.87  4595.2  1405.7  4637.1 1402.03
  4658.5 1396.89  4696.8 1394.28  4738.4  1391.9  4752.4 1388.62  4770.2 1389.38
  4775.7  1386.6    4815 1382.42  4974.2 1383.34  5000.1 1376.65  5002.9 1376.15
  5006.1 1376.65  5021.1 1378.54    5044 1388.01  5065.8 1400.23    5079 1404.45
  5102.4  1406.2  5120.3 1404.63  5158.9 1410.57  5438.8 1421.09  5489.8 1423.35
#Mann= 9 ,-1 , 0
  4143.4      .1       0  4367.7     .16       0  4386.7      .1       0
  4595.2     .16       0  4696.8      .1       0  5000.1     .07       0
  5006.1      .1       0  5158.9     .05       0  5438.8      .1       0
Bank Sta=5000.1,5006.1
XS Rating Curve= 0 ,0
Exp/Cntr=0.3,0.1

Type RM Length L Ch R = 1 ,5821    ,602,602,602
BEGIN DESCRIPTION:
UNT 1046 IN LATR 12.0
END DESCRIPTION:
XS GIS Cut Line= 4
      2888031.52     10106690.68      2887471.64     10106777.48
      2887280.67     10107007.51      2887011.56     10107675.94
#Sta/Elev= 30
  4305.5 1420.31  4379.4 1415.56  4419.1 1409.74  4521.1 1406.05  4595.9  1405.9
  4672.9 1403.62    4702 1406.57  4774.1 1400.09    4855 1396.28  4882.4 1393.14
  4949.6 1389.13  4957.4 1387.56  4971.2 1379.81  4981.5 1377.07  4992.6 1374.17
  4996.1 1371.57  4998.8 1371.07  5002.1 1371.57  5027.7 1378.76    5085 1381.26
  5127.1 1386.44  5148.8 1391.95  5163.1 1393.14    5270 1394.61  5375.8  1399.8
  5528.4 1407.58  5608.9 1410.53  5694.4 1422.21  5770.6 1429.06  5891.6 1432.96
#Mann= 9 ,-1 , 0
  4305.5      .1       0  4595.9     .16       0    4702      .1       0
  4882.4     .16       0  4981.5      .1       0  4996.1     .07       0
  5002.1      .1       0  5375.8     .05       0  5528.4      .1       0
Bank Sta=4996.1,5002.1
XS Rating Curve= 0 ,0
Exp/Cntr=0.3,0.1

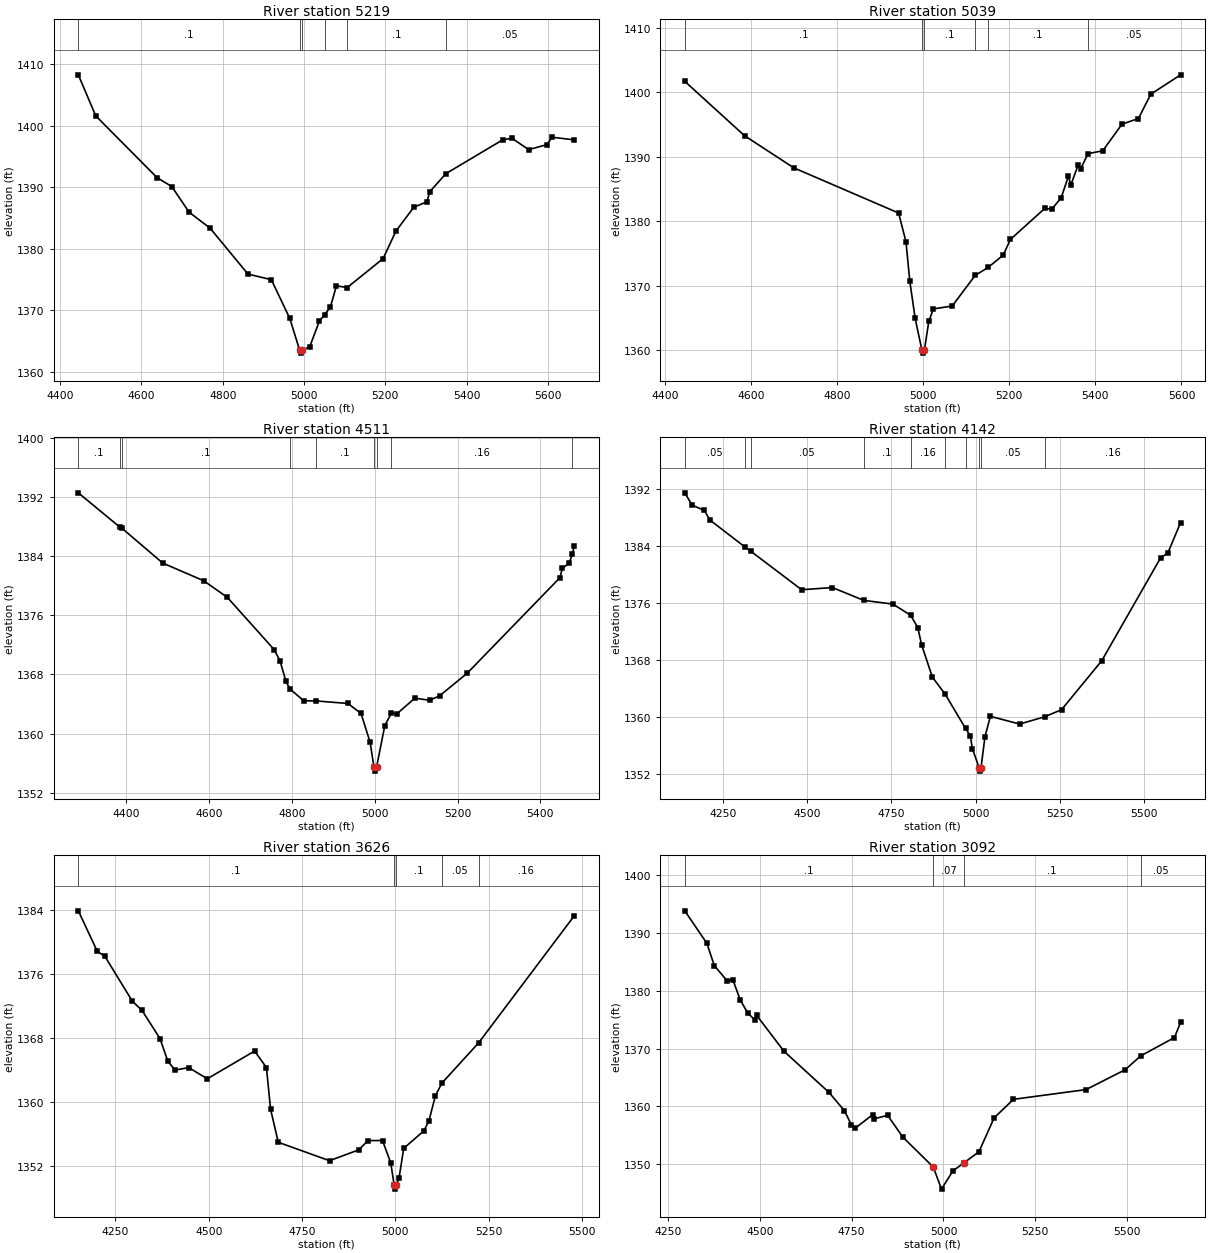
Type RM Length L Ch R = 1 ,5219    ,180,180,180
BEGIN DESCRIPTION:
UNT 1046 IN LATR 11.0
END DESCRIPTION:
XS GIS Cut Line= 3
      2887228.56     10106065.71      2886816.26     10106703.69
      2886629.64     10107124.67
#Sta/Elev= 30
  4444.6  1408.3  4487.4 1401.63  4638.5 1391.56  4674.7 1390.12    4717 1385.96
  4768.4 1383.38  4862.1 1375.88  4919.5 1374.97    4965 1368.66  4989.1 1363.52
  4991.8 1363.02  4995.1 1363.52  5013.8 1364.02  5037.6 1368.21  5050.7  1369.3
  5064.7 1370.48  5079.8 1373.98    5106 1373.68  5194.6  1378.4  5226.1 1382.87
  5269.9 1386.74  5302.7 1387.66    5309 1389.25  5348.8 1392.21  5488.7 1397.72
  5511.6 1397.98  5552.7 1396.13    5598 1396.95  5610.2 1398.15  5664.7 1397.72
#Mann= 6 ,-1 , 0
  4444.6      .1       0  4989.1     .07       0  4995.1      .1       0
  5050.7     .05       0    5106      .1       0  5348.8     .05       0
Bank Sta=4989.1,4995.1
XS Rating Curve= 0 ,0
Exp/Cntr=0.3,0.1

Type RM Length L Ch R = 1 ,5039    ,528,528,528
BEGIN DESCRIPTION:
UNT 1046 IN LATR 10.0
END DESCRIPTION:
XS GIS Cut Line= 4
        2887068.     10105978.86      2886824.94     10106295.71
      2886716.43     10106608.21      2886529.78     10106985.85
#Sta/Elev= 30
  4446.6 1401.67  4585.3 1393.25  4699.5 1388.28  4943.2 1381.27  4960.3 1376.78
    4969 1370.77  4981.5 1364.96  4997.1 1360.07  4999.9 1359.57  5003.1 1360.07
  5013.2 1364.49  5023.8 1366.42  5067.6 1366.87  5120.9 1371.61  5150.9 1372.84
    5186 1374.75  5202.8 1377.19  5283.3 1382.03  5298.2 1381.83  5320.6 1383.62
  5337.5 1386.98    5343 1385.62  5359.9 1388.68  5365.5 1388.05  5382.8 1390.47
  5417.2 1390.91  5461.8 1395.04  5500.1 1395.91  5528.7 1399.68    5598 1402.68
#Mann= 6 ,-1 , 0
  4446.6      .1       0  4997.1     .07       0  5003.1      .1       0
  5120.9     .05       0  5150.9      .1       0  5382.8     .05       0
Bank Sta=4997.1,5003.1
XS Rating Curve= 0 ,0
Exp/Cntr=0.3,0.1

Type RM Length L Ch R = 1 ,4511    ,369,369,369
BEGIN DESCRIPTION:
UNT 1046 IN LATR 9.0
END DESCRIPTION:
XS GIS Cut Line= 4
      2886846.65      10106004.9      2886382.23     10106399.87
       2886173.9     10106517.06      2886017.86     10106829.14
#Sta/Elev= 30
  4283.9 1392.59  4384.7 1387.92  4389.8 1387.77  4487.7 1383.08  4586.5 1380.69
  4643.7 1378.44  4756.8 1371.37  4771.1 1369.84  4785.3 1367.07  4794.6 1366.06
  4828.2 1364.44  4859.1 1364.41    4935 1364.07  4966.7 1362.72  4988.6 1358.82
  4998.1 1355.41  5000.9 1354.91  5004.1 1355.41  5024.1 1361.06  5039.8 1362.75
  5053.6 1362.69  5096.9 1364.79  5132.6  1364.5  5156.4  1365.1  5223.4 1368.18
  5447.1  1381.1  5453.1 1382.41  5469.4 1383.04  5476.7 1384.24  5481.5 1385.33
#Mann= 9 ,-1 , 0
  4283.9      .1       0  4384.7     .05       0  4389.8      .1       0
  4794.6     .16       0  4859.1      .1       0  4998.1     .07       0
  5004.1      .1       0  5039.8     .16       0  5476.7      .1       0
Bank Sta=4998.1,5004.1
XS Rating Curve= 0 ,0
Exp/Cntr=0.3,0.1

Type RM Length L Ch R = 1 ,4142    ,516,516,516
BEGIN DESCRIPTION:
UNT 1046 IN LATR 8.0
END DESCRIPTION:
XS GIS Cut Line= 4
      2886798.89     10105909.43      2886087.09     10106169.84
      2885913.48     10106482.34      2885796.68     10106819.77
#Sta/Elev= 30
  4136.4 1391.47  4158.1 1389.74    4194 1389.02  4211.4 1387.64  4315.8 1383.85
  4332.2 1383.29  4483.3 1377.89  4574.9 1378.19    4668 1376.39  4754.4 1375.88
  4807.2  1374.3  4828.3 1372.59  4839.6 1370.18  4871.6 1365.64  4909.7 1363.24
  4970.2 1358.44  4984.4 1357.41  4990.3 1355.63  5010.2 1352.96  5012.9 1352.46
  5016.2 1352.96  5027.9  1357.3  5043.9 1360.14  5130.8 1359.06  5204.7 1360.07
  5255.2 1361.07  5374.6 1367.93  5549.6 1382.37  5570.8 1383.02  5608.9 1387.31
#Mann= 10 ,-1 , 0
  4136.4     .05       0  4315.8      .1       0  4332.2     .05       0
    4668      .1       0  4807.2     .16       0  4909.7      .1       0
  4970.2     .05       0  5010.2    .035       0  5016.2     .05       0
  5204.7     .16       0
Bank Sta=5010.2,5016.2
XS Rating Curve= 0 ,0
Exp/Cntr=0.3,0.1

Type RM Length L Ch R = 1 ,3626    ,534,534,534
BEGIN DESCRIPTION:
UNT 1046 IN LATR 7.0
END DESCRIPTION:
XS GIS Cut Line= 3
      2886425.63     10105683.73      2885713.83     10105926.78
      2885462.76     10106446.24
#Sta/Elev= 30
  4150.5 1383.88  4201.3 1378.82  4221.5 1378.21  4295.4 1372.59  4321.3 1371.44
  4369.4 1367.93  4390.5 1365.09    4410    1364  4446.6  1364.3  4496.2 1362.91
    4623 1366.37  4654.7 1364.31  4665.8 1359.12  4686.4 1354.98  4823.8 1352.68
  4902.6 1354.04  4926.7 1355.19  4965.9  1355.2  4988.1 1352.38  4997.1 1349.63
  4999.8 1349.13  5003.1 1349.63  5010.3 1350.55  5022.7 1354.22    5077 1356.42
  5090.5 1357.69  5107.5 1360.77  5124.9 1362.36  5223.4 1367.39  5479.6 1383.24
#Mann= 5 ,-1 , 0
  4150.5      .1       0  4997.1     .07       0  5003.1      .1       0
  5124.9     .05       0  5223.4     .16       0
Bank Sta=4997.1,5003.1
XS Rating Curve= 0 ,0
Exp/Cntr=0.3,0.1

Type RM Length L Ch R = 1 ,3092    ,299,299,299
BEGIN DESCRIPTION:
UNT 1046 IN LATR 6.0
END DESCRIPTION:
XS GIS Cut Line= 4
      2886508.07     10105583.91      2886000.29     10105649.01
      2885596.64     10105549.18      2885281.21     10105830.05
#Sta/Elev= 30
  4295.6 1393.83  4355.7 1388.21  4375.9 1384.36  4411.7 1381.66  4426.3 1381.94
  4446.4 1378.43  4466.6 1376.19  4486.3 1374.93  4491.3 1375.74  4565.9 1369.52
  4688.4  1362.4  4730.3 1359.25  4748.9 1356.84    4759 1356.19  4807.5 1358.58
  4811.6 1357.85  4847.9 1358.45  4889.3 1354.68  4972.2  1349.5  4994.6 1345.68
  5025.7 1348.84    5055  1350.2  5096.5 1352.14  5137.9 1358.01  5190.6 1361.22
  5388.2  1362.9  5494.4 1366.33  5537.2 1368.74    5629 1371.91  5645.7 1374.56
#Mann= 4 ,-1 , 0
  4295.6      .1       0  4972.2     .07       0    5055      .1       0
  5537.2     .05       0
Bank Sta=4972.2,5055
XS Rating Curve= 0 ,0
Exp/Cntr=0.3,0.1

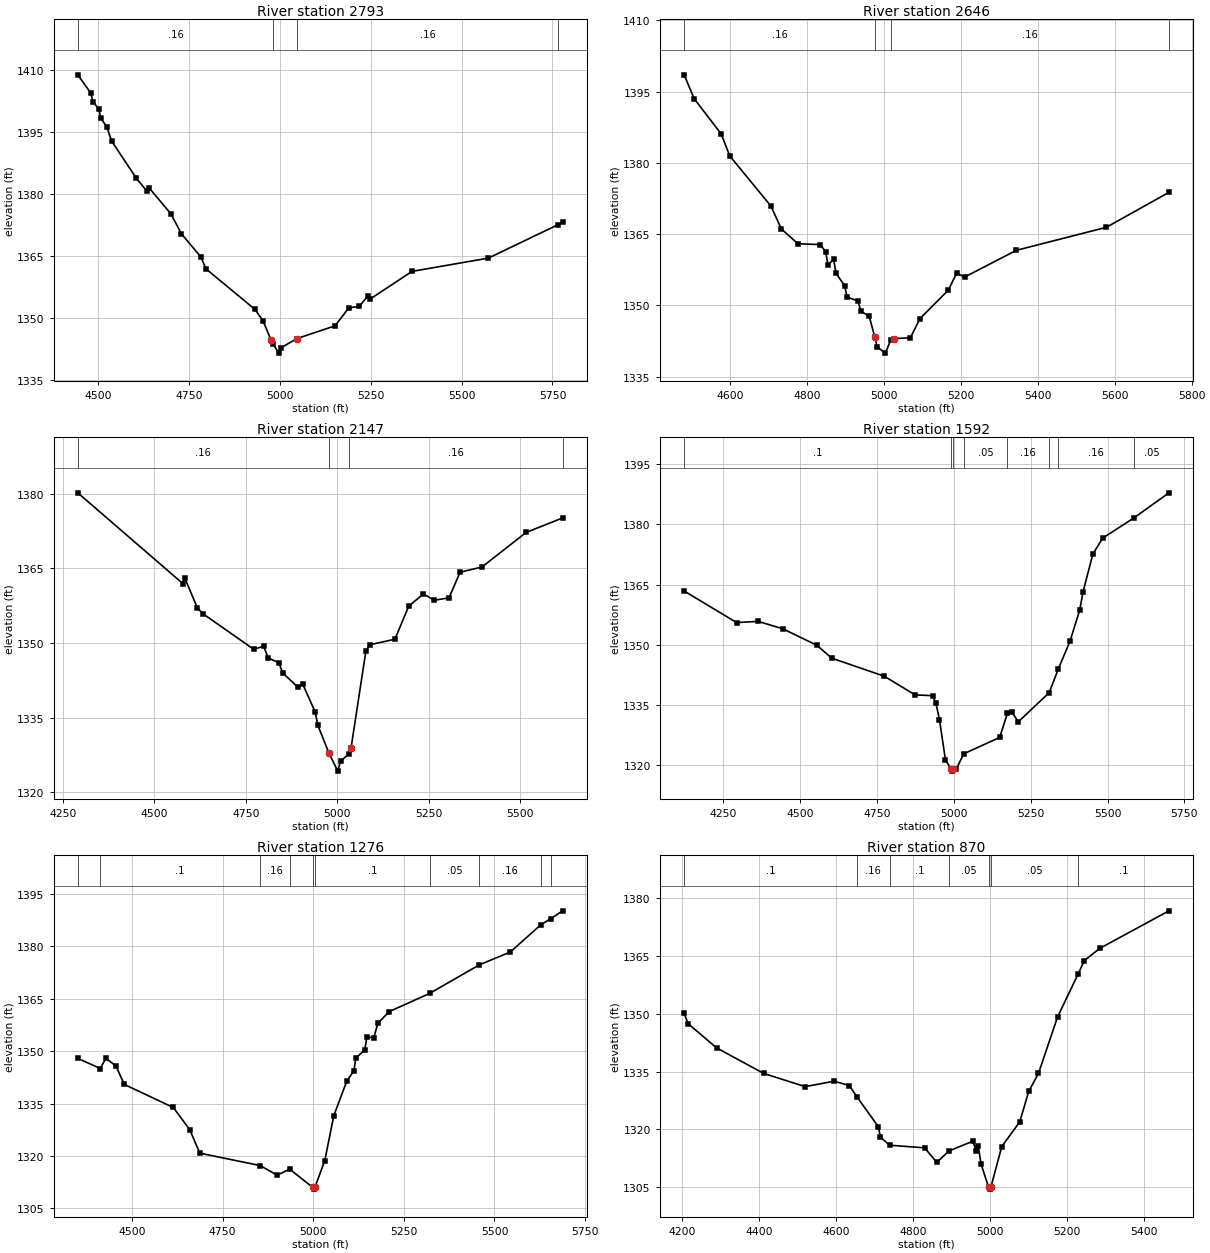
Type RM Length L Ch R = 1 ,2793    ,147,147,147
BEGIN DESCRIPTION:
Mapping XS edd7fef4
END DESCRIPTION:
XS GIS Cut Line= 4
      2886420.88     10105109.73      2885743.75     10105465.65
      2885570.14     10105531.62      2885282.73     10105786.14
#Sta/Elev= 30
  4443.3 1408.83  4479.2 1404.42  4484.9 1402.38  4501.3 1400.52  4506.9 1398.33
  4523.3 1396.22  4536.4 1392.83  4604.2 1383.87  4633.5 1380.73  4639.2 1381.55
  4699.6 1375.25  4728.5 1370.43  4782.2 1364.81  4796.2 1361.94  4930.8 1352.16
  4952.9 1349.45  4974.9 1344.85  4980.6 1343.83  4996.7 1341.58  5002.6 1342.88
  5046.7  1345.1  5151.3 1348.17  5189.7 1352.55  5218.1 1352.87  5242.9 1355.49
  5248.2 1354.66  5363.7 1361.34  5573.6 1364.54  5765.1 1372.61  5777.9 1373.34
#Mann= 4 ,-1 , 0
  4443.3     .16       0  4980.6     .07       0  5046.7     .16       0
  5765.1     .05       0
Bank Sta=4974.9,5046.7
XS Rating Curve= 0 ,0
Exp/Cntr=0.3,0.1

Type RM Length L Ch R = 1 ,2646    ,499,499,499
BEGIN DESCRIPTION:
Mapping XS 0bce73cc
END DESCRIPTION:
XS GIS Cut Line= 3
      2886222.88     10104951.79      2885747.22     10105342.39
        2885274.     10105779.21
#Sta/Elev= 30
  4481.5 1398.53  4507.4 1393.53  4577.8 1386.09    4600 1381.46  4706.9 1370.92
  4734.2 1366.07  4777.2 1362.98  4834.6  1362.8    4849 1361.34  4855.4 1358.49
  4869.8 1359.72  4876.2 1356.75  4898.5 1354.12  4904.9 1351.75  4933.6  1350.9
  4940.1 1348.82  4962.3 1347.71  4976.6 1343.38  4983.2 1341.23  5004.5 1339.95
  5018.3 1342.77  5026.2 1343.02  5069.2 1343.18  5094.1 1347.21  5167.7  1353.2
  5189.3 1356.78  5210.3 1355.97  5344.6 1361.59  5578.3 1366.43    5741 1373.79
#Mann= 4 ,-1 , 0
  4481.5     .16       0  4976.6     .07       0  5018.3     .16       0
    5741     .05       0
Bank Sta=4976.6,5026.2
XS Rating Curve= 0 ,0
Exp/Cntr=0.3,0.1

Type RM Length L Ch R = 1 ,2147    ,555,555,555
BEGIN DESCRIPTION:
UNT 1046 IN LATR 4.0
END DESCRIPTION:
XS GIS Cut Line= 4
      2885978.61     10104932.85      2885388.31     10105093.45
      2885284.14     10105323.49      2885253.76     10105783.51
#Sta/Elev= 30
  4290.4  1380.2  4577.5 1361.97  4582.7 1363.12  4617.3 1357.07  4632.5  1355.9
  4771.2 1348.77  4798.4 1349.37  4810.9 1347.02  4839.8 1346.07  4850.7    1344
  4891.6 1341.18  4905.1 1341.79  4939.5 1336.13  4946.4 1333.56  4976.6 1327.96
    5001 1324.28  5008.8 1326.32  5031.9 1327.73  5037.4 1328.94  5078.1 1348.47
  5089.1 1349.68  5157.3 1350.78    5195 1357.42  5235.1 1359.88  5265.2 1358.62
  5305.3  1359.1  5335.3 1364.24  5395.4  1365.3  5515.7 1372.23  5615.7 1375.15
#Mann= 4 ,-1 , 0
  4290.4     .16       0  4976.6     .07       0  5031.9     .16       0
  5615.7     .05       0
Bank Sta=4976.6,5037.4
XS Rating Curve= 0 ,0
Exp/Cntr=0.3,0.1

Type RM Length L Ch R = 1 ,1592    ,316,316,316
BEGIN DESCRIPTION:
UNT 1046 IN LATR 3.0
END DESCRIPTION:
XS GIS Cut Line= 4
      2885679.08     10104793.97      2884915.22     10104833.03
      2884811.05     10105110.81      2884637.44     10105596.92
#Sta/Elev= 30
  4122.2  1363.4    4293 1355.54  4363.1 1355.83  4443.2    1354  4553.4 1349.92
  4602.7 1346.68  4773.7 1342.18  4873.8 1337.54  4930.5 1337.35  4941.2 1335.59
  4953.1 1331.38  4972.7  1321.3  4991.6 1319.07  4994.4 1318.57  4997.6 1319.07
  5008.3 1319.14  5032.1 1322.89  5148.9 1326.94  5174.1 1332.92  5187.9 1333.35
  5209.8 1330.85  5310.2 1338.11  5340.2 1344.07    5378 1350.92  5409.5 1358.65
  5420.4 1363.22  5452.3 1372.59  5484.1 1376.55  5585.6 1381.57  5699.9 1387.83
#Mann= 8 ,-1 , 0
  4122.2      .1       0  4991.6     .07       0  4997.6      .1       0
  5032.1     .05       0  5174.1     .16       0  5310.2      .1       0
  5340.2     .16       0  5585.6     .05       0
Bank Sta=4991.6,4997.6
XS Rating Curve= 0 ,0
Exp/Cntr=0.3,0.1

Type RM Length L Ch R = 1 ,1276    ,406,406,406
BEGIN DESCRIPTION:
UNT 1046 IN LATR 2.0
END DESCRIPTION:
XS GIS Cut Line= 4
      2885058.48     10104472.78      2884637.44     10104676.78
      2884459.49     10105154.21      2884398.85      10105509.4
#Sta/Elev= 30
  4350.3 1347.94  4412.4 1345.03  4427.7 1347.94  4455.8 1345.74  4478.4 1340.48
  4613.8 1333.86    4659 1327.55  4687.1 1320.77  4853.6 1317.22  4900.3 1314.47
    4935 1316.19  4998.5 1310.97  5001.2 1310.47  5004.5 1310.97  5031.8 1318.65
  5056.8 1331.55  5092.5 1341.42  5112.1  1344.4  5117.5 1347.99  5142.4 1350.43
  5147.8 1354.06  5167.1 1353.84  5178.1 1357.97  5209.8 1361.34  5321.3 1366.56
  5457.7  1374.7  5543.5  1378.4  5627.1 1386.14  5655.8    1388    5688 1390.21
#Mann= 10 ,-1 , 0
  4350.3     .05       0  4412.4      .1       0  4853.6     .16       0
    4935      .1       0  4998.5     .07       0  5004.5      .1       0
  5321.3     .05       0  5457.7     .16       0  5627.1      .1       0
  5655.8     .05       0
Bank Sta=4998.5,5004.5
XS Rating Curve= 0 ,0
Exp/Cntr=0.3,0.1

Type RM Length L Ch R = 1 ,870     ,284,284,284
BEGIN DESCRIPTION:
Mapping XS 9ecb7906
END DESCRIPTION:
XS GIS Cut Line= 4
      2884898.48     10104438.03      2884262.86     10104606.93
      2884173.97     10104829.17      2884165.08     10105193.63
#Sta/Elev= 30
  4204.3 1350.11  4214.7  1347.4  4288.6 1341.15  4411.3 1334.51  4519.2 1331.09
  4594.4 1332.49  4634.5 1331.37  4653.5 1328.49  4709.7 1320.73  4714.9 1318.05
  4738.9 1315.91  4830.2 1315.23  4861.7 1311.46  4893.4 1314.41  4955.5 1316.95
  4964.4 1314.47  4969.8 1315.63    4977 1311.02  4996.5 1305.03  4999.2 1304.53
  5002.5 1305.03  5030.8 1315.56  5077.5 1321.93  5101.1 1329.88  5126.4 1334.53
  5175.9 1349.11  5229.6  1360.3  5245.9 1363.77  5285.9 1366.92  5465.9 1376.65
#Mann= 7 ,-1 , 0
  4204.3      .1       0  4653.5     .16       0  4738.9      .1       0
  4893.4     .05       0  4996.5    .035       0  5002.5     .05       0
  5229.6      .1       0
Bank Sta=4996.5,5002.5
XS Rating Curve= 0 ,0
Exp/Cntr=0.3,0.1

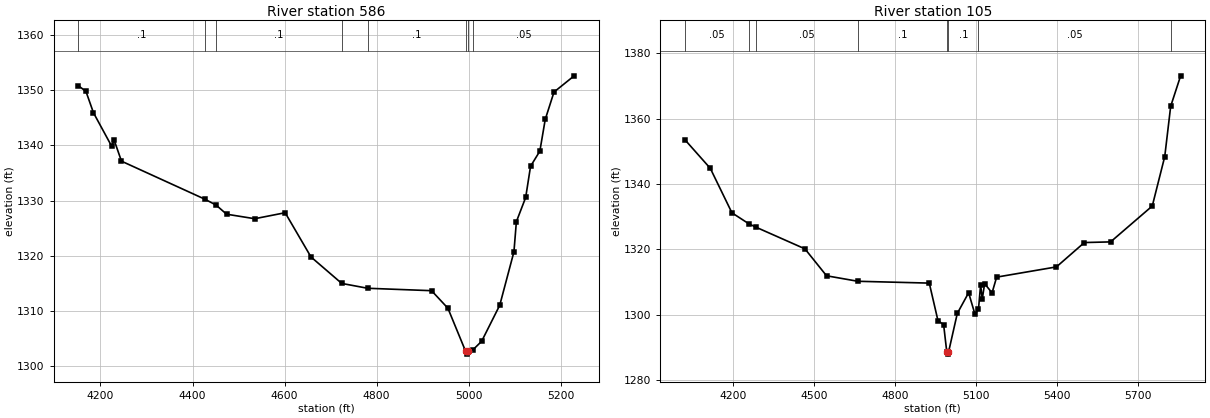
Type RM Length L Ch R = 1 ,586     ,481,481,481
BEGIN DESCRIPTION:
Mapping XS 74bf886f
END DESCRIPTION:
XS GIS Cut Line= 3
       2884810.9     10104356.23      2884053.99     10104481.22
      2883949.81     10104772.91
#Sta/Elev= 30
    4152 1350.86  4168.5 1349.84  4184.9 1345.94  4224.5 1339.85  4229.6 1341.02
  4245.7 1337.15    4427 1330.23  4451.2 1329.17    4474 1327.51  4535.1 1326.69
  4601.2 1327.78  4657.3 1319.74  4724.1 1314.93  4780.3 1314.05  4919.2 1313.61
  4954.7 1310.42  4993.2 1302.58  4995.9 1302.08  4999.2 1302.58  5009.6 1302.91
    5028 1304.42  5067.3 1310.97  5098.1 1320.68  5103.4 1326.15  5123.6 1330.55
  5134.2 1336.22  5154.4 1338.98  5166.1 1344.74  5185.1 1349.71  5228.9 1352.66
#Mann= 8 ,-1 , 0
    4152      .1       0    4427     .05       0  4451.2      .1       0
  4724.1     .05       0  4780.3      .1       0  4993.2     .07       0
  4999.2      .1       0  5009.6     .05       0
Bank Sta=4993.2,4999.2
XS Rating Curve= 0 ,0
Exp/Cntr=0.3,0.1

Type RM Length L Ch R = 1 ,105     ,0,0,0
BEGIN DESCRIPTION:
UNT 1046 IN LATR 1.0
END DESCRIPTION:
XS GIS Cut Line= 4
      2884772.78     10104193.03      2883863.01     10104161.78
       2883689.4     10104283.31      2883901.22     10104963.89
#Sta/Elev= 30
  4022.2 1353.57  4116.6 1344.78  4196.6 1331.18  4259.4 1327.81  4284.5 1326.82
  4466.8 1320.15  4546.8 1311.91  4662.6 1310.23    4927 1309.67  4959.2 1298.17
  4980.1 1296.96    4992 1288.44  4994.7 1287.94    4998 1288.44  5030.7  1300.4
  5072.6 1306.72  5096.1 1300.13  5109.1 1301.71    5117 1309.11  5123.1 1304.82
  5131.8  1309.5  5159.3 1306.68  5176.3  1311.5  5397.6 1314.63  5500.9 1322.08
    5598 1322.28  5752.3 1333.26  5798.4 1348.38  5820.4 1363.77  5857.2 1373.09
#Mann= 8 ,-1 , 0
  4022.2     .05       0  4259.4      .1       0  4284.5     .05       0
  4662.6      .1       0    4992     .07       0    4998      .1       0
  5109.1     .05       0  5820.4      .1       0
Bank Sta=4992,4998
XS Rating Curve= 0 ,0
Exp/Cntr=0.3,0.1

Chan Stop Cuts=-1
Use User Specified Reach Order=0
Composite Channel Slope=5