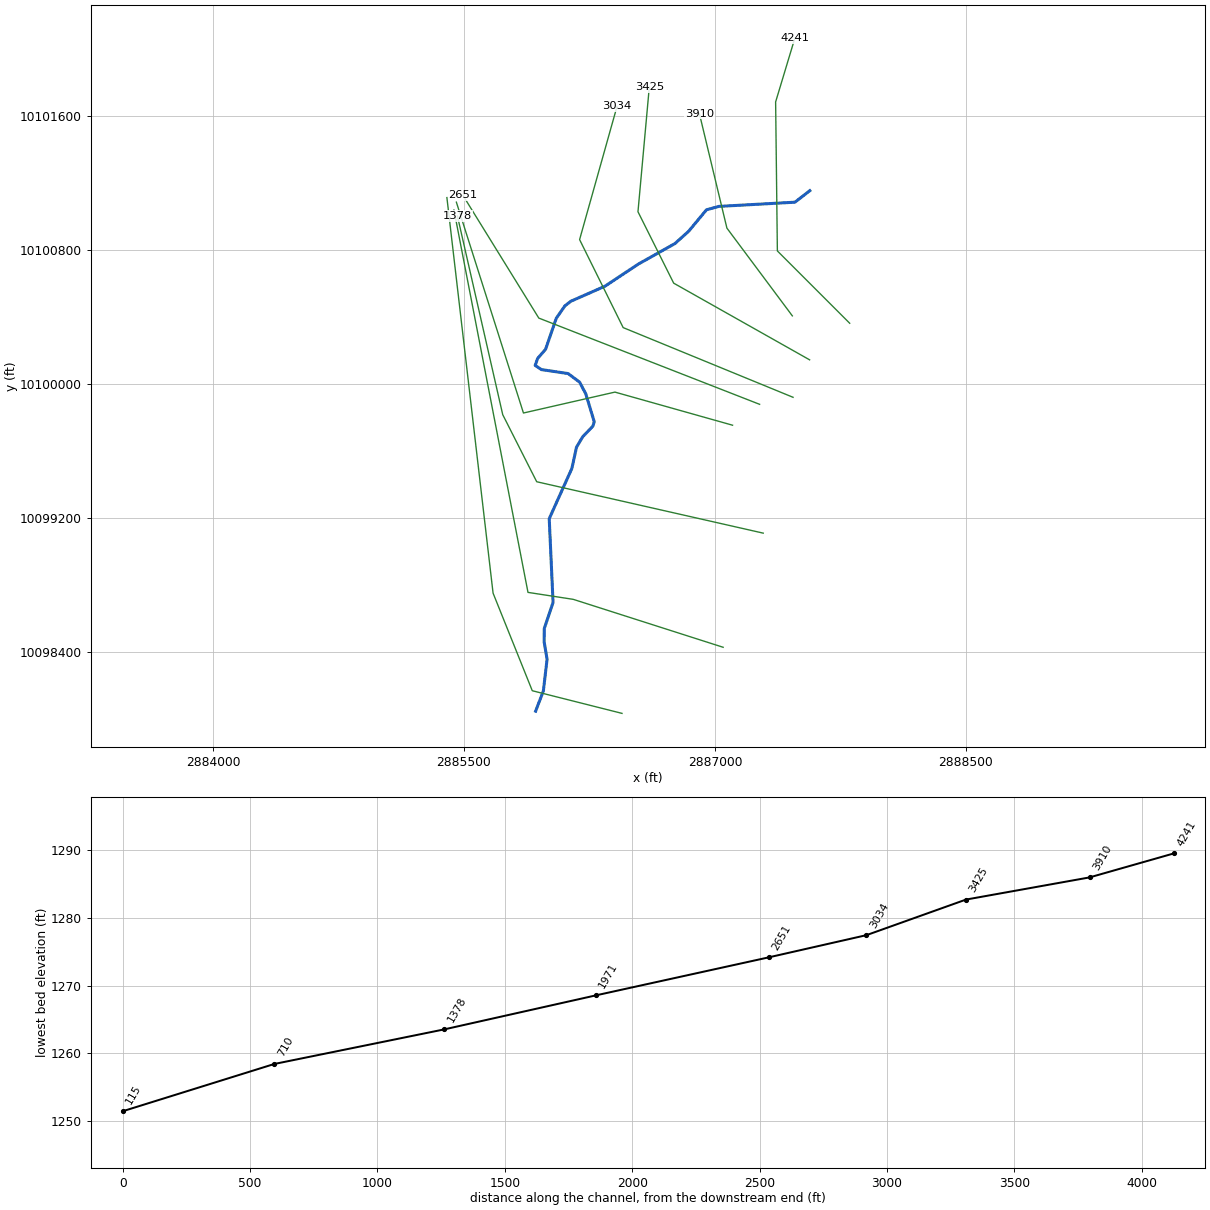
--- UNT 0047 IN LATR.prj (project) ---

Proj Title=UNT 1047 IN LATR Base Level Engineering
Current Plan=p01
Default Exp/Contr=0.3,0.1
English Units
Geom File=g01
Flow File=f01
Plan File=p01
Y Axis Title=Elevation
X Axis Title(PF)=Main Channel Distance
X Axis Title(XS)=Station
BEGIN DESCRIPTION:
UNT 1047 IN LATR
END DESCRIPTION:
DSS Export Rating Curves= 0
DSS Export Rating Curve Sorted= 0
DSS Export Volume Flow Curves= 0
DXF OffsetX= 0
DXF OffsetY= 0
DXF ScaleX= 1
DXF ScaleY= 10

--- UNT 0047 IN LATR.p01 (plan) ---

Plan Title=Multiple Run
Short Identifier=Multiple
Geom File=g01
Flow File=f01
Subcritical Flow
K Sum by GR= 0
Std Step Tol= 0.01
Critical Tol= 0.01
Num of Std Step Trials= 20
Max Error Tol= 0.3
Flow Tol Ratio= 0.001
Split Flow NTrial= 30
Split Flow Tol= 0.02
Split Flow Ratio= 0.02
Log Output Level= 0
Friction Slope Method= 1
Unsteady Friction Slope Method= 2
Unsteady Bridges Friction Slope Method= 1
Parabolic Critical Depth
Global Vel Dist=  1 , 1 , 1
Global Log Level= 0
CheckData=True
Encroach Param= -1, 0, 0, 0
BEGIN DESCRIPTION:
Multiple Run
END DESCRIPTION:

--- UNT 0047 IN LATR.f01 (steady flow) ---

Flow Title=Multiple
Number of Profiles=7
Profile Names=10-year,25-year,50-year,1pct_min,100-year,1pct_plu,500-year
River Rch & RM= UNT 1047 IN LATR,Reach-1,4241
    1141    1679    2153    2019    2730    3693    4410
Boundary for River Rch & Prof#=UNT 1047 IN LATR,Reach-1,1
Up Type=0
Dn Type=3
Dn Slope=0.005
Boundary for River Rch & Prof#=UNT 1047 IN LATR,Reach-1,2
Up Type=0
Dn Type=3
Dn Slope=0.005
Boundary for River Rch & Prof#=UNT 1047 IN LATR,Reach-1,3
Up Type=0
Dn Type=3
Dn Slope=0.005
Boundary for River Rch & Prof#=UNT 1047 IN LATR,Reach-1,4
Up Type=0
Dn Type=3
Dn Slope=0.005
Boundary for River Rch & Prof#=UNT 1047 IN LATR,Reach-1,5
Up Type=0
Dn Type=3
Dn Slope=0.005
Boundary for River Rch & Prof#=UNT 1047 IN LATR,Reach-1,6
Up Type=0
Dn Type=3
Dn Slope=0.005
Boundary for River Rch & Prof#=UNT 1047 IN LATR,Reach-1,7
Up Type=0
Dn Type=3
Dn Slope=0.005

--- UNT 0047 IN LATR.g01 (geometry) ---

Geom Title=Existing Conditions
Program Version=4.10

River Reach=UNT 1047 IN LATR,Reach-1
Reach XY= 30
      2887567.43     10101154.97      2887478.59      10101086.1
      2887023.24     10101060.99      2886949.69     10101040.61
      2886843.02     10100912.15      2886761.15     10100838.78
      2886542.23     10100716.03      2886343.32     10100584.08
      2886138.47     10100493.73      2886103.47     10100466.36
      2886051.91     10100392.31      2885987.94      10100207.2
      2885940.48     10100152.27      2885925.61     10100110.39
      2885963.27     10100085.48      2886122.71     10100061.67
      2886191.68     10100009.98       2886228.4     10099940.14
       2886278.7     10099773.81      2886270.65     10099747.35
      2886209.77     10099683.74       2886172.7     10099621.37
      2886145.29     10099495.05       2886009.7     10099194.07
      2886032.66      10098693.6      2885980.25     10098537.96
      2885979.12     10098459.06       2885996.9     10098354.07
      2885974.63     10098164.24      2885928.47     10098043.73

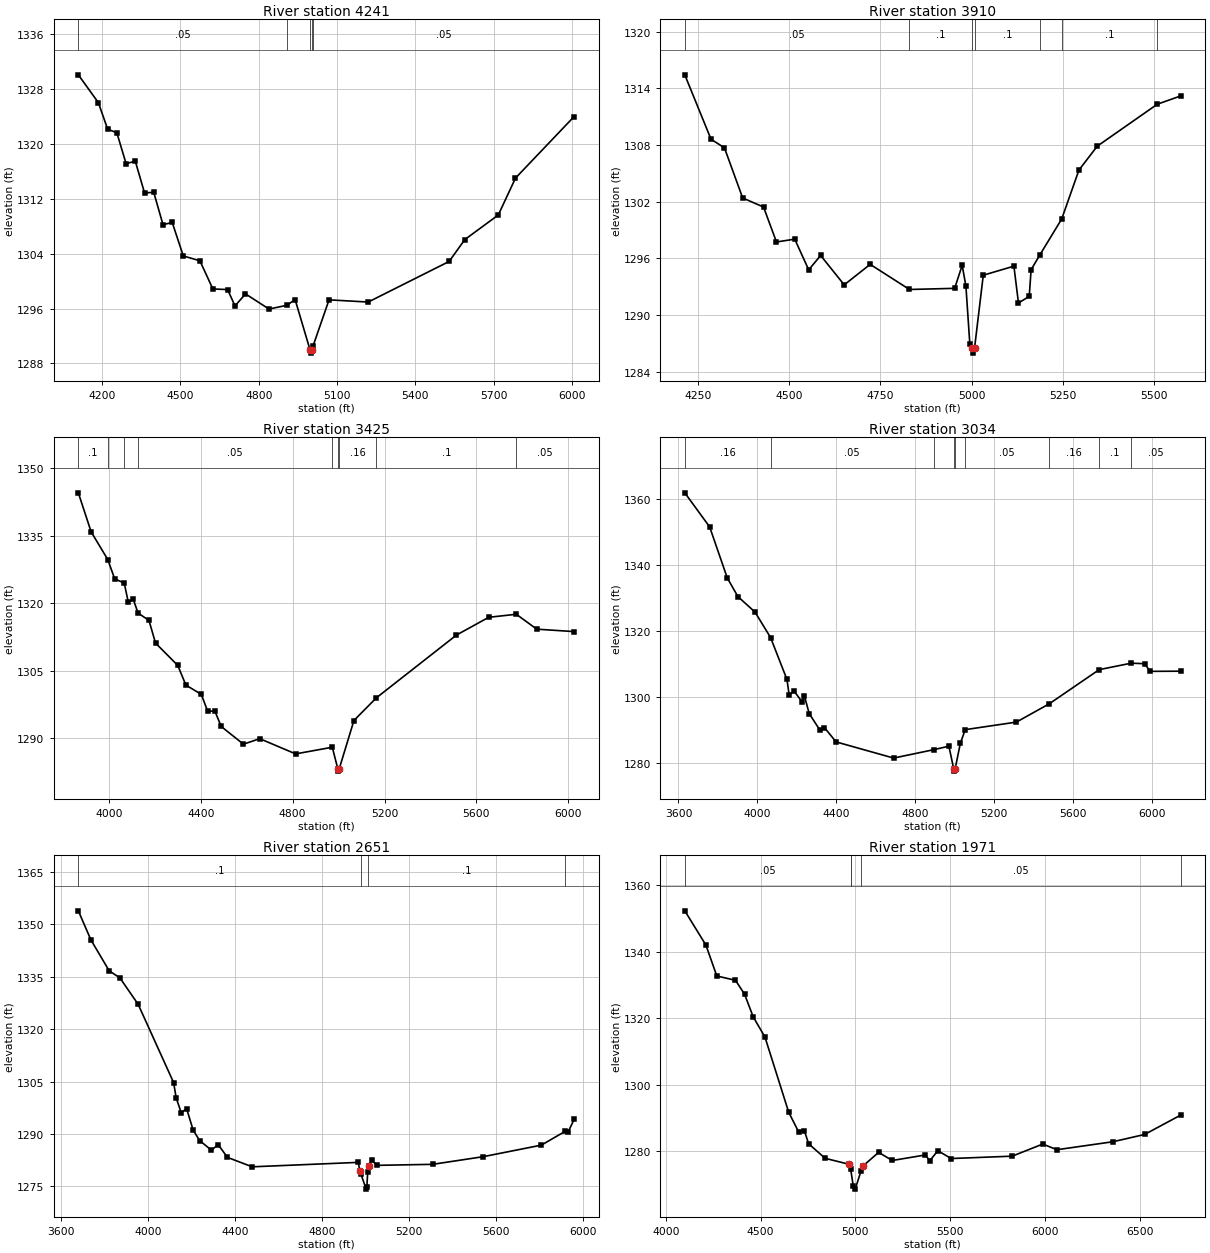
Type RM Length L Ch R = 1 ,4241    ,331,331,331
BEGIN DESCRIPTION:
UNT 1047 IN LATR 4.0
END DESCRIPTION:
XS GIS Cut Line= 4
      2887805.87     10100362.52      2887373.55     10100794.84
      2887363.13     10101685.46      2887477.73      10102065.7
#Sta/Elev= 30
  4108.9  1330.1  4185.7 1326.04  4221.1 1322.18  4256.4 1321.65  4291.8 1317.15
  4327.1  1317.5  4362.5 1312.88  4397.8 1312.96  4433.2 1308.24  4468.5 1308.57
    4511 1303.68  4574.6 1302.98  4624.1 1298.87  4680.7 1298.78    4709 1296.39
  4749.2 1298.15  4839.2 1295.94  4908.1 1296.49  4939.2 1297.33  4996.2 1290.01
    4999 1289.51  5002.2 1290.01  5007.5  1290.5  5069.2 1297.28  5219.2 1296.96
  5529.2 1302.88  5589.2 1306.07  5717.5 1309.66  5783.4 1315.04  6008.1 1324.02
#Mann= 5 ,-1 , 0
  4108.9     .05       0  4908.1      .1       0  4996.2     .07       0
  5002.2      .1       0  5007.5     .05       0
Bank Sta=4996.2,5002.2
XS Rating Curve= 0 ,0
Exp/Cntr=0.3,0.1

Type RM Length L Ch R = 1 ,3910    ,485,485,485
BEGIN DESCRIPTION:
Mapping XS 7e2c409f
END DESCRIPTION:
XS GIS Cut Line= 3
      2887463.05     10100406.68       2887071.9     10100931.18
      2886907.46     10101615.61
#Sta/Elev= 30
  4214.5 1315.44  4286.3 1308.62  4323.1 1307.71    4373  1302.4  4430.2 1301.44
  4465.6 1297.74  4515.7 1298.04  4553.9 1294.79  4586.6 1296.31  4651.2  1293.2
  4722.3 1295.37  4829.9 1292.71  4953.7 1292.83  4974.3 1295.27  4984.5 1293.08
  4995.2 1286.98  5002.1 1286.47  5004.9 1285.97  5008.1 1286.47  5032.1 1294.22
    5116 1295.18  5128.5 1291.28    5158 1291.98  5163.1  1294.8  5187.7 1296.41
  5246.9 1300.17  5294.2 1305.36  5344.5 1307.89  5508.9 1312.33  5572.7  1313.2
#Mann= 7 ,-1 , 0
  4214.5     .05       0  4829.9      .1       0  5002.1     .07       0
  5008.1      .1       0  5187.7     .05       0  5246.9      .1       0
  5508.9     .05       0
Bank Sta=5002.1,5008.1
XS Rating Curve= 0 ,0
Exp/Cntr=0.3,0.1

Type RM Length L Ch R = 1 ,3425    ,391,391,391
BEGIN DESCRIPTION:
UNT 1047 IN LATR 3.0
END DESCRIPTION:
XS GIS Cut Line= 4
      2887566.27     10100143.79      2886753.76     10100602.13
      2886540.22     10101029.21      2886607.92     10101773.97
#Sta/Elev= 30
  3867.2 1344.55  3922.9 1335.88  3995.4 1329.72  4025.4 1325.42    4067  1324.5
  4084.7 1320.23  4106.3 1320.89    4127 1317.84  4174.7 1316.19  4203.1 1311.17
    4300 1306.19  4335.4 1301.82  4402.5 1299.76  4429.9 1296.05  4461.7 1296.02
  4489.1 1292.62  4585.9 1288.69  4656.9 1289.91    4813 1286.53  4972.6 1288.01
  4996.7  1283.2  4999.5  1282.7  5002.7  1283.2  5066.8 1293.95    5164 1298.97
  5513.1 1312.94  5653.6 1316.89  5773.7 1317.56  5862.6 1314.25  6025.4 1313.71
#Mann= 9 ,-1 , 0
  3867.2      .1       0  3995.4     .05       0    4067      .1       0
    4127     .05       0  4972.6     .16       0  4996.7     .07       0
  5002.7     .16       0    5164      .1       0  5773.7     .05       0
Bank Sta=4996.7,5002.7
XS Rating Curve= 0 ,0
Exp/Cntr=0.3,0.1

Type RM Length L Ch R = 1 ,3034    ,383,383,383
BEGIN DESCRIPTION:
UNT 1047 IN LATR 2.0
END DESCRIPTION:
XS GIS Cut Line= 4
      2887467.31     10099919.84      2886451.68     10100336.51
      2886191.26     10100862.55      2886415.11     10101659.04
#Sta/Elev= 30
  3632.3 1361.91  3758.2 1351.57  3847.2 1336.12  3901.3 1330.42  3987.7 1325.75
  4066.8    1318  4149.9 1305.26  4161.2  1300.5  4185.2 1301.78  4225.5 1298.58
  4238.6  1300.2  4262.5 1294.93  4315.9 1289.97  4339.9 1290.65  4398.7 1286.32
  4690.3 1281.41  4894.5 1283.97  4970.4 1285.02  4995.4 1277.95  4998.2 1277.45
  5001.4 1277.95  5028.3 1285.89  5053.2 1290.04  5312.4 1292.33    5479 1297.89
  5731.9 1308.25    5894 1310.21  5962.3 1310.05  5989.4 1307.73  6144.4 1307.78
#Mann= 9 ,-1 , 0
  3632.3     .16       0  4066.8     .05       0  4894.5      .1       0
  4995.4     .07       0  5001.4      .1       0  5053.2     .05       0
    5479     .16       0  5731.9      .1       0    5894     .05       0
Bank Sta=4995.4,5001.4
XS Rating Curve= 0 ,0
Exp/Cntr=0.3,0.1

Type RM Length L Ch R = 1 ,2651    ,680,680,680
BEGIN DESCRIPTION:
Mapping XS fad0f937
END DESCRIPTION:
XS GIS Cut Line= 3
      2887267.44      10099877.8       2885947.4     10100393.37
      2885494.06     10101126.71
#Sta/Elev= 30
  3680.8 1353.88  3738.5 1345.57  3822.7  1336.7  3871.7 1334.69  3955.8 1327.11
  4118.8 1304.69  4130.6 1300.32    4154 1296.01  4178.5 1297.26  4208.4 1291.12
  4238.2  1288.1  4292.5 1285.33  4323.8 1286.93    4366 1283.28    4480 1280.57
    4968 1281.84  4974.3 1279.45  4979.7 1278.52  5003.9 1274.18  5007.1 1274.68
  5010.9 1279.04  5016.8 1280.72  5028.6 1282.52  5053.1 1280.99  5309.4 1281.28
    5541 1283.46  5809.4 1286.78  5919.3 1290.75  5933.1 1290.64  5960.1 1294.17
#Mann= 4 ,-1 , 0
  3680.8      .1       0  4979.7     .05       0  5010.9      .1       0
  5919.3     .05       0
Bank Sta=4974.3,5016.8
XS Rating Curve= 0 ,0
Exp/Cntr=0.3,0.1

Type RM Length L Ch R = 1 ,1971    ,593,593,593
BEGIN DESCRIPTION:
Mapping XS f86b3a66
END DESCRIPTION:
XS GIS Cut Line= 4
      2887105.68     10099752.99      2886402.53     10099950.91
      2885855.66     10099825.91      2885454.63      10101086.3
#Sta/Elev= 30
  4100.4 1352.24  4211.8 1341.93  4269.1 1332.65  4367.6 1331.35  4415.6 1327.16
  4461.1 1320.34  4522.9 1314.31  4648.1 1291.69  4700.1 1285.81  4731.2 1286.06
  4753.1 1282.21  4840.4 1277.82  4968.4 1276.01  4974.4 1274.72  4988.9 1269.42
  4998.9 1268.56  5029.9  1274.1  5040.2 1275.52  5122.3 1279.62  5194.1 1277.17
  5368.5 1278.83  5391.9 1277.09  5434.4  1280.1    5505 1277.76  5826.5 1278.47
  5987.6 1282.11  6062.6 1280.41  6357.9 1282.81  6524.3 1284.99  6714.5 1290.81
#Mann= 5 ,-1 , 0
  4100.4     .05       0  4974.4    .035       0  4974.4    .035       0
  5029.9     .05       0  6714.5     .05       0
Bank Sta=4968.4,5040.2
XS Rating Curve= 0 ,0
Exp/Cntr=0.3,0.1

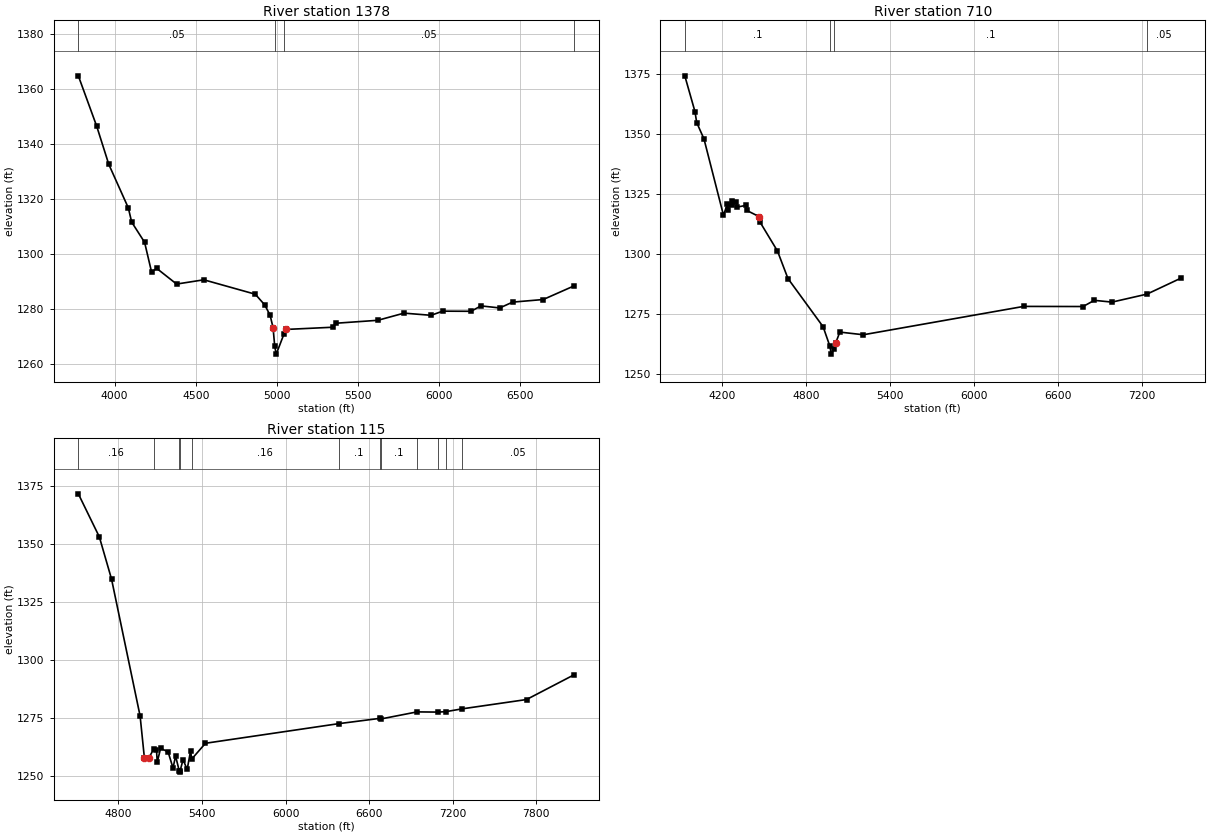
Type RM Length L Ch R = 1 ,1378    ,668,668,668
BEGIN DESCRIPTION:
Mapping XS c724b6e4
END DESCRIPTION:
XS GIS Cut Line= 4
      2887289.06     10099107.75      2885934.86     10099415.05
      2885731.73     10099816.09      2885460.89     10101003.62
#Sta/Elev= 30
  3776.3 1364.92  3889.7 1346.54    3964 1332.68  4084.5 1316.81    4105 1311.65
  4184.7  1304.3  4227.8 1293.43  4258.9 1294.81  4381.9 1289.08    4550 1290.63
  4867.1 1285.38  4925.4 1281.47  4958.4 1277.72  4976.7 1273.16  4986.9 1266.34
  4996.2 1263.56  5044.7 1271.02  5058.7 1272.56  5346.7 1273.36  5363.4 1274.81
  5622.3 1275.88  5783.9 1278.49  5950.5  1277.7  6022.3 1279.21  6196.7 1279.16
  6258.2 1281.13  6373.7 1280.38  6453.1  1282.5  6641.9 1283.45  6832.5 1288.43
#Mann= 4 ,-1 , 0
  3776.3     .05       0  4986.9    .035       0  5044.7     .05       0
  6832.5     .05       0
Bank Sta=4976.7,5058.7
XS Rating Curve= 0 ,0
Exp/Cntr=0.3,0.1

Type RM Length L Ch R = 1 ,710     ,595,595,595
BEGIN DESCRIPTION:
Mapping XS 27fd4e49
END DESCRIPTION:
XS GIS Cut Line= 4
      2887049.42     10098425.47      2886153.61     10098711.93
      2885882.77     10098753.59      2885440.19     10101039.42
#Sta/Elev= 30
  3933.7 1374.39  4006.5 1359.45  4018.7 1354.92  4070.8 1348.09    4210 1316.31
  4236.9  1320.8  4242.2 1318.69  4269.1 1322.36  4274.3 1320.73  4301.2 1321.69
  4306.5 1319.69  4370.8 1320.42  4376.1 1318.33  4467.3 1315.66  4472.6 1313.32
    4596 1301.39  4670.8 1289.94  4921.9 1269.87  4970.5 1261.73  4979.9 1258.45
  5000.8 1260.61  5010.9 1262.91  5041.3 1267.63  5209.5 1266.52  6354.9 1278.33
  6779.3 1278.28  6859.6 1280.86  6986.3 1280.12  7236.4 1283.46  7476.5 1290.04
#Mann= 4 ,-1 , 0
  3933.7      .1       0  4970.5     .05       0  5000.8      .1       0
  7236.4     .05       0
Bank Sta=4467.3,5010.9
XS Rating Curve= 0 ,0
Exp/Cntr=0.3,0.1

Type RM Length L Ch R = 1 ,115     ,0,0,0
BEGIN DESCRIPTION:
Mapping XS a62fd44a
END DESCRIPTION:
XS GIS Cut Line= 4
      2886444.86     10098030.33      2885908.42     10098165.74
      2885674.05     10098749.07        2885398.      10101113.7
#Sta/Elev= 30
  4511.4  1371.6  4662.4    1353    4750 1334.79  4955.3 1275.69 4986.13 1257.59
 5016.56 1257.51  5052.8 1261.38  5072.9 1261.07  5078.3 1255.78  5102.5 1261.75
  5156.3 1260.24  5191.8 1253.22    5210 1258.45  5236.6 1251.98  5239.4 1251.48
  5242.6 1251.98  5263.8 1256.88  5293.4 1252.64  5317.6 1260.54  5326.7 1257.17
  5425.1 1263.94  6380.9 1272.39  6677.7 1274.68  6688.9 1274.47  6945.2 1277.48
  7097.1 1277.39  7154.1  1277.6  7267.5 1278.78  7731.7 1282.81    8074 1293.51
#Mann= 12 ,-1 , 0
  4511.4     .16       0  5052.8      .1       0  5236.6     .07       0
  5242.6      .1       0  5326.7     .16       0  6380.9      .1       0
  6677.7     .16       0  6688.9      .1       0  6945.2     .16       0
  7097.1      .1       0  7154.1     .16       0  7267.5     .05       0
Bank Sta=4986.13,5016.56
XS Rating Curve= 0 ,0
Exp/Cntr=0.3,0.1

Chan Stop Cuts=-1
Use User Specified Reach Order=0
Composite Channel Slope=5