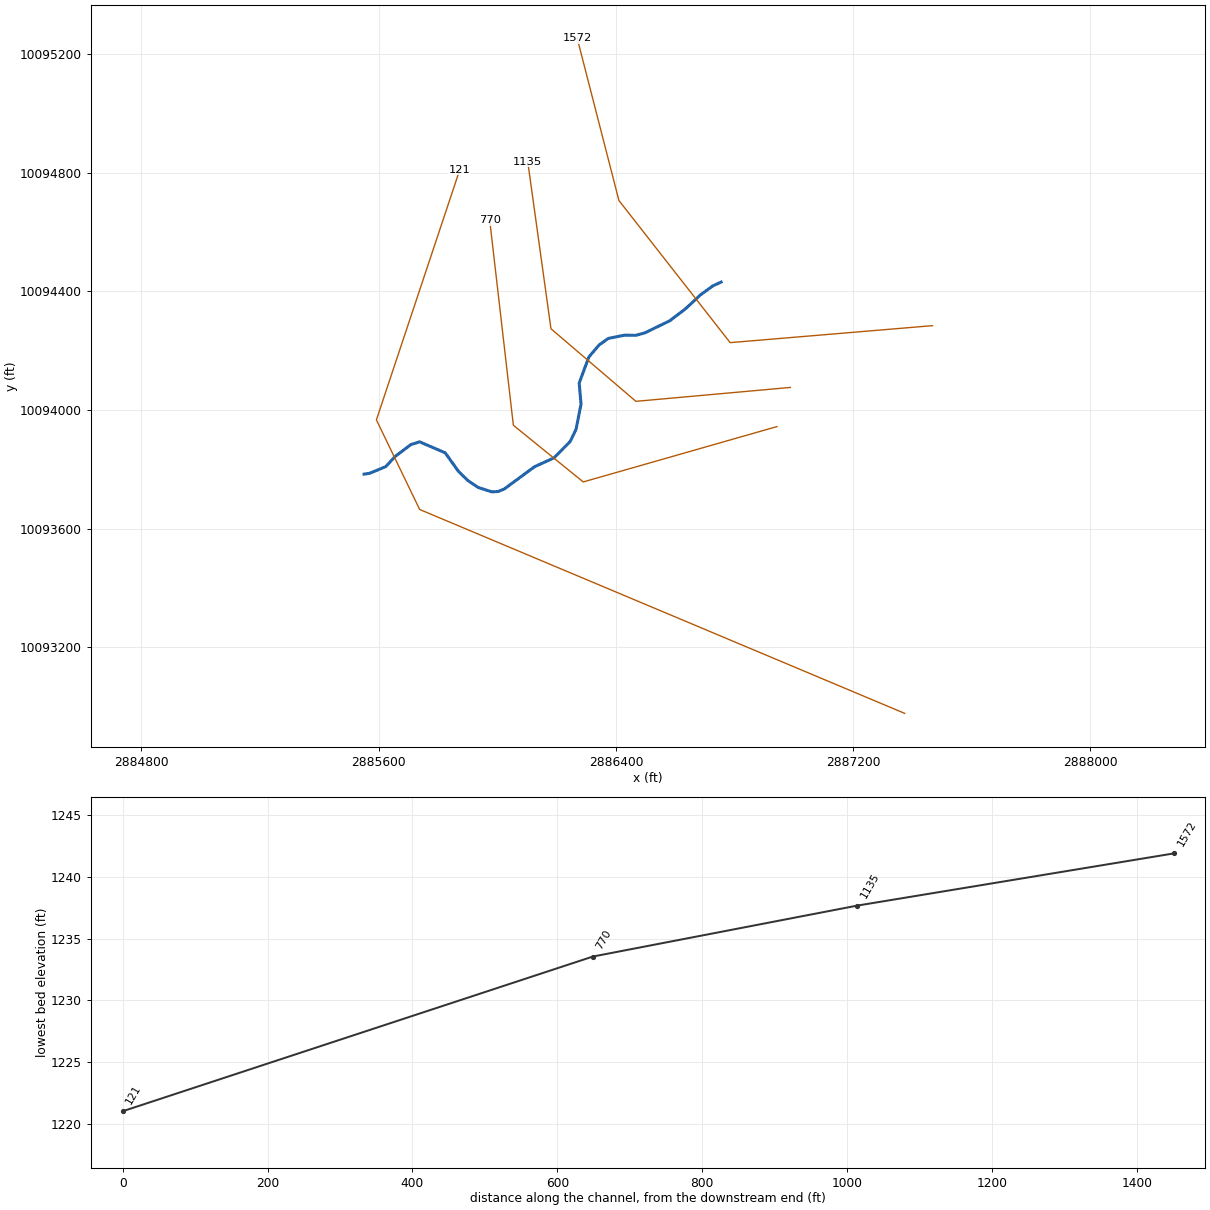
--- UNT 0048 IN LATR.prj (project) ---

Proj Title=UNT 1048 IN LATR Base Level Engineering
Current Plan=p01
Default Exp/Contr=0.3,0.1
English Units
Geom File=g01
Flow File=f01
Plan File=p01
BEGIN DESCRIPTION:
UNT 1048 IN LATR
END DESCRIPTION:

--- UNT 0048 IN LATR.p01 (plan) ---

Plan Title=Multiple Run
Short Identifier=Multiple
Geom File=g01
Flow File=f01
Subcritical Flow
K Sum by GR= 0
Std Step Tol= 0.01
Critical Tol= 0.01
Num of Std Step Trials= 20
Max Error Tol= 0.3
Flow Tol Ratio= 0.001
Split Flow NTrial= 30
Split Flow Tol= 0.02
Split Flow Ratio= 0.02
Log Output Level= 0
Friction Slope Method= 1
Unsteady Friction Slope Method= 2
Unsteady Bridges Friction Slope Method= 1
Parabolic Critical Depth
Global Vel Dist=  1 , 1 , 1
Global Log Level= 0
CheckData=True
Encroach Param= -1, 0, 0, 0
BEGIN DESCRIPTION:
Multiple Run
END DESCRIPTION:

--- UNT 0048 IN LATR.f01 (steady flow) ---

Flow Title=Multiple
Number of Profiles=7
Profile Names=10-year,25-year,50-year,1pct_min,100-year,1pct_plu,500-year
River Rch & RM= UNT 1048 IN LATR,Reach-1,1572
     715    1027    1295    1197    1619    2189    2536
Boundary for River Rch & Prof#=UNT 1048 IN LATR,Reach-1,1
Up Type=0
Dn Type=3
Dn Slope=0.005
Boundary for River Rch & Prof#=UNT 1048 IN LATR,Reach-1,2
Up Type=0
Dn Type=3
Dn Slope=0.005
Boundary for River Rch & Prof#=UNT 1048 IN LATR,Reach-1,3
Up Type=0
Dn Type=3
Dn Slope=0.005
Boundary for River Rch & Prof#=UNT 1048 IN LATR,Reach-1,4
Up Type=0
Dn Type=3
Dn Slope=0.005
Boundary for River Rch & Prof#=UNT 1048 IN LATR,Reach-1,5
Up Type=0
Dn Type=3
Dn Slope=0.005
Boundary for River Rch & Prof#=UNT 1048 IN LATR,Reach-1,6
Up Type=0
Dn Type=3
Dn Slope=0.005
Boundary for River Rch & Prof#=UNT 1048 IN LATR,Reach-1,7
Up Type=0
Dn Type=3
Dn Slope=0.005

--- UNT 0048 IN LATR.g01 (geometry) ---

Geom Title=Existing Conditions

River Reach=UNT 1048 IN LATR,Reach-1
Reach XY= 30
      2886754.46     10094431.44      2886726.10     10094418.07
      2886685.57     10094388.66      2886635.05     10094341.78
      2886581.86     10094301.08      2886497.37     10094260.04
      2886466.47     10094251.71      2886428.62     10094252.33
      2886374.39     10094241.44      2886343.35     10094219.53
      2886308.64     10094178.73      2886276.07     10094091.06
      2886282.21     10094019.98      2886265.50     10093934.99
      2886246.18     10093894.61      2886191.44     10093838.81
      2886125.77     10093808.87      2886023.32     10093733.65
      2886003.16     10093725.25      2885982.13     10093724.02
      2885935.87     10093738.58      2885901.63     10093761.48
      2885869.57     10093792.44      2885824.21     10093855.64
      2885738.06     10093892.63      2885708.71     10093883.59
      2885655.07     10093842.95      2885623.93     10093809.08
      2885569.94     10093786.73      2885550.73     10093783.67

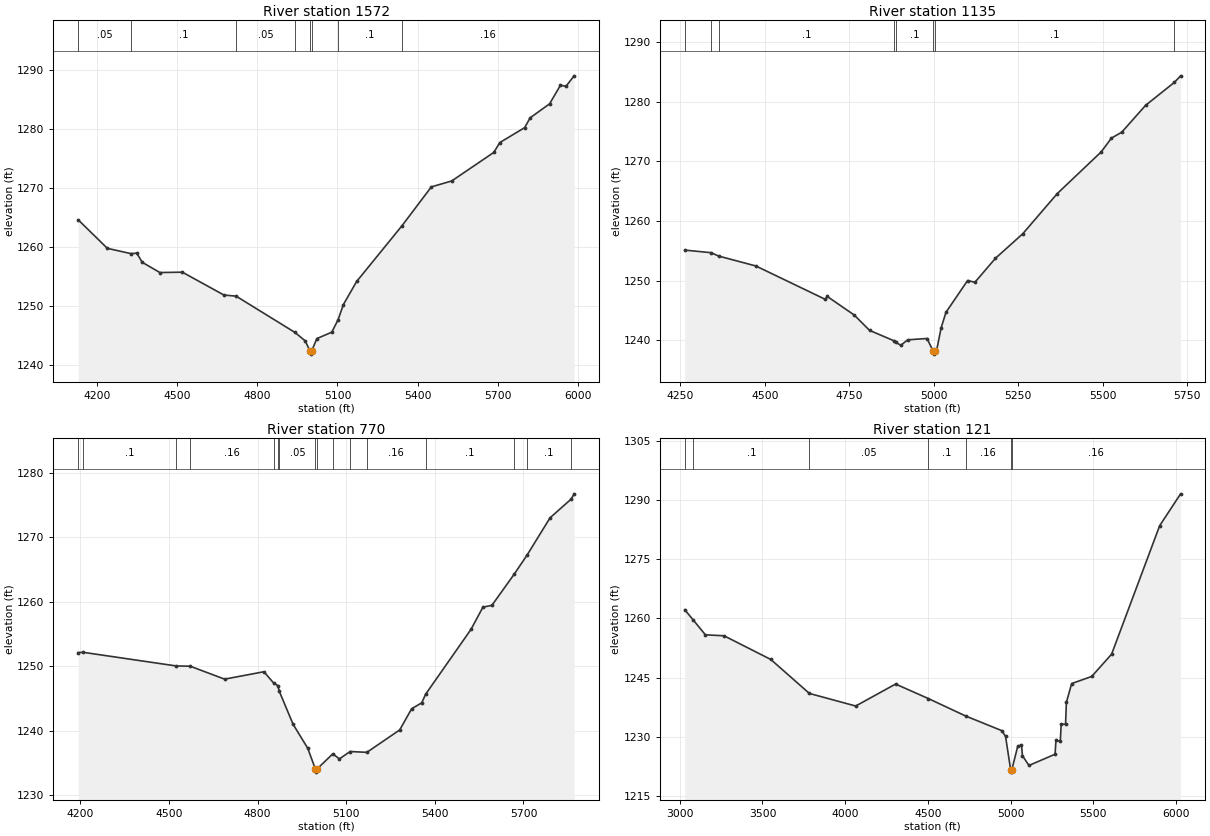
Type RM Length L Ch R = 1,1572,437,437,437
BEGIN DESCRIPTION:
UNT 1048 IN LATR 3.0
END DESCRIPTION:
XS GIS Cut Line= 4
      2887467.31     10094284.42      2886785.01     10094227.13
      2886410.01     10094706.30      2886269.39     10095253.15
#Sta/Elev= 30
  4128.6 1264.64  4237.8 1259.81  4325.5 1258.92  4348.2 1258.99  4368.3 1257.45
  4434.6 1255.71  4518.8 1255.77  4674.5 1251.90  4720.2 1251.71  4940.8 1245.56
  4979.2 1244.13  4997.0 1242.39  4999.8 1241.89  5003.0 1242.39  5022.6 1244.52
  5078.7 1245.61  5102.4 1247.74  5122.1 1250.29  5171.8 1254.20  5341.5 1263.63
  5451.6 1270.22  5527.9 1271.22  5685.7 1276.06  5708.2 1277.73  5801.1 1280.25
  5821.8 1281.92  5894.5 1284.28  5935.4 1287.44  5956.0 1287.25  5986.4 1289.03
#Mann=8,-1,0
  4128.6    0.05       0  4325.5     0.1       0  4720.2    0.05       0
  4940.8    0.16       0  4997.0    0.07       0  5003.0    0.16       0
  5102.4     0.1       0  5341.5    0.16       0
Bank Sta=4997,5003
Exp/Cntr=0.3,0.1

Type RM Length L Ch R = 1,1135,365,365,365
BEGIN DESCRIPTION:
UNT 1048 IN LATR 2.0
END DESCRIPTION:
XS GIS Cut Line= 4
      2886988.12     10094076.09      2886467.30     10094029.21
      2886180.84     10094274.01      2886102.72     10094836.47
#Sta/Elev= 30
  4263.2 1255.11  4341.1 1254.68  4363.6 1254.11  4473.7 1252.45  4679.7 1246.84
  4684.8 1247.35  4764.9 1244.22  4810.2 1241.65  4882.8 1239.90  4888.3 1239.65
  4902.5 1239.15  4923.3 1240.07  4980.4 1240.29  4998.3 1238.17  5001.0 1237.67
  5004.3 1238.17  5008.2 1238.18  5022.1 1242.10  5036.4 1244.68  5100.3 1250.01
  5122.0 1249.72  5182.8 1253.74  5263.6 1257.85  5365.8 1264.59  5495.8 1271.58
  5526.1 1273.89  5556.4 1274.87  5627.1 1279.38  5712.0 1283.22  5730.8 1284.33
#Mann=8,-1,0
  4263.2     0.1       0  4341.1    0.05       0  4363.6     0.1       0
  4882.8    0.05       0  4888.3     0.1       0  4998.3    0.07       0
  5004.3     0.1       0  5712.0    0.16       0
Bank Sta=4998.3,5004.3
Exp/Cntr=0.3,0.1

Type RM Length L Ch R = 1,770,649,649,649
BEGIN DESCRIPTION:
Mapping XS a1c4eb4f
END DESCRIPTION:
XS GIS Cut Line= 4
      2886943.03     10093944.15      2886289.64     10093757.46
      2886054.07     10093948.58      2885974.26     10094640.30
#Sta/Elev= 30
  4192.3 1252.10  4208.3 1252.15  4524.0 1250.03  4571.4 1249.99  4688.1 1247.98
  4821.1 1249.13  4854.9 1247.34  4868.0 1246.99  4873.2 1246.10  4919.9 1240.98
  4969.5 1237.26  4995.3 1234.05  4998.0 1233.55  5001.3 1234.05  5054.5 1236.39
  5076.6 1235.60  5113.2 1236.75  5169.7 1236.62  5281.0 1240.10  5321.3 1243.38
  5355.7 1244.31  5368.6 1245.63  5522.6 1255.72  5562.9 1259.16  5593.1 1259.43
  5668.7 1264.27  5712.1 1267.22  5790.3 1273.03  5862.4 1275.96  5871.5 1276.74
#Mann=16,-1,0
  4192.3    0.05       0  4208.3     0.1       0  4524.0    0.05       0
  4571.4    0.16       0  4854.9    0.05       0  4868.0    0.16       0
  4873.2    0.05       0  4995.3   0.035       0  5001.3    0.05       0
  5054.5     0.1       0  5113.2    0.05       0  5169.7    0.16       0
  5368.6     0.1       0  5668.7    0.16       0  5712.1     0.1       0
  5862.4    0.16       0
Bank Sta=4995.3,5001.3
Exp/Cntr=0.3,0.1

Type RM Length L Ch R = 1,121,0,0,0
BEGIN DESCRIPTION:
UNT 1048 IN LATR 1.0
END DESCRIPTION:
XS GIS Cut Line= 4
      2887373.58     10092977.12      2885738.13     10093664.63
      2885592.30     10093966.71      2885873.23     10094809.50
#Sta/Elev= 30
  3030.3 1262.19  3082.4 1259.55  3155.2 1255.83  3267.9 1255.59  3550.8 1249.58
  3783.8 1240.98  4063.8 1237.79  4305.0 1243.36  4503.7 1239.67  4727.7 1235.28
  4947.7 1231.54  4969.9 1230.08  5001.0 1221.54  5003.7 1221.04  5007.0 1221.54
  5043.6 1227.62  5066.2 1227.93  5071.8 1225.20  5111.4 1222.73  5269.2 1225.58
  5274.5 1229.11  5300.8 1228.83  5306.1 1233.19  5332.5 1233.17  5337.7 1238.73
  5369.4 1243.48  5490.6 1245.28  5611.0 1250.93  5901.7 1283.50  6028.2 1291.56
#Mann=7,-1,0
  3030.3    0.05       0  3082.4     0.1       0  3783.8    0.05       0
  4503.7     0.1       0  4727.7    0.16       0  5001.0    0.07       0
  5007.0    0.16       0
Bank Sta=5001,5007
Exp/Cntr=0.3,0.1

Chan Stop Cuts=-1