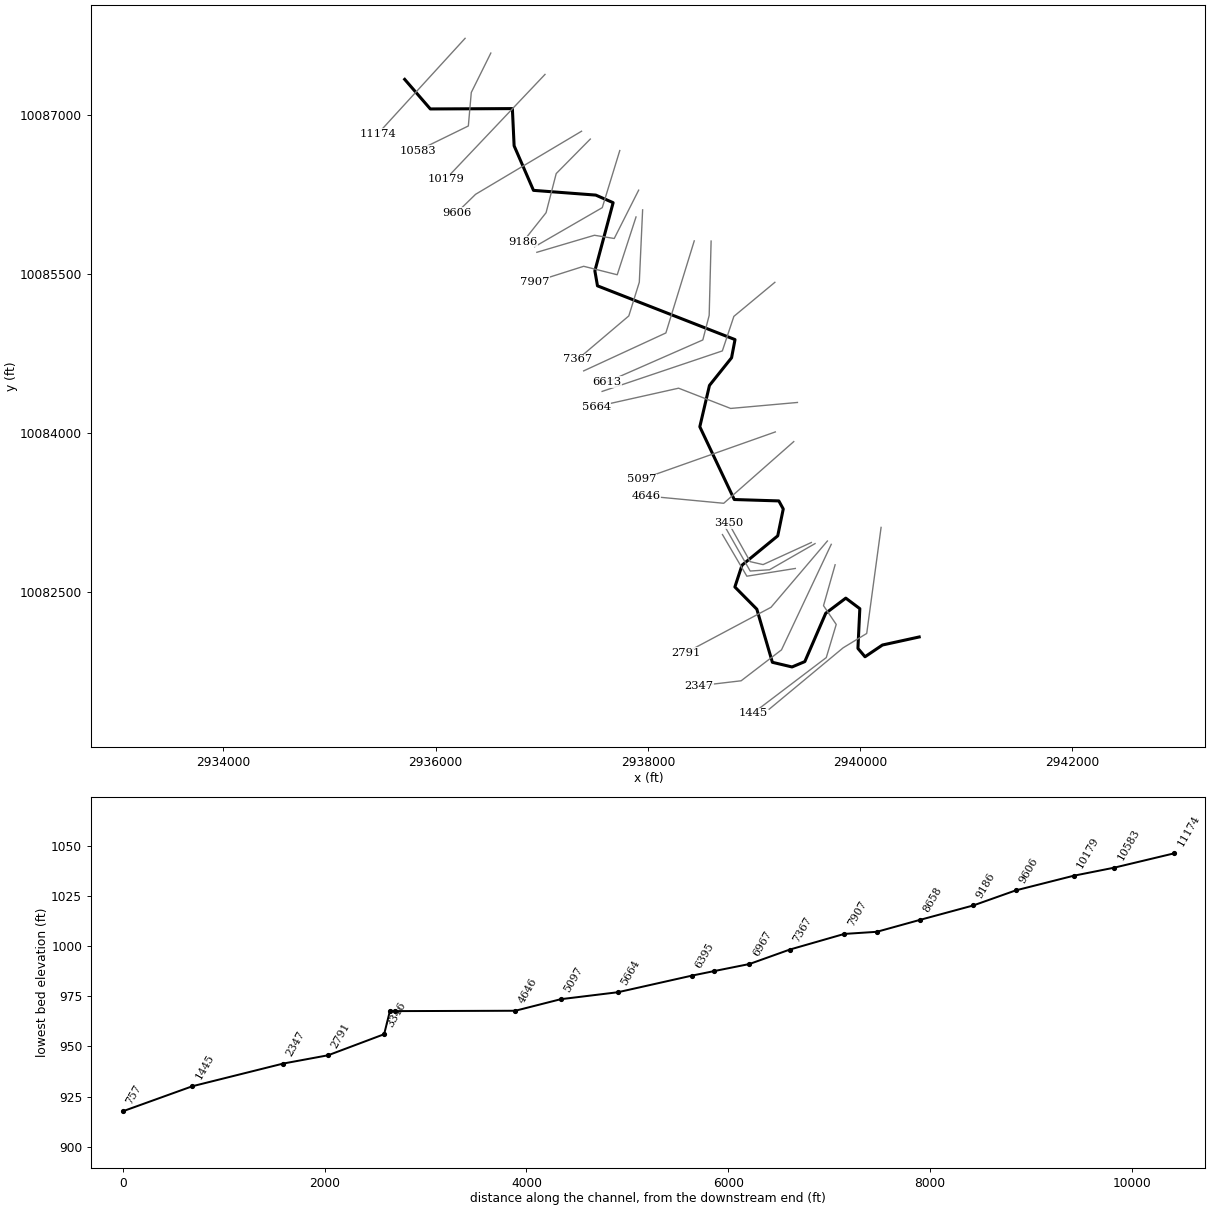
--- UNT 0050 IN LATR.prj (project) ---

Proj Title=UNT 1050 IN LATR Base Level Engineering
Current Plan=p01
Default Exp/Contr=0.3,0.1
English Units
Geom File=g01
Flow File=f01
Plan File=p01
BEGIN DESCRIPTION:
UNT 1050 IN LATR
END DESCRIPTION:

--- UNT 0050 IN LATR.p01 (plan) ---

Plan Title=Multiple Run
Short Identifier=Multiple
Geom File=g01
Flow File=f01
Subcritical Flow
K Sum by GR= 0
Std Step Tol= 0.01
Critical Tol= 0.01
Num of Std Step Trials= 20
Max Error Tol= 0.3
Flow Tol Ratio= 0.001
Split Flow NTrial= 30
Split Flow Tol= 0.02
Split Flow Ratio= 0.02
Log Output Level= 0
Friction Slope Method= 1
Unsteady Friction Slope Method= 2
Unsteady Bridges Friction Slope Method= 1
Parabolic Critical Depth
Global Vel Dist=  1 , 1 , 1
Global Log Level= 0
CheckData=True
Encroach Param= -1, 0, 0, 0
BEGIN DESCRIPTION:
Multiple Run
END DESCRIPTION:

--- UNT 0050 IN LATR.f01 (steady flow) ---

Flow Title=Multiple
Number of Profiles=7
Profile Names=10-year,25-year,50-year,1pct_min,100-year,1pct_plu,500-year
River Rch & RM= UNT 1050 IN LATR,Reach-1,11174
    1404    2079    2675    2516    3403    4602    5530
Boundary for River Rch & Prof#=UNT 1050 IN LATR,Reach-1,1
Up Type=0
Dn Type=3
Dn Slope=0.005
Boundary for River Rch & Prof#=UNT 1050 IN LATR,Reach-1,2
Up Type=0
Dn Type=3
Dn Slope=0.005
Boundary for River Rch & Prof#=UNT 1050 IN LATR,Reach-1,3
Up Type=0
Dn Type=3
Dn Slope=0.005
Boundary for River Rch & Prof#=UNT 1050 IN LATR,Reach-1,4
Up Type=0
Dn Type=3
Dn Slope=0.005
Boundary for River Rch & Prof#=UNT 1050 IN LATR,Reach-1,5
Up Type=0
Dn Type=3
Dn Slope=0.005
Boundary for River Rch & Prof#=UNT 1050 IN LATR,Reach-1,6
Up Type=0
Dn Type=3
Dn Slope=0.005
Boundary for River Rch & Prof#=UNT 1050 IN LATR,Reach-1,7
Up Type=0
Dn Type=3
Dn Slope=0.005

--- UNT 0050 IN LATR.g01 (geometry) ---

Geom Title=Existing Conditions

River Reach=UNT 1050 IN LATR,Reach-1
Reach XY= 30
      2935708.47     10087333.73      2935949.86     10087054.86
      2936723.05     10087057.99      2936739.54     10086707.30
      2936921.96     10086287.20      2937508.88     10086242.56
      2937672.44     10086171.03      2937500.36     10085527.87
      2937524.97     10085386.94      2938820.86     10084880.19
      2938788.32     10084708.79      2938580.08     10084448.07
      2938489.10     10084058.21      2938813.77     10083372.26
      2939233.62     10083359.04      2939275.35     10083283.04
      2939223.28     10083029.73      2938886.91     10082753.25
      2938819.48     10082547.66      2939026.29     10082338.37
      2939172.87     10081837.46      2939358.12     10081793.60
      2939478.45     10081844.14      2939675.68     10082300.16
      2939864.45     10082442.43      2939996.73     10082343.15
      2939978.87     10081968.53      2940045.66     10081889.66
      2940209.80     10082000.49      2940556.15     10082076.30

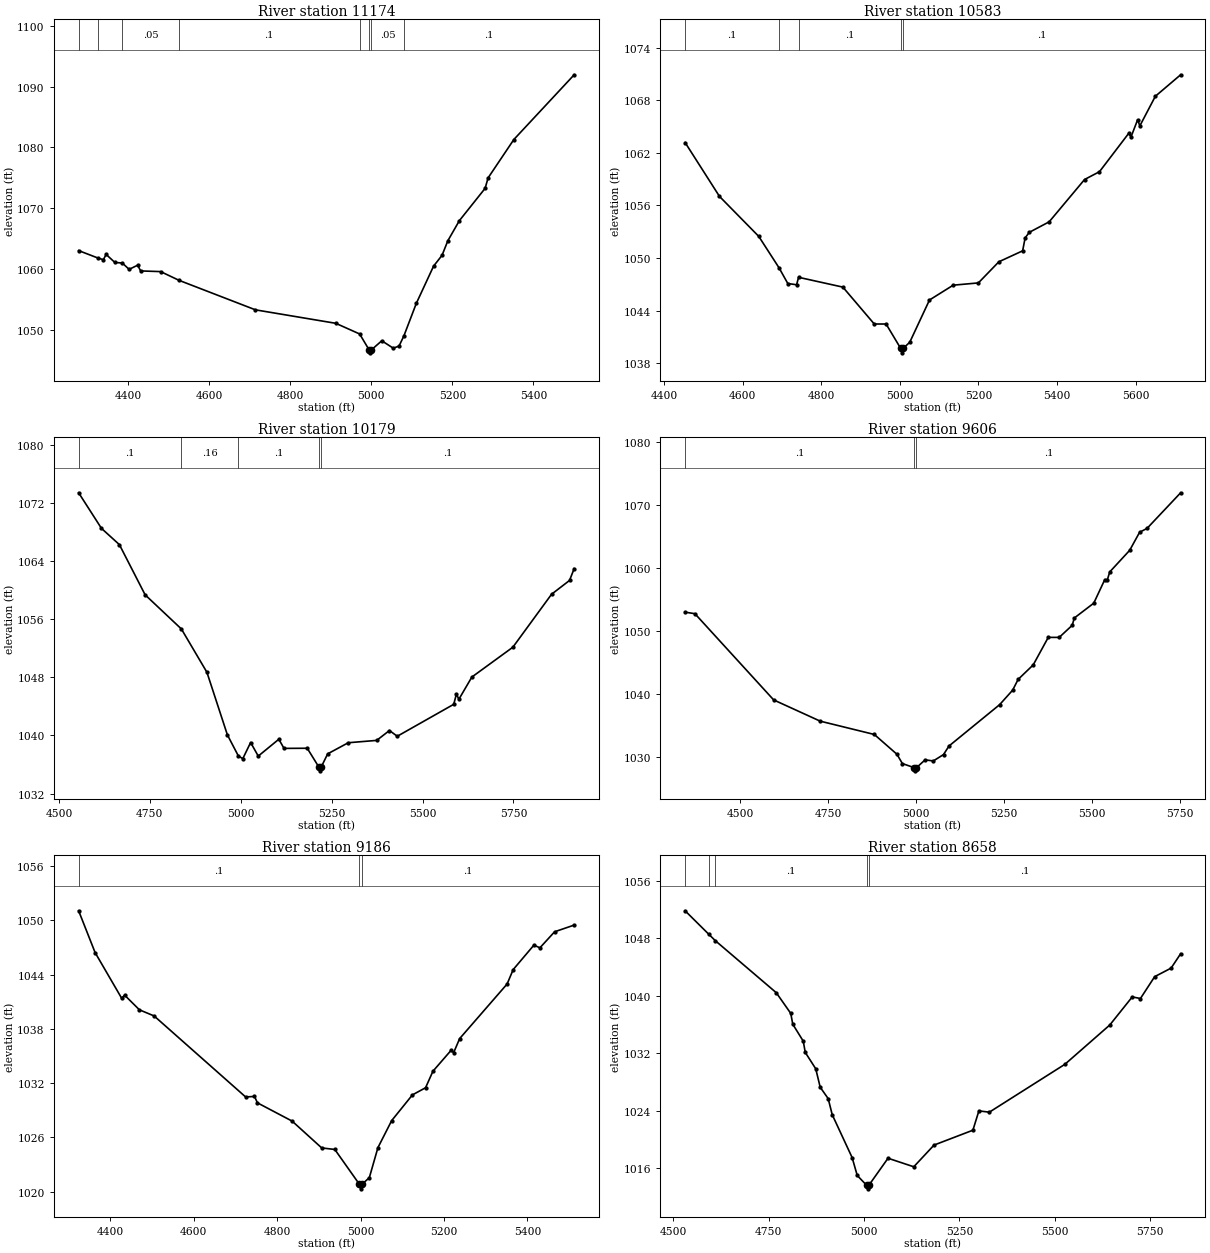
Type RM Length L Ch R = 1,11174,591,591,591
BEGIN DESCRIPTION:
UNT 1050 IN LATR 24.0
END DESCRIPTION:
XS GIS Cut Line= 2
      2936277.55     10087720.55      2935453.59     10086818.53
#Sta/Elev= 30
  4278.6 1063.07  4327.0 1061.83  4339.6 1061.58  4346.4 1062.44  4368.0 1061.12
  4386.2 1061.03  4403.1 1059.99  4424.1 1060.67  4431.5 1059.73  4480.8 1059.62
  4526.0 1058.19  4714.6 1053.34  4912.5 1051.13  4971.4 1049.38  4994.6 1046.78
  4997.4 1046.28  5000.6 1046.78  5026.0 1048.26  5054.4 1047.04  5068.6 1047.40
  5080.6 1049.08  5111.1 1054.40  5153.7 1060.52  5174.6 1062.30  5188.8 1064.68
  5217.2 1067.98  5280.7 1073.29  5288.1 1075.01  5351.6 1081.31  5500.3 1091.94
#Mann=8,-1,0
  4278.6    0.05       0  4327.0     0.1       0  4386.2    0.05       0
  4526.0     0.1       0  4971.4    0.05       0  4994.6   0.035       0
  5000.6    0.05       0  5080.6     0.1       0
Bank Sta=4994.6,5000.6
Exp/Cntr=0.3,0.1

Type RM Length L Ch R = 1,10583,404,404,404
BEGIN DESCRIPTION:
UNT 1050 IN LATR 23.0
END DESCRIPTION:
XS GIS Cut Line= 4
      2936520.02     10087581.68      2936335.98     10087210.14
      2936308.21     10086894.16      2935833.00     10086661.76
#Sta/Elev= 30
  4453.7 1063.17  4541.2 1057.02  4641.1 1052.46  4692.6 1048.88  4715.0 1047.08
  4737.4 1046.94  4742.4 1047.79  4855.1 1046.67  4935.0 1042.46  4965.1 1042.46
  5002.3 1039.67  5005.0 1039.17  5008.3 1039.67  5025.3 1040.38  5075.5 1045.20
  5135.8 1046.89  5199.9 1047.15  5252.0 1049.56  5312.5 1050.81  5318.8 1052.28
  5329.4 1052.92  5380.0 1054.12  5470.1 1058.95  5508.0 1059.84  5582.6 1064.23
  5588.2 1063.80  5605.1 1065.77  5610.7 1065.07  5650.2 1068.45  5714.5 1070.90
#Mann=5,-1,0
  4453.7     0.1       0  4692.6    0.05       0  4742.4     0.1       0
  5002.3    0.07       0  5008.3     0.1       0
Bank Sta=5002.3,5008.3
Exp/Cntr=0.3,0.1

Type RM Length L Ch R = 1,10179,573,573,573
BEGIN DESCRIPTION:
Mapping XS 51f3e1d9
END DESCRIPTION:
XS GIS Cut Line= 2
      2937030.44     10087380.29      2936093.18     10086390.96
#Sta/Elev= 30
  4554.2 1073.40  4617.0 1068.50  4666.3 1066.26  4737.1 1059.35  4836.8 1054.65
  4907.0 1048.69  4963.3 1040.07  4993.6 1037.16  5005.7 1036.80  5027.2 1039.02
  5048.2 1037.15  5104.8 1039.47  5119.0 1038.21  5182.9 1038.23  5215.1 1035.62
  5217.8 1035.12  5221.1 1035.62  5239.1 1037.46  5295.8 1038.99  5373.8 1039.31
  5409.0 1040.67  5430.5 1039.88  5585.8 1044.28  5593.1 1045.68  5600.0 1044.98
  5635.6 1048.03  5748.4 1052.14  5854.8 1059.43  5904.2 1061.33  5917.0 1062.96
#Mann=5,-1,0
  4554.2     0.1       0  4836.8    0.16       0  4993.6     0.1       0
  5215.1    0.07       0  5221.1     0.1       0
Bank Sta=5215.1,5221.1
Exp/Cntr=0.3,0.1

Type RM Length L Ch R = 1,9606,420,420,420
BEGIN DESCRIPTION:
UNT 1050 IN LATR 21.0
END DESCRIPTION:
XS GIS Cut Line= 3
      2937374.73     10086844.64      2936376.50     10086250.04
      2936199.70     10086077.56
#Sta/Elev= 30
  4343.7 1052.99  4371.6 1052.75  4595.5 1039.07  4727.9 1035.70  4881.7 1033.59
  4946.0 1030.45  4961.5 1028.97  4995.5 1028.32  4998.3 1027.82  5001.5 1028.32
  5026.1 1029.56  5049.4 1029.39  5078.4 1030.40  5094.0 1031.76  5238.0 1038.32
  5275.0 1040.62  5290.6 1042.33  5333.4 1044.62  5376.2 1048.99  5407.4 1048.99
  5444.4 1050.91  5450.2 1052.06  5505.6 1054.42  5536.9 1058.15  5544.1 1058.11
  5551.1 1059.38  5607.7 1062.80  5636.0 1065.67  5657.1 1066.28  5752.6 1071.93
#Mann=3,-1,0
  4343.7     0.1       0  4995.5    0.07       0  5001.5     0.1       0
Bank Sta=4995.5,5001.5
Exp/Cntr=0.3,0.1

Type RM Length L Ch R = 1,9186,528,528,528
BEGIN DESCRIPTION:
UNT 1050 IN LATR 20.0
END DESCRIPTION:
XS GIS Cut Line= 4
      2937457.23     10086770.88      2937136.04     10086445.36
      2937040.56     10086076.43      2936823.53     10085802.98
#Sta/Elev= 30
  4324.5 1051.04  4364.0 1046.42  4427.7 1041.37  4434.7 1041.72  4470.1 1040.10
  4505.4 1039.42  4724.7 1030.47  4745.9 1030.53  4753.0 1029.82  4836.2 1027.80
  4907.0 1024.84  4938.4 1024.67  4997.4 1020.82  5000.2 1020.32  5003.4 1020.82
  5021.1 1021.55  5041.7 1024.87  5074.7 1027.86  5124.4 1030.70  5155.9 1031.49
  5173.5 1033.31  5216.8 1035.61  5223.2 1035.37  5237.6 1036.92  5351.3 1042.95
  5365.8 1044.54  5415.4 1047.24  5429.9 1046.95  5465.1 1048.72  5512.0 1049.46
#Mann=3,-1,0
  4324.5     0.1       0  4997.4    0.07       0  5003.4     0.1       0
Bank Sta=4997.4,5003.4
Exp/Cntr=0.3,0.1

Type RM Length L Ch R = 1,8658,428,428,428
BEGIN DESCRIPTION:
UNT 1050 IN LATR 19.0
END DESCRIPTION:
XS GIS Cut Line= 3
      2937735.01     10086662.39      2937570.07     10086124.18
      2936932.76     10085755.66
#Sta/Elev= 30
  4530.7 1051.83  4592.1 1048.60  4610.1 1047.66  4769.7 1040.43  4807.7 1037.55
  4813.0 1036.04  4840.5 1033.68  4845.7 1032.12  4873.2 1029.84  4884.9 1027.27
  4905.8 1025.69  4916.4 1023.45  4968.6 1017.48  4982.0 1014.99  5006.5 1013.63
  5009.2 1013.13  5012.5 1013.63  5062.7 1017.39  5130.2 1016.20  5183.3 1019.22
  5285.2 1021.29  5300.9 1023.98  5328.3 1023.80  5526.3 1030.46  5644.0 1035.93
  5702.9 1039.84  5724.4 1039.62  5761.7 1042.66  5804.8 1043.85  5829.8 1045.85
#Mann=5,-1,0
  4530.7     0.1       0  4592.1    0.05       0  4610.1     0.1       0
  5006.5    0.07       0  5012.5     0.1       0
Bank Sta=5006.5,5012.5
Exp/Cntr=0.3,0.1

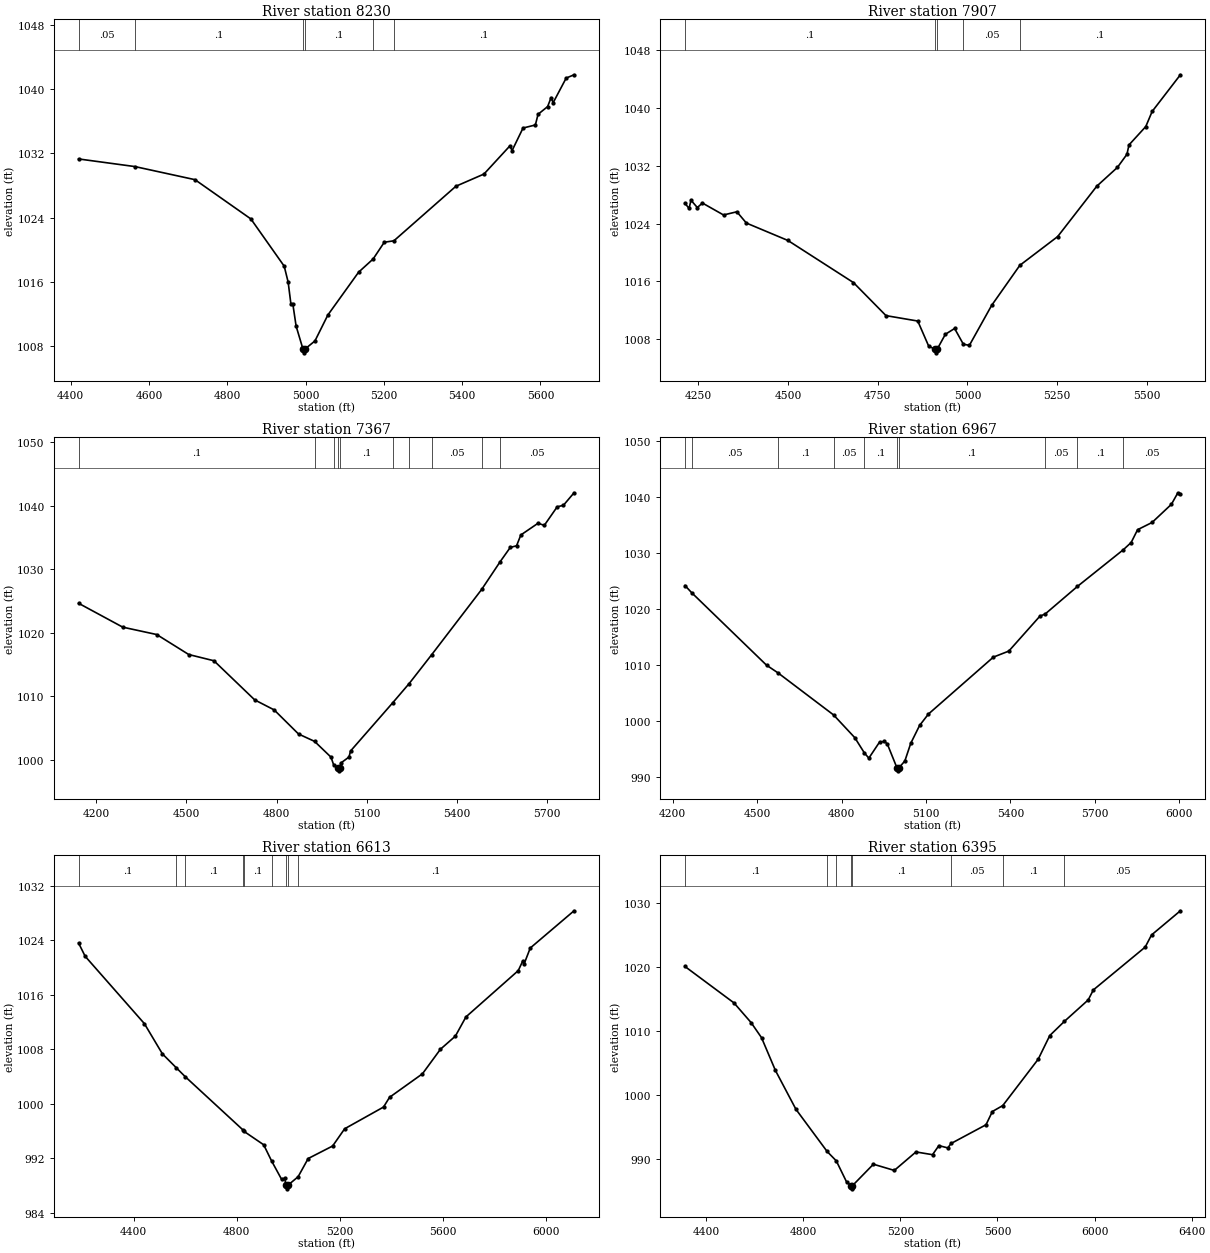
Type RM Length L Ch R = 1,8230,323,323,323
BEGIN DESCRIPTION:
UNT 1050 IN LATR 18.0
END DESCRIPTION:
XS GIS Cut Line= 4
      2937912.94     10086289.08      2937682.92     10085833.38
      2937496.29     10085863.76      2936953.71     10085703.16
#Sta/Elev= 30
  4420.4 1031.31  4564.3 1030.36  4717.6 1028.73  4860.4 1023.84  4945.5 1017.96
  4955.6 1015.97  4962.5 1013.29  4967.5 1013.26  4975.9 1010.50  4993.2 1007.67
  4995.9 1007.17  4999.2 1007.67  5024.0 1008.65  5057.0 1011.88  5135.5 1017.21
  5172.7 1018.86  5201.1 1020.94  5225.7 1021.12  5384.0 1027.91  5455.7 1029.43
  5522.2 1032.95  5527.4 1032.34  5555.5 1035.16  5587.0 1035.54  5593.9 1036.87
  5618.3 1037.83  5627.2 1038.95  5632.4 1038.31  5665.7 1041.38  5685.8 1041.79
#Mann=6,-1,0
  4420.4    0.05       0  4564.3     0.1       0  4993.2    0.07       0
  4999.2     0.1       0  5172.7    0.05       0  5225.7     0.1       0
Bank Sta=4993.2,4999.2
Exp/Cntr=0.3,0.1

Type RM Length L Ch R = 1,7907,540,540,540
BEGIN DESCRIPTION:
Mapping XS 44e85978
END DESCRIPTION:
XS GIS Cut Line= 4
      2937888.06     10086036.50      2937710.98     10085491.39
      2937395.01     10085571.25      2936936.71     10085425.42
#Sta/Elev= 30
  4213.3 1026.79  4224.8 1026.10  4230.1 1027.23  4247.7 1026.22  4262.0 1026.84
  4320.7 1025.19  4357.9 1025.63  4384.4 1024.07  4500.1 1021.66  4682.7 1015.83
  4773.3 1011.26  4861.8 1010.51  4892.2 1007.04  4909.8 1006.61  4912.6 1006.11
  4915.8 1006.61  4938.7 1008.68  4964.4 1009.48  4988.8 1007.30  5005.6 1007.15
  5067.5 1012.67  5146.1 1018.22  5251.5 1022.20  5360.6 1029.18  5417.9 1031.77
  5444.5 1033.59  5450.1 1034.88  5497.0 1037.43  5514.6 1039.51  5593.3 1044.59
#Mann=5,-1,0
  4213.3     0.1       0  4909.8   0.035       0  4915.8     0.1       0
  4988.8    0.05       0  5146.1     0.1       0
Bank Sta=4909.8,4915.8
Exp/Cntr=0.3,0.1

Type RM Length L Ch R = 1,7367,400,400,400
BEGIN DESCRIPTION:
UNT 1050 IN LATR 16.0
END DESCRIPTION:
XS GIS Cut Line= 4
      2937950.28     10086103.29      2937919.03     10085421.05
      2937820.07     10085103.34      2937338.30     10084694.48
#Sta/Elev= 30
  4141.7 1024.64  4288.5 1020.89  4401.5 1019.73  4507.9 1016.59  4591.7 1015.61
  4727.3 1009.46  4791.9 1007.89  4873.0 1004.10  4926.4 1002.94  4981.0 1000.46
  4989.9  999.24  5005.3  998.81  5008.1  998.31  5011.3  998.81  5013.6  999.53
  5040.8 1000.48  5046.1 1001.43  5185.6 1008.97  5241.0 1012.03  5316.3 1016.59
  5481.9 1026.81  5543.9 1031.20  5577.2 1033.42  5598.1 1033.68  5612.4 1035.38
  5669.5 1037.22  5690.4 1036.89  5733.2 1039.80  5754.1 1040.05  5789.3 1042.01
#Mann=10,-1,0
  4141.7     0.1       0  4926.4    0.05       0  4989.9     0.1       0
  5005.3    0.07       0  5011.3     0.1       0  5185.6    0.05       0
  5241.0     0.1       0  5316.3    0.05       0  5481.9     0.1       0
  5543.9    0.05       0
Bank Sta=5005.3,5011.3
Exp/Cntr=0.3,0.1

Type RM Length L Ch R = 1,6967,354,354,354
BEGIN DESCRIPTION:
Mapping XS 2378817d
END DESCRIPTION:
XS GIS Cut Line= 3
      2938436.68     10085810.83      2938169.32     10084942.77
      2937395.02     10084585.14
#Sta/Elev= 30
  4243.3 1024.22  4267.8 1022.91  4533.2 1009.99  4574.6 1008.59  4771.7 1001.09
  4847.2  997.02  4881.4  994.28  4897.0  993.37  4934.9  996.23  4951.8  996.35
  4962.3  995.95  4997.2  991.60  5000.0  991.10  5003.2  991.60  5025.0  992.86
  5046.0  996.02  5077.4  999.21  5108.8 1001.25  5339.8 1011.43  5394.5 1012.50
  5505.0 1018.74  5524.0 1019.14  5638.7 1024.07  5801.9 1030.63  5829.5 1031.91
  5852.4 1034.20  5903.8 1035.49  5972.6 1038.74  5995.6 1040.80  6004.5 1040.51
#Mann=10,-1,0
  4243.3     0.1       0  4267.8    0.05       0  4574.6     0.1       0
  4771.7    0.05       0  4881.4     0.1       0  4997.2    0.07       0
  5003.2     0.1       0  5524.0    0.05       0  5638.7     0.1       0
  5801.9    0.05       0
Bank Sta=4997.2,5003.2
Exp/Cntr=0.3,0.1

Type RM Length L Ch R = 1,6613,218,218,218
BEGIN DESCRIPTION:
UNT 1050 IN LATR 15.0
END DESCRIPTION:
XS GIS Cut Line= 4
      2938595.59     10085809.05      2938577.36     10085108.55
      2938517.47     10084876.78      2937616.41     10084480.94
#Sta/Elev= 30
  4186.1 1023.61  4211.4 1021.68  4441.5 1011.79  4511.5 1007.35  4565.9 1005.29
  4599.8 1004.01  4826.1  996.12  4829.2  995.95  4904.9  994.00  4935.4  991.64
  4974.4  988.93  4986.1  989.07  4992.1  988.03  4994.8  987.53  4998.1  988.03
  5038.7  989.31  5077.7  991.98  5172.7  993.82  5219.4  996.35  5370.4  999.54
  5393.8 1000.97  5521.5 1004.42  5591.5 1008.03  5649.4 1009.95  5690.4 1012.77
  5893.6 1019.57  5911.5 1021.01  5917.0 1020.61  5940.3 1022.89  6110.4 1028.36
#Mann=9,-1,0
  4186.1     0.1       0  4565.9    0.05       0  4599.8     0.1       0
  4826.1    0.05       0  4829.2     0.1       0  4935.4    0.05       0
  4992.1   0.035       0  4998.1    0.05       0  5038.7     0.1       0
Bank Sta=4992.1,4998.1
Exp/Cntr=0.3,0.1

Type RM Length L Ch R = 1,6395,731,731,731
BEGIN DESCRIPTION:
UNT 1050 IN LATR 14.0
END DESCRIPTION:
XS GIS Cut Line= 4
      2939196.25     10085420.15      2938810.00     10085099.00
      2938701.50     10084773.48      2937568.70     10084391.54
#Sta/Elev= 30
  4312.5 1020.06  4514.6 1014.36  4584.9 1011.29  4627.9 1008.93  4685.2 1003.80
  4769.8  997.72  4898.2  991.13  4936.0  989.66  4978.5  986.35  4996.6  985.79
  4999.3  985.29  5002.6  985.79  5088.8  989.14  5174.9  988.17  5264.1  991.06
  5332.3  990.63  5358.5  992.05  5395.3  991.69  5408.7  992.38  5552.7  995.31
  5578.9  997.38  5621.7  998.31  5767.7 1005.56  5815.4 1009.26  5875.7 1011.48
  5973.7 1014.83  5994.8 1016.39  6208.4 1023.09  6234.6 1024.99  6353.4 1028.77
#Mann=8,-1,0
  4312.5     0.1       0  4898.2    0.05       0  4936.0     0.1       0
  4996.6    0.07       0  5002.6     0.1       0  5408.7    0.05       0
  5621.7     0.1       0  5875.7    0.05       0
Bank Sta=4996.6,5002.6
Exp/Cntr=0.3,0.1

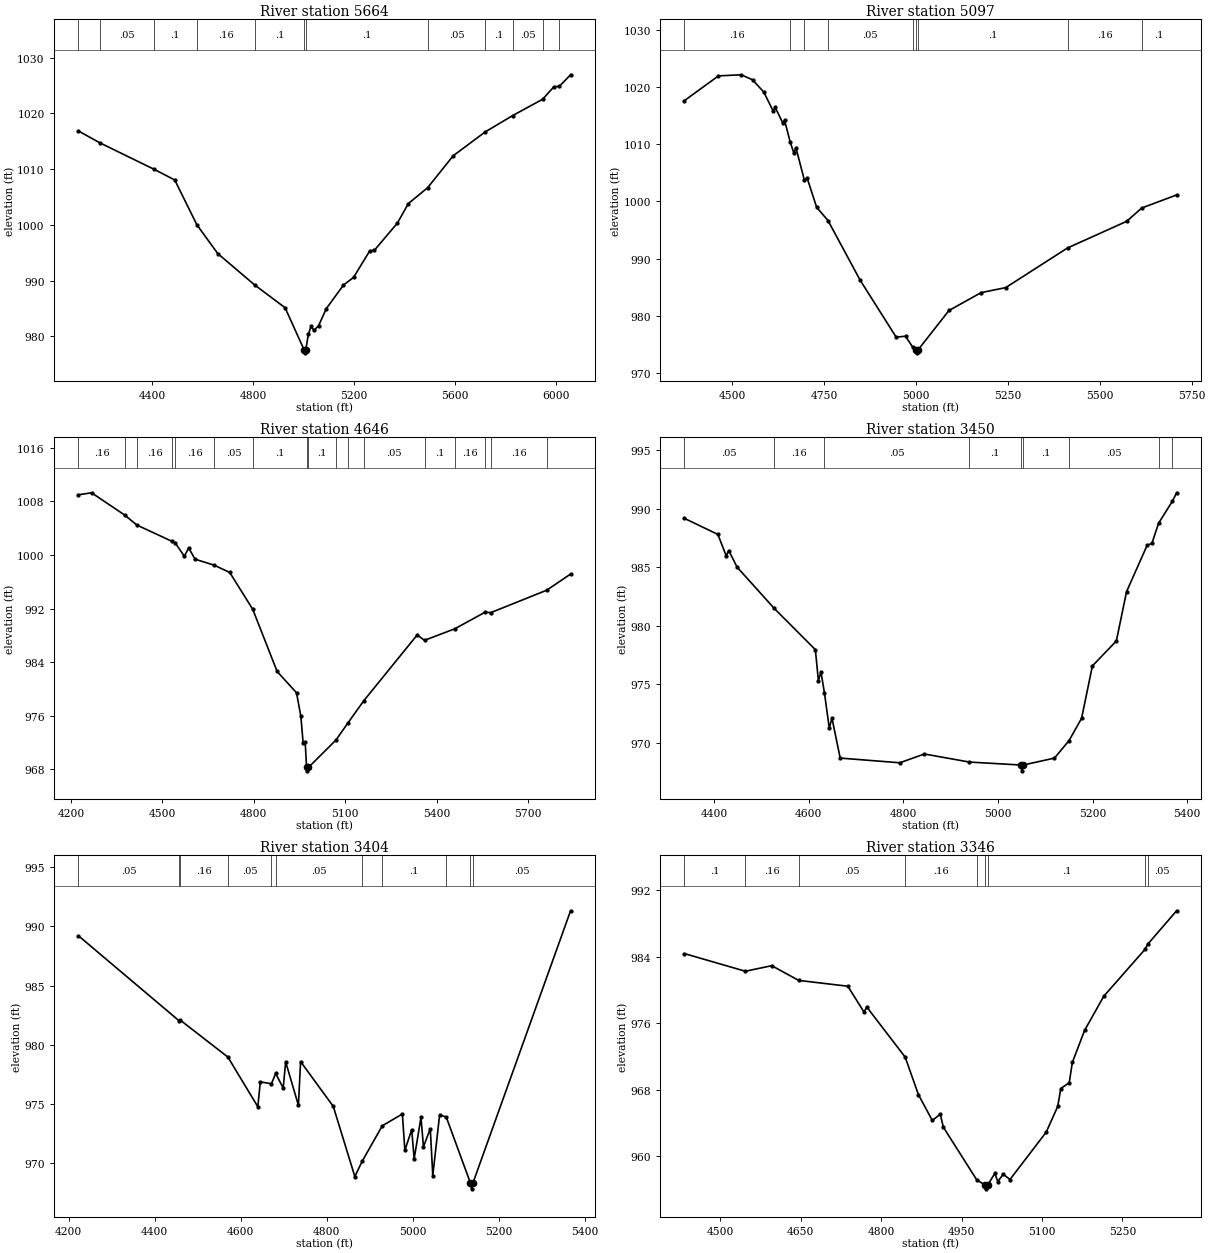
Type RM Length L Ch R = 1,5664,567,567,567
BEGIN DESCRIPTION:
UNT 1050 IN LATR 12.0
END DESCRIPTION:
XS GIS Cut Line= 4
      2939408.92     10084287.37      2938779.62     10084230.95
      2938289.17     10084421.92      2937513.84     10084248.66
#Sta/Elev= 30
  4106.9 1016.83  4191.4 1014.71  4405.0 1010.00  4488.9 1008.04  4577.0  999.98
  4659.6  994.84  4805.4  989.23  4926.7  985.12  5002.6  977.53  5005.3  977.03
  5008.6  977.53  5019.0  980.32  5029.7  981.79  5040.8  981.05  5059.9  981.91
  5089.8  984.93  5158.5  989.20  5198.6  990.57  5262.7  995.33  5280.4  995.39
  5372.4 1000.31  5415.8 1003.81  5491.9 1006.63  5593.7 1012.38  5721.0 1016.67
  5830.1 1019.60  5948.6 1022.52  5993.3 1024.76  6015.1 1024.84  6059.5 1026.91
#Mann=12,-1,0
  4106.9     0.1       0  4191.4    0.05       0  4405.0     0.1       0
  4577.0    0.16       0  4805.4     0.1       0  5002.6    0.07       0
  5008.6     0.1       0  5491.9    0.05       0  5721.0     0.1       0
  5830.1    0.05       0  5948.6     0.1       0  6015.1    0.05       0
Bank Sta=5002.6,5008.6
Exp/Cntr=0.3,0.1

Type RM Length L Ch R = 1,5097,451,451,451
BEGIN DESCRIPTION:
UNT 1050 IN LATR 11.0
END DESCRIPTION:
XS GIS Cut Line= 2
      2939200.62     10084009.59      2937937.61     10083562.54
#Sta/Elev= 30
  4369.3 1017.63  4461.8 1021.95  4523.6 1022.14  4554.5 1021.27  4585.4 1019.10
  4610.9 1015.78  4616.3 1016.44  4636.5 1013.77  4641.8 1014.20  4657.0 1010.39
  4667.4 1008.41  4672.7 1009.40  4695.4 1003.80  4703.6 1004.02  4729.2  998.97
  4760.1  996.66  4847.5  986.25  4945.5  976.30  4971.1  976.45  4990.3  974.57
  4999.0  974.05  5001.8  973.55  5005.0  974.05  5089.4  980.95  5176.8  984.07
  5243.9  984.95  5412.2  991.88  5573.1  996.53  5614.2  998.86  5709.1 1001.14
#Mann=9,-1,0
  4369.3    0.16       0  4657.0    0.05       0  4695.4    0.16       0
  4760.1    0.05       0  4990.3     0.1       0  4999.0    0.07       0
  5005.0     0.1       0  5412.2    0.16       0  5614.2     0.1       0
Bank Sta=4999,5005
Exp/Cntr=0.3,0.1

Type RM Length L Ch R = 1,4646,1196,1196,1196
BEGIN DESCRIPTION:
UNT 1050 IN LATR 10.0
END DESCRIPTION:
XS GIS Cut Line= 3
      2939374.24     10083918.45      2938714.52     10083336.85
      2937982.28     10083406.17
#Sta/Elev= 30
  4224.4 1008.98  4267.4 1009.28  4376.3 1005.95  4415.8 1004.47  4532.5 1002.01
  4542.6 1001.75  4571.9  999.80  4586.1 1001.05  4607.0  999.37  4669.4  998.48
  4720.8  997.39  4796.2  991.90  4876.4  982.61  4940.0  979.43  4954.2  975.93
  4961.8  971.91  4968.5  972.05  4973.0  968.28  4975.8  967.78  4979.0  968.28
  5069.3  972.37  5108.8  974.93  5160.9  978.25  5336.0  988.06  5360.0  987.26
  5459.5  988.98  5559.0  991.46  5577.5  991.39  5761.2  994.74  5839.4  997.15
#Mann=17,-1,0
  4224.4    0.16       0  4376.3     0.1       0  4415.8    0.16       0
  4532.5     0.1       0  4542.6    0.16       0  4669.4    0.05       0
  4796.2     0.1       0  4973.0    0.07       0  4979.0     0.1       0
  5069.3    0.16       0  5108.8     0.1       0  5160.9    0.05       0
  5360.0     0.1       0  5459.5    0.16       0  5559.0     0.1       0
  5577.5    0.16       0  5761.2     0.1       0
Bank Sta=4973,4979
Exp/Cntr=0.3,0.1

Type RM Length L Ch R = 1,3450,46,46,46
BEGIN DESCRIPTION:
UNT 1050 IN LATR 9.0
END DESCRIPTION:
XS GIS Cut Line= 4
      2939540.01     10082967.04      2939085.18     10082758.72
      2938963.65     10082786.50      2938760.70     10083149.03
#Sta/Elev= 30
  4337.3  989.18  4407.9  987.81  4425.4  985.99  4430.9  986.43  4448.4  985.02
  4526.7  981.50  4614.0  977.96  4620.4  975.31  4625.9  976.05  4633.2  974.26
  4643.5  971.23  4649.0  972.12  4666.5  968.69  4792.5  968.29  4844.5  969.04
  4939.7  968.35  5047.7  968.10  5050.5  967.60  5053.7  968.10  5119.5  968.69
  5150.4  970.19  5176.8  972.09  5199.7  976.57  5250.3  978.70  5271.9  982.92
  5315.3  986.87  5325.6  987.05  5339.6  988.77  5369.0  990.66  5377.7  991.37
#Mann=9,-1,0
  4337.3    0.05       0  4526.7    0.16       0  4633.2    0.05       0
  4939.7     0.1       0  5047.7    0.07       0  5053.7     0.1       0
  5150.4    0.05       0  5339.6    0.16       0  5369.0     0.1       0
Bank Sta=5047.7,5053.7
Exp/Cntr=0.3,0.1

Type RM Length L Ch R = 1,3404,58,58,58
BEGIN DESCRIPTION:
UNT 1050 IN LATR 8.0
END DESCRIPTION:
XS GIS Cut Line= 4
      2939574.76     10082956.64      2939145.94     10082710.11
      2938963.65     10082697.96      2938733.10     10083103.59
#Sta/Elev= 30
  4223.1  989.21  4457.8  982.01  4459.4  982.10  4570.5  978.97  4640.0  974.78
  4645.8  976.88  4671.6  976.72  4681.6  977.59  4699.0  976.35  4704.7  978.57
  4734.4  974.90  4739.4  978.59  4815.4  974.81  4865.5  968.89  4882.9  970.20
  4929.3  973.17  4976.0  974.17  4981.8  971.10  4997.7  972.84  5003.4  970.38
  5019.3  973.89  5025.0  971.40  5040.9  972.92  5046.7  968.97  5062.5  974.07
  5077.9  973.92  5134.1  968.35  5136.9  967.85  5140.1  968.35  5367.0  991.32
#Mann=11,-1,0
  4223.1    0.05       0  4457.8     0.1       0  4459.4    0.16       0
  4570.5    0.05       0  4671.6    0.16       0  4681.6    0.05       0
  4882.9    0.16       0  4929.3     0.1       0  5077.9    0.05       0
  5134.1    0.07       0  5140.1    0.05       0
Bank Sta=5134.1,5140.1
Exp/Cntr=0.3,0.1

Type RM Length L Ch R = 1,3346,555,555,555
BEGIN DESCRIPTION:
UNT 1050 IN LATR 7.0
END DESCRIPTION:
XS GIS Cut Line= 3
      2939389.03     10082722.27      2938932.40     10082649.35
      2938702.50     10083041.74
#Sta/Elev= 30
  4433.7  984.36  4547.2  982.24  4596.3  982.91  4646.5  981.14  4738.1  980.44
  4768.3  977.33  4773.4  977.94  4845.0  971.92  4869.7  967.41  4895.6  964.30
  4910.4  965.05  4916.2  963.49  4978.7  957.13  4993.3  956.58  4996.1  956.08
  4999.3  956.58  5012.0  957.93  5017.8  956.96  5027.7  957.84  5040.3  957.20
  5107.8  962.89  5129.3  965.98  5135.1  968.14  5150.8  968.84  5156.6  971.28
  5179.4  975.13  5215.2  979.24  5292.0  984.87  5297.3  985.51  5350.9  989.51
#Mann=9,-1,0
  4433.7     0.1       0  4547.2    0.16       0  4646.5    0.05       0
  4845.0    0.16       0  4978.7     0.1       0  4993.3   0.035       0
  4999.3     0.1       0  5292.0     0.1       0  5297.3    0.05       0
Bank Sta=4993.3,4999.3
Exp/Cntr=0.3,0.1

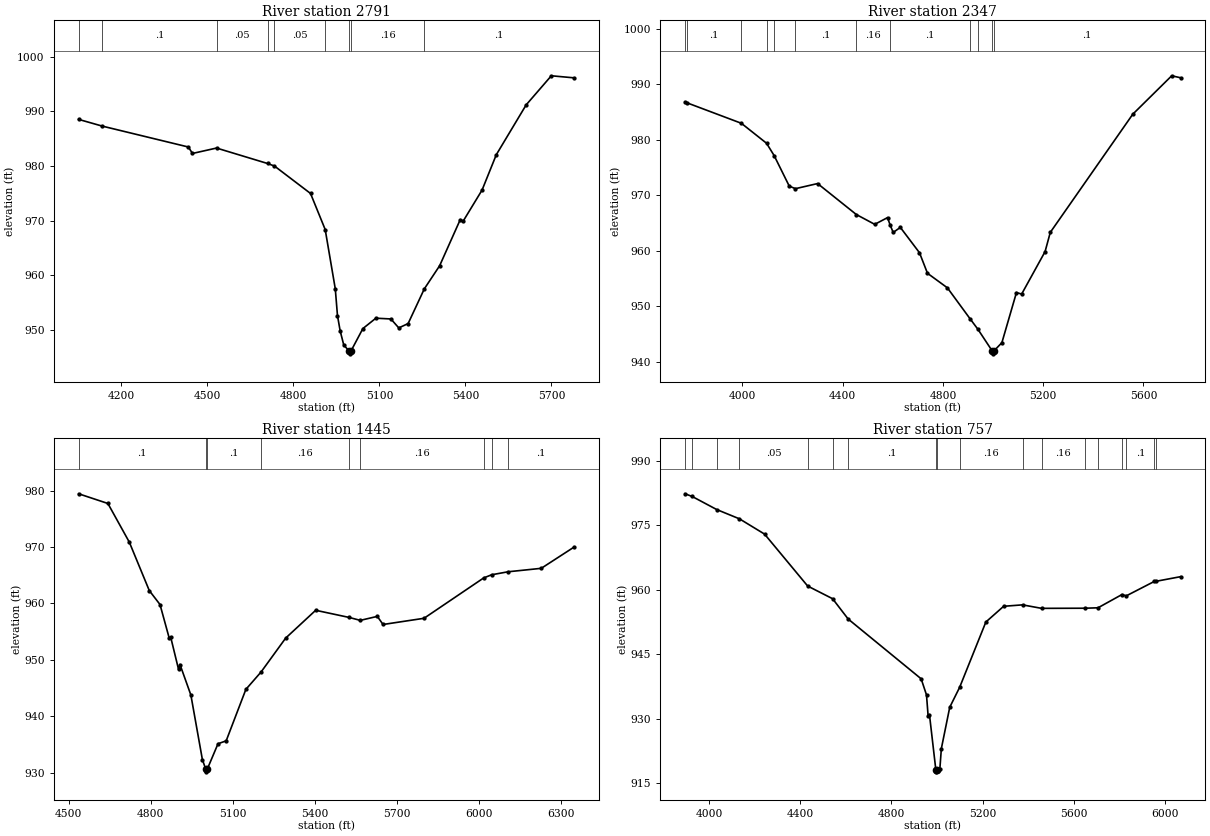
Type RM Length L Ch R = 1,2791,444,444,444
BEGIN DESCRIPTION:
UNT 1050 IN LATR 6.0
END DESCRIPTION:
XS GIS Cut Line= 3
      2939691.08     10082980.95      2939159.83     10082355.95
      2938357.73     10081928.85
#Sta/Elev= 30
  4050.5  988.53  4132.9  987.30  4433.4  983.47  4447.7  982.29  4531.7  983.28
  4709.7  980.45  4733.9  979.98  4859.6  974.96  4910.8  968.35  4946.0  957.49
  4953.6  952.60  4963.0  949.79  4975.6  947.19  4994.6  946.08  4997.3  945.58
  5000.6  946.08  5042.3  950.21  5087.6  952.11  5140.0  951.97  5167.6  950.33
  5200.2  951.13  5256.6  957.48  5310.1  961.72  5382.1  970.18  5392.3  969.90
  5458.2  975.59  5507.8  982.06  5612.0  991.19  5699.8  996.52  5779.5  996.14
#Mann=9,-1,0
  4050.5    0.05       0  4132.9     0.1       0  4531.7    0.05       0
  4709.7     0.1       0  4733.9    0.05       0  4910.8    0.16       0
  4994.6    0.07       0  5000.6    0.16       0  5256.6     0.1       0
Bank Sta=4994.6,5000.6
Exp/Cntr=0.3,0.1

Type RM Length L Ch R = 1,2347,902,902,902
BEGIN DESCRIPTION:
UNT 1050 IN LATR 5.0
END DESCRIPTION:
XS GIS Cut Line= 4
      2939727.55     10082949.72      2939258.79     10081954.90
      2938878.58     10081663.24      2938483.07     10081616.40
#Sta/Elev= 30
  3771.3  986.73  3777.8  986.65  3995.7  982.95  4096.2  979.36  4126.4  977.15
  4186.9  971.64  4211.6  971.18  4300.0  972.10  4454.4  966.53  4527.9  964.76
  4579.0  965.97  4589.7  964.60  4601.7  963.30  4630.1  964.21  4706.5  959.65
  4738.4  955.95  4817.9  953.33  4907.5  947.81  4939.8  945.86  4997.0  941.95
  4999.7  941.45  5003.0  941.95  5035.3  943.46  5093.4  952.48  5114.2  952.21
  5207.6  959.85  5228.4  963.31  5557.7  984.59  5712.9  991.50  5748.5  991.14
#Mann=12,-1,0
  3771.3    0.05       0  3777.8     0.1       0  3995.7    0.05       0
  4096.2     0.1       0  4126.4    0.05       0  4211.6     0.1       0
  4454.4    0.16       0  4589.7     0.1       0  4907.5    0.16       0
  4939.8     0.1       0  4997.0    0.07       0  5003.0     0.1       0
Bank Sta=4997,5003
Exp/Cntr=0.3,0.1

Type RM Length L Ch R = 1,1445,688,688,688
BEGIN DESCRIPTION:
UNT 1050 IN LATR 3.0
END DESCRIPTION:
XS GIS Cut Line= 5
      2939763.99     10082756.95      2939654.62     10082371.57
      2939774.41     10082194.49      2939680.66     10081881.99
      2938987.92     10081355.92
#Sta/Elev= 30
  4536.8  979.43  4643.7  977.71  4722.0  970.85  4795.0  962.26  4834.1  959.79
  4868.0  953.79  4873.2  954.00  4901.9  948.28  4907.1  949.15  4946.9  943.74
  4989.0  932.28  5001.0  930.62  5003.7  930.12  5007.0  930.62  5046.0  935.10
  5075.9  935.62  5147.8  944.74  5203.4  947.83  5293.3  953.84  5402.9  958.77
  5526.2  957.49  5565.8  956.98  5628.1  957.69  5649.0  956.25  5798.7  957.35
  6016.8  964.51  6045.9  965.07  6106.1  965.60  6227.1  966.21  6347.3  969.99
#Mann=9,-1,0
  4536.8     0.1       0  5001.0    0.07       0  5007.0     0.1       0
  5203.4    0.16       0  5526.2     0.1       0  5565.8    0.16       0
  6016.8     0.1       0  6045.9    0.16       0  6106.1     0.1       0
Bank Sta=5001,5007
Exp/Cntr=0.3,0.1

Type RM Length L Ch R = 1,757,0,0,0
BEGIN DESCRIPTION:
UNT 1050 IN LATR 1.0
END DESCRIPTION:
XS GIS Cut Line= 4
      2940197.10     10083109.48      2940061.68     10082109.44
      2939839.46     10081974.02      2939142.52     10081394.98
#Sta/Elev= 30
  3893.9  982.33  3925.1  981.70  4032.8  978.66  4132.6  976.50  4242.8  972.95
  4432.0  960.87  4541.4  957.92  4609.9  953.19  4930.2  939.29  4953.7  935.54
  4960.8  930.65  4966.7  930.96  4994.6  918.15  4997.3  917.65  5000.6  918.15
  5012.2  918.23  5018.9  923.06  5055.7  932.67  5099.2  937.31  5214.3  952.50
  5292.4  956.16  5375.3  956.49  5458.9  955.68  5649.7  955.71  5706.7  955.81
  5811.8  958.89  5830.6  958.58  5954.5  961.96  5963.1  961.99  6069.4  963.05
#Mann=18,-1,0
  3893.9     0.1       0  3925.1    0.05       0  4032.8     0.1       0
  4132.6    0.05       0  4432.0     0.1       0  4541.4    0.16       0
  4609.9     0.1       0  4994.6    0.07       0  5000.6     0.1       0
  5099.2    0.16       0  5375.3     0.1       0  5458.9    0.16       0
  5649.7     0.1       0  5706.7    0.16       0  5811.8    0.05       0
  5830.6     0.1       0  5954.5    0.16       0  5963.1     0.1       0
Bank Sta=4994.6,5000.6
Exp/Cntr=0.3,0.1

Chan Stop Cuts=-1