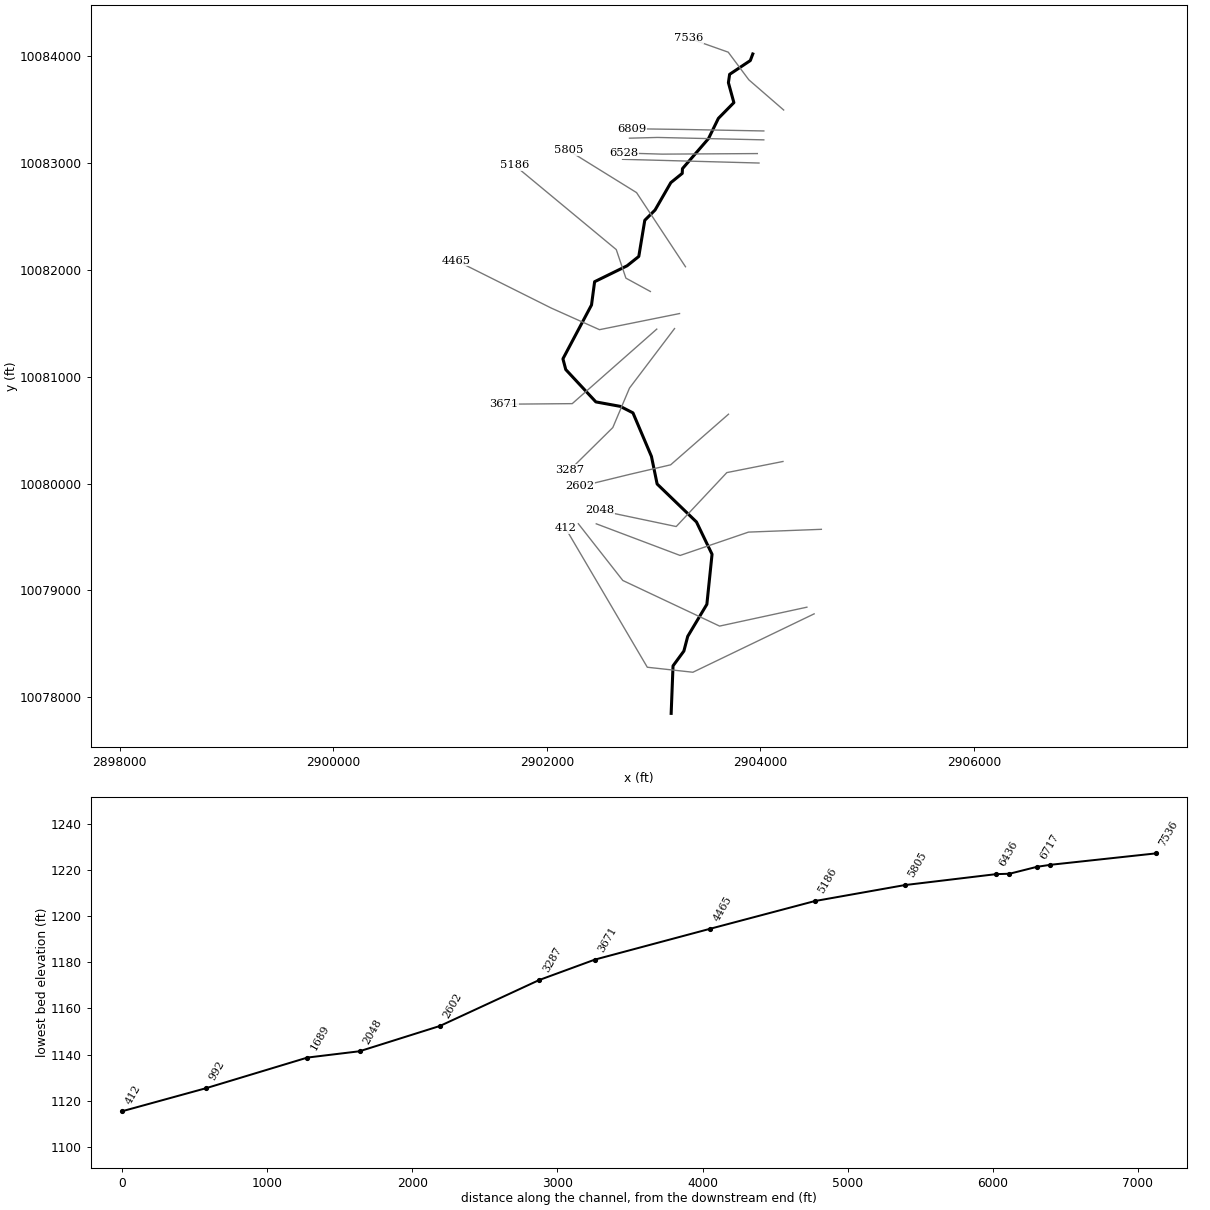
--- UNT 0051 IN LATR.prj (project) ---

Proj Title=UNT 1051 IN LATR Base Level Engineering
Current Plan=p01
Default Exp/Contr=0.3,0.1
English Units
Geom File=g01
Flow File=f01
Plan File=p01
BEGIN DESCRIPTION:
UNT 1051 IN LATR
END DESCRIPTION:

--- UNT 0051 IN LATR.p01 (plan) ---

Plan Title=Multiple Run
Short Identifier=Multiple
Geom File=g01
Flow File=f01
Subcritical Flow
K Sum by GR= 0
Std Step Tol= 0.01
Critical Tol= 0.01
Num of Std Step Trials= 20
Max Error Tol= 0.3
Flow Tol Ratio= 0.001
Split Flow NTrial= 30
Split Flow Tol= 0.02
Split Flow Ratio= 0.02
Log Output Level= 0
Friction Slope Method= 1
Unsteady Friction Slope Method= 2
Unsteady Bridges Friction Slope Method= 1
Parabolic Critical Depth
Global Vel Dist=  1 , 1 , 1
Global Log Level= 0
CheckData=True
Encroach Param= -1, 0, 0, 0
BEGIN DESCRIPTION:
Multiple Run
END DESCRIPTION:

--- UNT 0051 IN LATR.f01 (steady flow) ---

Flow Title=Multiple
Number of Profiles=7
Profile Names=10-year,25-year,50-year,1pct_min,100-year,1pct_plu,500-year
River Rch & RM= UNT 1051 IN LATR,Reach-1,7536
     734    1043    1306    1196    1618    2188    2493
River Rch & RM= UNT 1051 IN LATR,Reach-1,5805
    1100    1601    2037    1894    2562    3465    4071
Boundary for River Rch & Prof#=UNT 1051 IN LATR,Reach-1,1
Up Type=0
Dn Type=3
Dn Slope=0.005
Boundary for River Rch & Prof#=UNT 1051 IN LATR,Reach-1,2
Up Type=0
Dn Type=3
Dn Slope=0.005
Boundary for River Rch & Prof#=UNT 1051 IN LATR,Reach-1,3
Up Type=0
Dn Type=3
Dn Slope=0.005
Boundary for River Rch & Prof#=UNT 1051 IN LATR,Reach-1,4
Up Type=0
Dn Type=3
Dn Slope=0.005
Boundary for River Rch & Prof#=UNT 1051 IN LATR,Reach-1,5
Up Type=0
Dn Type=3
Dn Slope=0.005
Boundary for River Rch & Prof#=UNT 1051 IN LATR,Reach-1,6
Up Type=0
Dn Type=3
Dn Slope=0.005
Boundary for River Rch & Prof#=UNT 1051 IN LATR,Reach-1,7
Up Type=0
Dn Type=3
Dn Slope=0.005

--- UNT 0051 IN LATR.g01 (geometry) ---

Geom Title=Existing Conditions

River Reach=UNT 1051 IN LATR,Reach-1
Reach XY= 30
      2903928.07     10084023.27      2903904.86     10083961.52
      2903711.15     10083832.53      2903699.71     10083754.46
      2903750.96     10083567.66      2903605.94     10083420.20
      2903513.42     10083230.90      2903269.39     10082949.26
      2903267.28     10082904.81      2903160.33     10082818.13
      2903012.77     10082561.59      2902916.61     10082465.58
      2902860.44     10082126.99      2902750.85     10082039.36
      2902446.73     10081890.38      2902417.65     10081672.37
      2902149.94     10081168.04      2902176.47     10081067.65
      2902458.45     10080764.60      2902687.11     10080722.87
      2902805.80     10080661.95      2902979.04     10080253.97
      2903032.15     10079995.84      2903400.55     10079640.29
      2903546.50     10079337.71      2903498.04     10078869.01
      2903318.65     10078568.73      2903282.74     10078431.28
      2903181.11     10078292.63      2903163.64     10077847.56

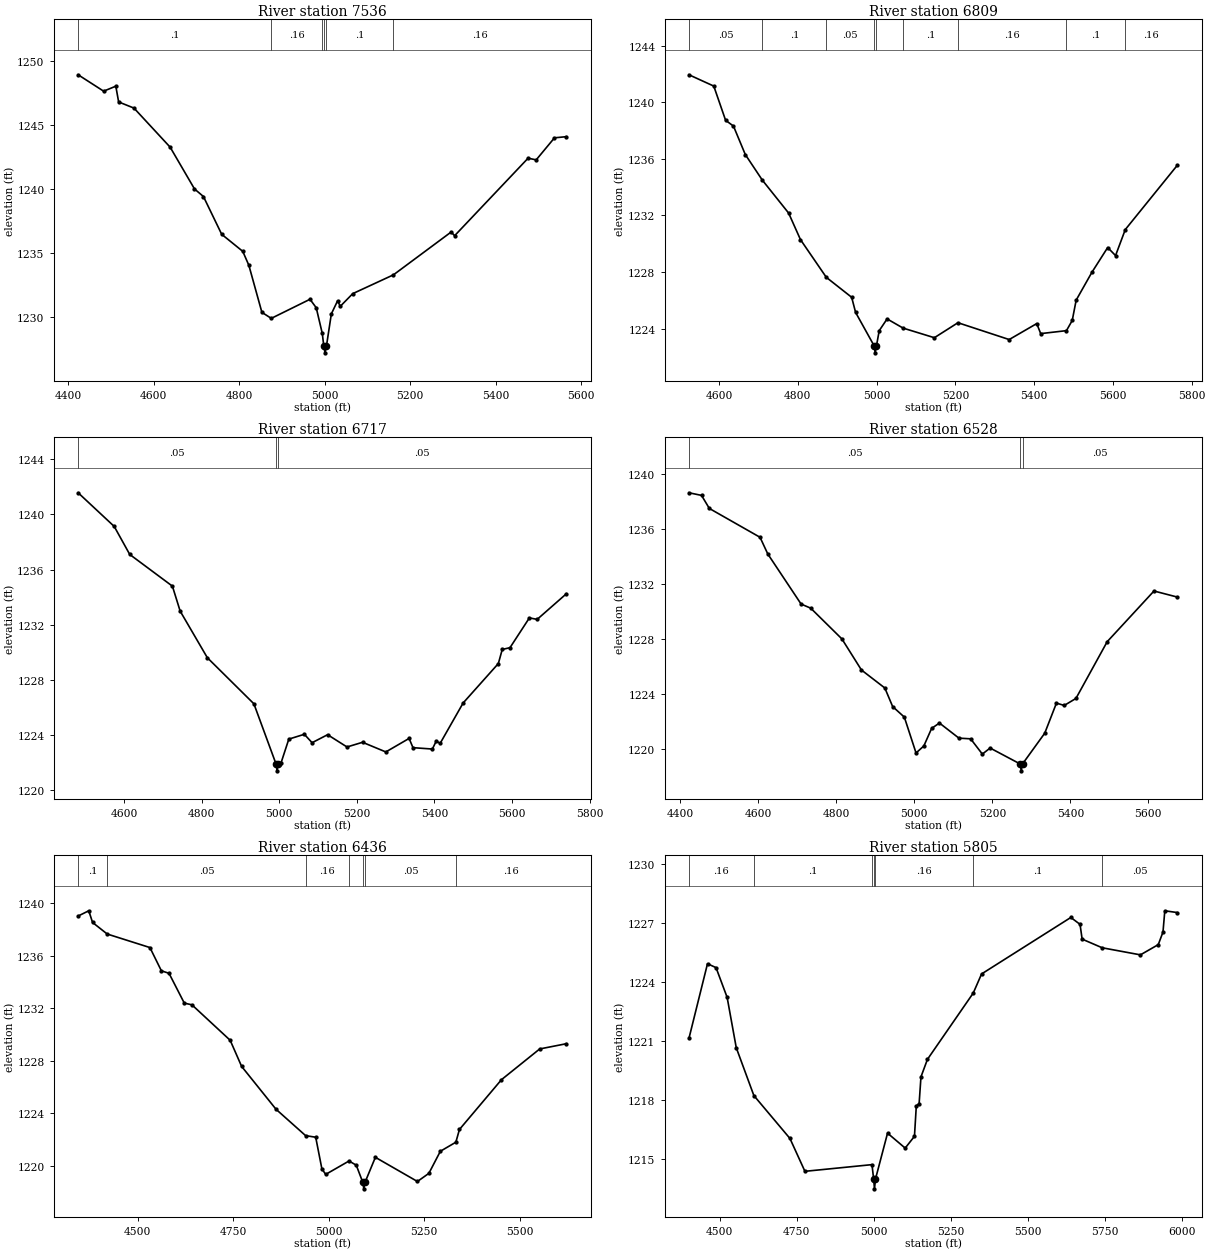
Type RM Length L Ch R = 1,7536,727,727,727
BEGIN DESCRIPTION:
UNT 1051 IN LATR 16.0
END DESCRIPTION:
XS GIS Cut Line= 4
      2904217.19     10083498.42      2903890.83     10083781.38
      2903698.12     10084040.06      2903331.80     10084169.66
#Sta/Elev= 30
  4422.8 1248.93  4482.5 1247.65  4511.0 1248.04  4517.6 1246.81  4553.5 1246.33
  4638.2 1243.28  4695.2 1240.02  4716.1 1239.43  4758.9 1236.48  4808.2 1235.15
  4822.5 1234.06  4853.0 1230.39  4875.0 1229.92  4965.6 1231.41  4980.2 1230.75
  4994.4 1228.74  4998.0 1227.73  5000.8 1227.23  5004.0 1227.73  5015.6 1230.27
  5030.2 1231.29  5036.5 1230.86  5065.7 1231.85  5161.1 1233.32  5296.1 1236.66
  5304.2 1236.37  5476.2 1242.42  5495.2 1242.29  5538.0 1244.01  5565.9 1244.10
#Mann=6,-1,0
  4422.8     0.1       0  4875.0    0.16       0  4994.4     0.1       0
  4998.0    0.07       0  5004.0     0.1       0  5161.1    0.16       0
Bank Sta=4998,5004
Exp/Cntr=0.3,0.1

Type RM Length L Ch R = 1,6809,92,92,92
BEGIN DESCRIPTION:
UNT 1051 IN LATR 15.0
END DESCRIPTION:
XS GIS Cut Line= 3
      2904031.47     10083302.22      2903286.66     10083316.11
      2902791.85     10083323.03
#Sta/Elev= 30
  4523.6 1241.95  4586.6 1241.15  4616.6 1238.73  4636.6 1238.32  4666.6 1236.31
  4709.8 1234.50  4776.6 1232.17  4806.7 1230.29  4872.4 1227.62  4936.7 1226.21
  4946.7 1225.14  4993.7 1222.78  4996.4 1222.28  4999.7 1222.78  5006.7 1223.85
  5026.7 1224.68  5067.3 1224.03  5146.7 1223.35  5206.6 1224.41  5336.7 1223.22
  5406.7 1224.35  5416.7 1223.64  5482.1 1223.85  5496.8 1224.57  5506.8 1226.01
  5546.8 1227.98  5586.8 1229.73  5606.8 1229.16  5631.5 1231.00  5763.4 1235.54
#Mann=9,-1,0
  4523.6    0.05       0  4709.8     0.1       0  4872.4    0.05       0
  4993.7    0.04       0  4999.7    0.05       0  5067.3     0.1       0
  5206.6    0.16       0  5482.1     0.1       0  5631.5    0.16       0
Bank Sta=4993.7,4999.7
Exp/Cntr=0.3,0.1

Type RM Length L Ch R = 1,6717,189,189,189
BEGIN DESCRIPTION:
UNT 1051 IN LATR 14.0
END DESCRIPTION:
XS GIS Cut Line= 3
      2904031.43     10083218.88      2903034.92     10083241.45
      2902773.08     10083234.52
#Sta/Elev= 30
  4481.6 1241.57  4574.6 1239.13  4614.6 1237.10  4724.6 1234.80  4744.6 1232.99
  4814.7 1229.61  4934.7 1226.27  4991.7 1221.91  4994.4 1221.41  4997.7 1221.91
  5004.7 1221.99  5024.7 1223.71  5064.7 1224.06  5084.7 1223.45  5124.7 1224.03
  5174.7 1223.14  5214.8 1223.48  5274.8 1222.78  5334.8 1223.76  5344.8 1223.09
  5394.8 1222.99  5404.8 1223.57  5414.8 1223.40  5474.1 1226.33  5564.9 1229.19
  5574.9 1230.21  5594.9 1230.34  5644.9 1232.50  5664.9 1232.39  5740.3 1234.25
#Mann=3,-1,0
  4481.6    0.05       0  4991.7    0.04       0  4997.7    0.05       0
Bank Sta=4991.7,4997.7
Exp/Cntr=0.3,0.1

Type RM Length L Ch R = 1,6528,92,92,92
BEGIN DESCRIPTION:
UNT 1051 IN LATR 13.0
END DESCRIPTION:
XS GIS Cut Line= 3
      2903970.64     10083090.41      2903078.33     10083085.20
      2902718.91     10083095.62
#Sta/Elev= 30
  4422.1 1238.65  4454.3 1238.46  4474.3 1237.51  4604.3 1235.41  4624.3 1234.19
  4709.6 1230.55  4734.3 1230.25  4814.3 1228.01  4864.3 1225.75  4924.3 1224.44
  4944.3 1223.09  4974.3 1222.32  5004.3 1219.71  5024.3 1220.22  5044.3 1221.50
  5064.3 1221.89  5114.3 1220.79  5144.3 1220.74  5174.3 1219.63  5194.3 1220.07
  5271.3 1218.91  5274.0 1218.41  5277.3 1218.91  5334.3 1221.15  5364.3 1223.34
  5384.3 1223.17  5414.3 1223.68  5494.4 1227.81  5614.4 1231.50  5674.0 1231.06
#Mann=3,-1,0
  4422.1    0.05       0  5271.3    0.04       0  5277.3    0.05       0
Bank Sta=5271.3,5277.3
Exp/Cntr=0.3,0.1

Type RM Length L Ch R = 1,6436,631,631,631
BEGIN DESCRIPTION:
UNT 1051 IN LATR 12.0
END DESCRIPTION:
XS GIS Cut Line= 2
      2903986.30     10083001.87      2902708.57     10083036.59
#Sta/Elev= 30
  4343.8 1239.01  4371.6 1239.41  4381.6 1238.52  4419.9 1237.64  4531.7 1236.61
  4561.7 1234.84  4581.7 1234.65  4621.7 1232.38  4641.7 1232.25  4741.8 1229.55
  4771.8 1227.56  4861.8 1224.30  4939.3 1222.29  4965.7 1222.17  4981.9 1219.76
  4991.9 1219.34  5053.0 1220.36  5071.9 1220.04  5088.9 1218.74  5091.7 1218.24
  5094.9 1218.74  5121.9 1220.64  5232.0 1218.80  5262.0 1219.42  5292.0 1221.10
  5332.6 1221.79  5342.0 1222.76  5452.0 1226.55  5552.1 1228.89  5622.0 1229.29
#Mann=7,-1,0
  4343.8     0.1       0  4419.9    0.05       0  4939.3    0.16       0
  5053.0    0.05       0  5088.9    0.07       0  5094.9    0.05       0
  5332.6    0.16       0
Bank Sta=5088.9,5094.9
Exp/Cntr=0.3,0.1

Type RM Length L Ch R = 1,5805,619,619,619
BEGIN DESCRIPTION:
Mapping XS 3c0d1643
END DESCRIPTION:
XS GIS Cut Line= 3
      2903297.77     10082030.42      2902839.42     10082724.90
      2902200.50     10083120.75
#Sta/Elev= 30
  4400.4 1221.13  4460.5 1224.92  4488.2 1224.72  4524.2 1223.21  4553.8 1220.65
  4610.9 1218.22  4727.9 1216.04  4776.5 1214.37  4994.0 1214.71  4999.4 1213.98
  5002.1 1213.48  5005.4 1213.98  5044.5 1216.31  5101.7 1215.55  5131.8 1216.15
  5137.8 1217.70  5146.9 1217.81  5152.9 1219.17  5173.9 1220.06  5322.5 1223.43
  5349.5 1224.40  5639.0 1227.27  5668.9 1226.92  5675.6 1226.17  5740.7 1225.73
  5864.7 1225.37  5922.6 1225.89  5937.9 1226.53  5943.8 1227.61  5984.1 1227.52
#Mann=7,-1,0
  4400.4    0.16       0  4610.9     0.1       0  4994.0    0.16       0
  4999.4    0.07       0  5005.4    0.16       0  5322.5     0.1       0
  5740.7    0.05       0
Bank Sta=4999.4,5005.4
Exp/Cntr=0.3,0.1

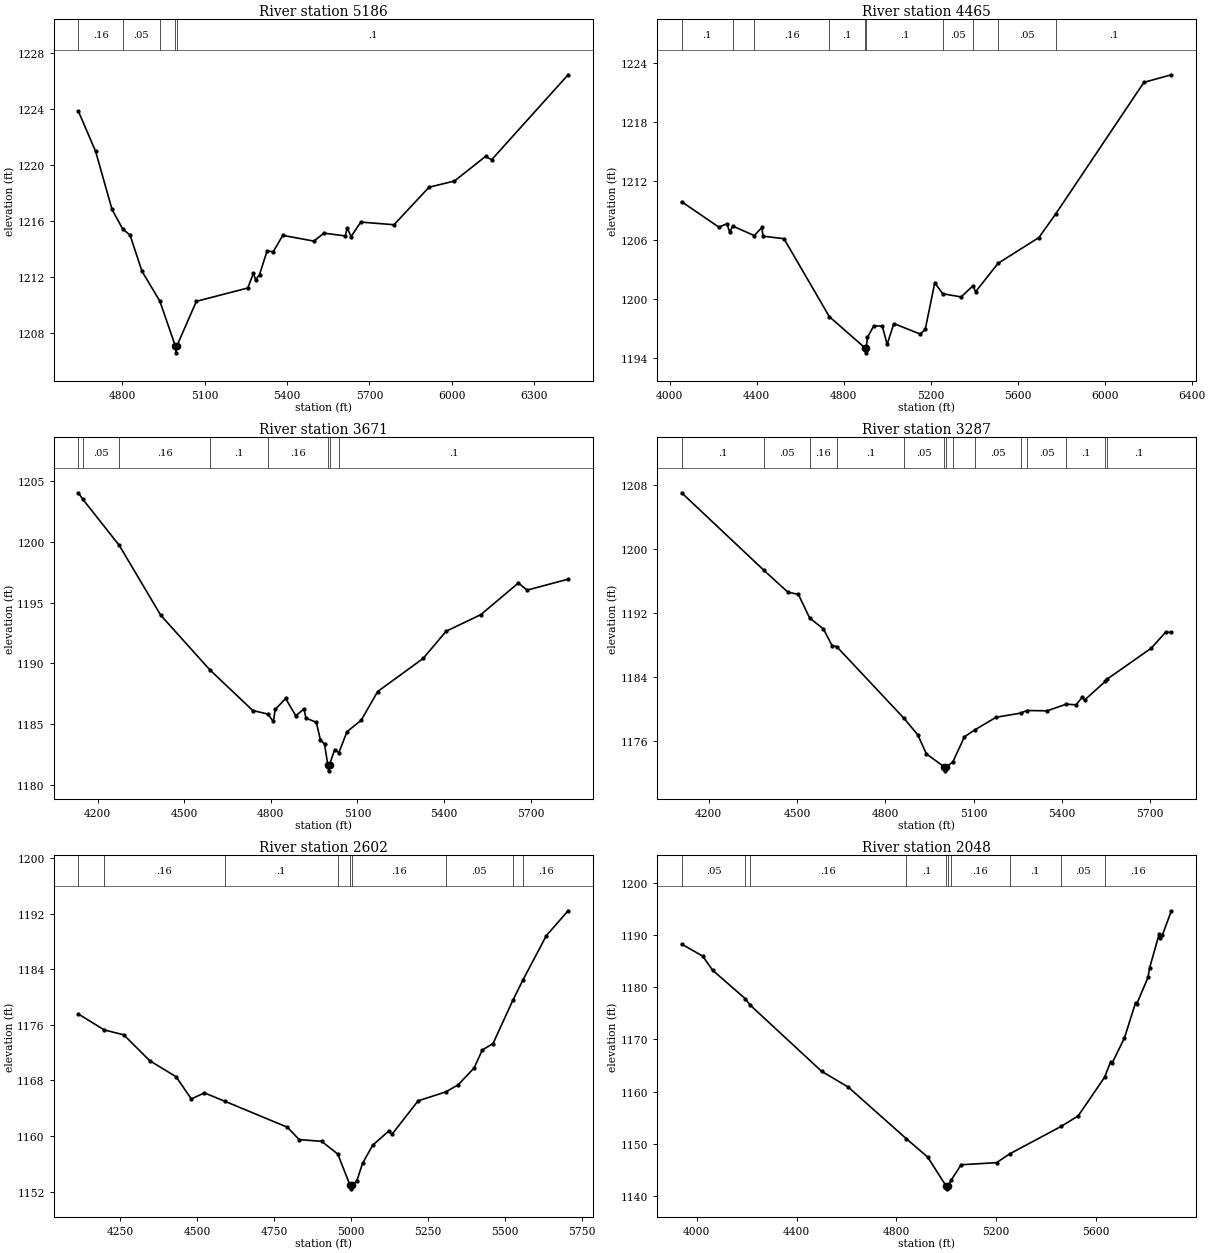
Type RM Length L Ch R = 1,5186,721,721,721
BEGIN DESCRIPTION:
UNT 1051 IN LATR 10.0
END DESCRIPTION:
XS GIS Cut Line= 4
      2902968.94     10081798.75      2902739.78     10081923.75
      2902649.51     10082191.11      2901694.63     10082982.79
#Sta/Elev= 30
  4639.9 1223.82  4702.8 1220.95  4762.6 1216.80  4801.3 1215.41  4828.1 1214.97
  4871.8 1212.38  4936.6 1210.26  4992.9 1207.06  4995.7 1206.56  4998.9 1207.06
  5069.8 1210.24  5256.8 1211.19  5277.6 1212.24  5285.5 1211.78  5299.8 1212.15
  5327.4 1213.85  5349.3 1213.77  5384.4 1214.95  5497.7 1214.54  5534.2 1215.11
  5612.4 1214.91  5618.9 1215.49  5633.2 1214.86  5668.3 1215.90  5789.5 1215.71
  5917.1 1218.39  6009.6 1218.83  6122.9 1220.59  6145.0 1220.35  6423.5 1226.42
#Mann=5,-1,0
  4639.9    0.16       0  4801.3    0.05       0  4936.6     0.1       0
  4992.9    0.07       0  4998.9     0.1       0
Bank Sta=4992.9,4998.9
Exp/Cntr=0.3,0.1

Type RM Length L Ch R = 1,4465,794,794,794
BEGIN DESCRIPTION:
UNT 1051 IN LATR 9.0
END DESCRIPTION:
XS GIS Cut Line= 4
      2903242.17     10081592.14      2902492.21     10081441.11
      2902039.09     10081644.23      2901153.68     10082086.93
#Sta/Elev= 30
  4055.1 1209.90  4225.8 1207.32  4262.9 1207.65  4276.6 1206.78  4289.2 1207.43
  4389.0 1206.46  4424.0 1207.28  4429.1 1206.40  4525.6 1206.14  4733.9 1198.23
  4897.9 1195.05  4900.7 1194.55  4903.9 1195.05  4909.3 1196.12  4937.9 1197.27
  4977.6 1197.28  4999.6 1195.40  5030.6 1197.52  5152.0 1196.46  5174.9 1196.93
  5218.7 1201.66  5255.6 1200.55  5339.7 1200.23  5394.1 1201.35  5406.8 1200.76
  5509.6 1203.64  5697.5 1206.26  5773.9 1208.63  6180.2 1222.02  6306.6 1222.79
#Mann=10,-1,0
  4055.1     0.1       0  4289.2    0.05       0  4389.0    0.16       0
  4733.9     0.1       0  4897.9    0.07       0  4903.9     0.1       0
  5255.6    0.05       0  5394.1     0.1       0  5509.6    0.05       0
  5773.9     0.1       0
Bank Sta=4897.9,4903.9
Exp/Cntr=0.3,0.1

Type RM Length L Ch R = 1,3671,384,384,384
BEGIN DESCRIPTION:
UNT 1051 IN LATR 8.0
END DESCRIPTION:
XS GIS Cut Line= 3
      2903028.68     10081446.32      2902237.01     10080748.40
      2901596.41     10080743.19
#Sta/Elev= 30
  4133.5 1204.01  4148.6 1203.49  4275.3 1199.69  4418.8 1193.96  4588.4 1189.49
  4737.5 1186.14  4789.9 1185.85  4808.7 1185.24  4815.3 1186.23  4851.3 1187.13
  4886.5 1185.71  4914.9 1186.27  4921.6 1185.52  4957.6 1185.17  4971.8 1183.73
  4986.1 1183.38  4997.3 1181.69  5000.0 1181.19  5003.3 1181.69  5021.2 1182.94
  5036.0 1182.69  5063.8 1184.40  5113.2 1185.35  5170.1 1187.70  5327.4 1190.41
  5407.4 1192.65  5527.4 1194.01  5657.4 1196.61  5687.4 1196.02  5829.5 1196.92
#Mann=8,-1,0
  4133.5     0.1       0  4148.6    0.05       0  4275.3    0.16       0
  4588.4     0.1       0  4789.9    0.16       0  4997.3    0.07       0
  5003.3    0.16       0  5036.0     0.1       0
Bank Sta=4997.3,5003.3
Exp/Cntr=0.3,0.1

Type RM Length L Ch R = 1,3287,685,685,685
BEGIN DESCRIPTION:
UNT 1051 IN LATR 7.0
END DESCRIPTION:
XS GIS Cut Line= 4
      2903195.34     10081451.52      2902773.46     10080894.23
      2902617.21     10080524.44      2902216.24     10080128.67
#Sta/Elev= 30
  4107.8 1207.08  4387.9 1197.37  4468.7 1194.66  4504.3 1194.38  4542.6 1191.44
  4589.6 1190.06  4618.7 1187.99  4634.4 1187.86  4863.5 1178.88  4910.0 1176.83
  4939.1 1174.45  4999.7 1172.83  5002.5 1172.33  5005.7 1172.83  5028.5 1173.40
  5068.5 1176.58  5104.5 1177.47  5176.4 1179.03  5259.0 1179.54  5281.3 1179.87
  5349.2 1179.83  5414.3 1180.66  5448.2 1180.58  5469.5 1181.59  5476.5 1181.17
  5547.4 1183.52  5551.6 1183.75  5702.8 1187.65  5752.3 1189.66  5771.6 1189.63
#Mann=14,-1,0
  4107.8     0.1       0  4387.9    0.05       0  4542.6    0.16       0
  4634.4     0.1       0  4863.5    0.05       0  4999.7    0.04       0
  5005.7    0.05       0  5028.5     0.1       0  5104.5    0.05       0
  5259.0     0.1       0  5281.3    0.05       0  5414.3     0.1       0
  5547.4    0.05       0  5551.6     0.1       0
Bank Sta=4999.7,5005.7
Exp/Cntr=0.3,0.1

Type RM Length L Ch R = 1,2602,554,554,554
BEGIN DESCRIPTION:
UNT 1051 IN LATR 6.0
END DESCRIPTION:
XS GIS Cut Line= 4
      2903700.56     10080649.45      2903158.88     10080175.48
      2902778.67     10080086.94      2902311.67     10079972.78
#Sta/Elev= 30
  4113.9 1177.56  4197.8 1175.27  4261.5 1174.56  4346.0 1170.83  4431.4 1168.53
  4480.8 1165.33  4523.5 1166.20  4589.1 1165.01  4793.0 1161.26  4831.2 1159.48
  4904.2 1159.23  4956.6 1157.40  4996.6 1152.89  4999.3 1152.39  5002.6 1152.89
  5018.9 1153.58  5037.0 1156.06  5070.2 1158.68  5121.6 1160.69  5132.5 1160.23
  5217.6 1165.06  5307.2 1166.34  5347.9 1167.37  5399.3 1169.78  5426.0 1172.37
  5461.0 1173.31  5525.3 1179.53  5558.1 1182.46  5634.3 1188.85  5704.8 1192.42
#Mann=9,-1,0
  4113.9     0.1       0  4197.8    0.16       0  4589.1     0.1       0
  4956.6    0.16       0  4996.6    0.07       0  5002.6    0.16       0
  5307.2    0.05       0  5525.3     0.1       0  5558.1    0.16       0
Bank Sta=4996.6,5002.6
Exp/Cntr=0.3,0.1

Type RM Length L Ch R = 1,2048,359,359,359
BEGIN DESCRIPTION:
UNT 1051 IN LATR 5.0
END DESCRIPTION:
XS GIS Cut Line= 4
      2904210.92     10080206.72      2903684.92     10080102.56
      2903210.96     10079597.36      2902492.88     10079748.26
#Sta/Elev= 30
  3939.1 1188.25  4023.2 1185.95  4063.9 1183.21  4194.7 1177.78  4213.8 1176.57
  4500.5 1163.89  4606.5 1160.90  4839.7 1151.00  4924.9 1147.51  4999.6 1141.92
  5002.4 1141.42  5005.6 1141.92  5019.0 1143.07  5059.3 1146.03  5201.2 1146.43
  5253.3 1148.10  5459.3 1153.35  5528.2 1155.37  5634.0 1162.77  5658.5 1165.74
  5663.6 1165.42  5713.4 1170.26  5758.2 1177.03  5763.3 1176.83  5808.0 1181.87
  5814.3 1183.66  5852.8 1190.17  5857.9 1189.33  5865.4 1189.95  5901.8 1194.62
#Mann=10,-1,0
  3939.1    0.05       0  4194.7     0.1       0  4213.8    0.16       0
  4839.7     0.1       0  4999.6    0.07       0  5005.6     0.1       0
  5019.0    0.16       0  5253.3     0.1       0  5459.3    0.05       0
  5634.0    0.16       0
Bank Sta=4999.6,5005.6
Exp/Cntr=0.3,0.1

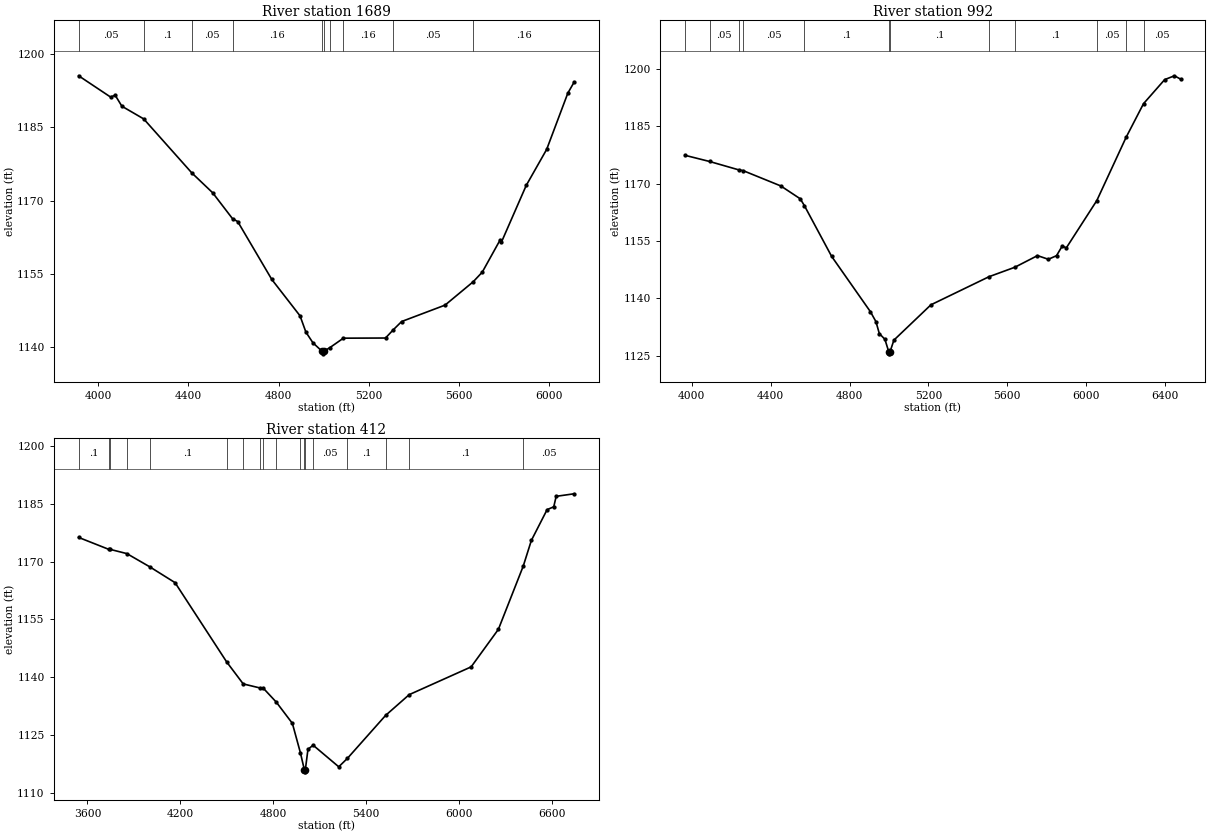
Type RM Length L Ch R = 1,1689,697,697,697
BEGIN DESCRIPTION:
UNT 1051 IN LATR 4.0
END DESCRIPTION:
XS GIS Cut Line= 4
      2904570.30     10079571.31      2903888.05     10079545.27
      2903247.42     10079326.52      2902462.20     10079622.93
#Sta/Elev= 30
  3912.6 1195.48  4054.5 1191.13  4074.6 1191.52  4104.6 1189.26  4201.4 1186.67
  4415.1 1175.63  4507.3 1171.59  4595.7 1166.28  4618.5 1165.71  4769.8 1153.88
  4895.1 1146.45  4921.1 1143.13  4952.4 1140.94  4993.4 1139.19  4996.2 1138.69
  4999.4 1139.19  5027.5 1139.96  5087.5 1141.89  5274.4 1141.92  5308.2 1143.57
  5346.0 1145.29  5538.6 1148.64  5663.5 1153.41  5703.7 1155.37  5783.6 1162.00
  5788.9 1161.51  5899.0 1173.10  5989.6 1180.45  6083.5 1191.94  6111.6 1194.20
#Mann=10,-1,0
  3912.6    0.05       0  4201.4     0.1       0  4415.1    0.05       0
  4595.7    0.16       0  4993.4    0.07       0  4999.4    0.16       0
  5027.5     0.1       0  5087.5    0.16       0  5308.2    0.05       0
  5663.5    0.16       0
Bank Sta=4993.4,4999.4
Exp/Cntr=0.3,0.1

Type RM Length L Ch R = 1,992,580,580,580
BEGIN DESCRIPTION:
UNT 1051 IN LATR 2.0
END DESCRIPTION:
XS GIS Cut Line= 4
      2904434.88     10078842.14      2903617.21     10078665.06
      2902710.96     10079092.15      2902294.31     10079623.38
#Sta/Elev= 30
  3966.0 1177.44  4090.1 1175.83  4237.7 1173.64  4260.4 1173.43  4451.5 1169.42
  4549.9 1166.06  4570.8 1164.29  4709.3 1150.97  4905.7 1136.50  4934.0 1133.88
  4951.2 1130.75  4979.5 1129.25  4999.3 1125.94  5002.1 1125.44  5005.3 1125.94
  5025.1 1129.03  5212.9 1138.28  5507.8 1145.65  5638.5 1148.12  5753.5 1151.17
  5808.6 1150.21  5850.0 1151.15  5878.9 1153.68  5899.7 1153.20  6054.3 1165.58
  6203.0 1182.16  6291.3 1190.97  6398.7 1197.28  6448.4 1198.28  6479.6 1197.39
#Mann=12,-1,0
  3966.0     0.1       0  4090.1    0.05       0  4237.7     0.1       0
  4260.4    0.05       0  4570.8     0.1       0  4999.3    0.07       0
  5005.3     0.1       0  5507.8    0.05       0  5638.5     0.1       0
  6054.3    0.05       0  6203.0    0.16       0  6291.3    0.05       0
Bank Sta=4999.3,5005.3
Exp/Cntr=0.3,0.1

Type RM Length L Ch R = 1,412,0,0,0
BEGIN DESCRIPTION:
UNT 1051 IN LATR 1.0
END DESCRIPTION:
XS GIS Cut Line= 4
      2904502.59     10078779.63      2903367.21     10078232.77
      2902940.13     10078279.65      2902175.40     10079580.22
#Sta/Elev= 30
  3543.2 1176.31  3739.2 1173.19  3747.1 1173.20  3854.4 1172.11  4001.6 1168.69
  4165.6 1164.56  4498.3 1143.99  4605.6 1138.25  4712.9 1137.21  4733.6 1137.21
  4819.1 1133.52  4922.9 1128.00  4974.7 1120.36  5000.4 1115.91  5003.1 1115.41
  5006.4 1115.91  5023.5 1121.27  5056.8 1122.33  5222.2 1116.72  5278.6 1118.93
  5524.6 1130.07  5676.8 1135.46  6076.8 1142.68  6252.6 1152.43  6412.9 1168.84
  6465.5 1175.54  6567.1 1183.53  6610.0 1184.27  6625.7 1186.99  6741.8 1187.65
#Mann=18,-1,0
  3543.2     0.1       0  3739.2    0.16       0  3747.1     0.1       0
  3854.4    0.05       0  4001.6     0.1       0  4498.3    0.05       0
  4605.6     0.1       0  4712.9    0.05       0  4733.6     0.1       0
  4819.1    0.05       0  4974.7     0.1       0  5000.4    0.07       0
  5006.4     0.1       0  5056.8    0.05       0  5278.6     0.1       0
  5524.6    0.05       0  5676.8     0.1       0  6412.9    0.05       0
Bank Sta=5000.4,5006.4
Exp/Cntr=0.3,0.1

Chan Stop Cuts=-1