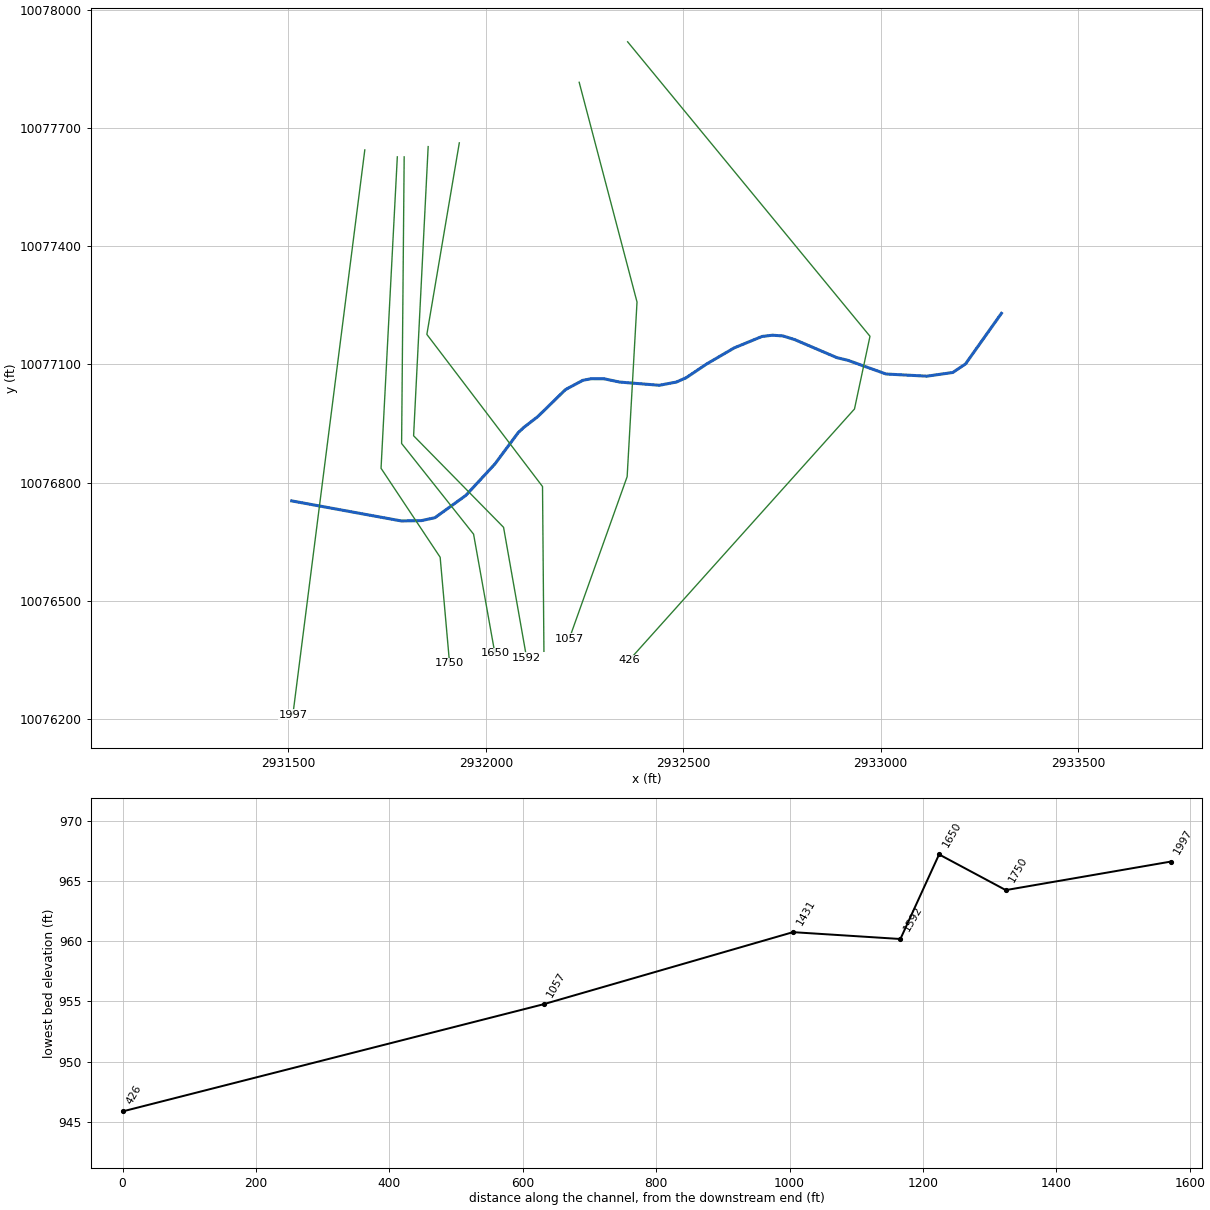
--- UNT 0054 IN LATR.prj (project) ---

Proj Title=UNT 1054 IN LATR Base Level Engineering
Current Plan=p01
Default Exp/Contr=0.3,0.1
English Units
Geom File=g01
Flow File=f01
Plan File=p01
BEGIN DESCRIPTION:
UNT 1054 IN LATR
END DESCRIPTION:

--- UNT 0054 IN LATR.p01 (plan) ---

Plan Title=Multiple Run
Short Identifier=Multiple
Geom File=g01
Flow File=f01
Subcritical Flow
K Sum by GR= 0
Std Step Tol= 0.01
Critical Tol= 0.01
Num of Std Step Trials= 20
Max Error Tol= 0.3
Flow Tol Ratio= 0.001
Split Flow NTrial= 30
Split Flow Tol= 0.02
Split Flow Ratio= 0.02
Log Output Level= 0
Friction Slope Method= 1
Unsteady Friction Slope Method= 2
Unsteady Bridges Friction Slope Method= 1
Parabolic Critical Depth
Global Vel Dist=  1 , 1 , 1
Global Log Level= 0
CheckData=True
Encroach Param= -1, 0, 0, 0
BEGIN DESCRIPTION:
Multiple Run
END DESCRIPTION:

--- UNT 0054 IN LATR.f01 (steady flow) ---

Flow Title=Multiple
Number of Profiles=7
Profile Names=10-year,25-year,50-year,1pct_min,100-year,1pct_plu,500-year
River Rch & RM= UNT 1054 IN LATR,Reach-1,1997
     832    1199    1515    1401    1895    2563    2978
Boundary for River Rch & Prof#=UNT 1054 IN LATR,Reach-1,1
Up Type=0
Dn Type=3
Dn Slope=0.005
Boundary for River Rch & Prof#=UNT 1054 IN LATR,Reach-1,2
Up Type=0
Dn Type=3
Dn Slope=0.005
Boundary for River Rch & Prof#=UNT 1054 IN LATR,Reach-1,3
Up Type=0
Dn Type=3
Dn Slope=0.005
Boundary for River Rch & Prof#=UNT 1054 IN LATR,Reach-1,4
Up Type=0
Dn Type=3
Dn Slope=0.005
Boundary for River Rch & Prof#=UNT 1054 IN LATR,Reach-1,5
Up Type=0
Dn Type=3
Dn Slope=0.005
Boundary for River Rch & Prof#=UNT 1054 IN LATR,Reach-1,6
Up Type=0
Dn Type=3
Dn Slope=0.005
Boundary for River Rch & Prof#=UNT 1054 IN LATR,Reach-1,7
Up Type=0
Dn Type=3
Dn Slope=0.005

--- UNT 0054 IN LATR.g01 (geometry) ---

Geom Title=Existing Conditions

River Reach=UNT 1054 IN LATR,Reach-1
Reach XY= 30
      2931508.47     10076753.73      2931786.16     10076702.87
      2931836.94     10076703.74      2931871.23     10076711.12
      2931949.36     10076767.54      2932023.14     10076847.40
      2932081.84     10076926.54      2932095.24     10076939.25
      2932132.10     10076967.88      2932201.86     10077036.06
      2932245.57     10077059.51      2932267.25     10077063.74
      2932299.47     10077063.52      2932339.07     10077055.17
      2932439.71     10077047.02      2932482.68     10077055.19
      2932507.41     10077066.06      2932559.55     10077101.11
      2932629.25     10077141.84      2932699.81     10077170.88
      2932726.18     10077174.03      2932752.99     10077172.14
      2932782.97     10077162.70      2932889.80     10077116.95
      2932917.09     10077110.42      2933014.03     10077075.60
      2933117.61     10077070.13      2933182.98     10077079.49
      2933215.24     10077101.22      2933306.16     10077229.49

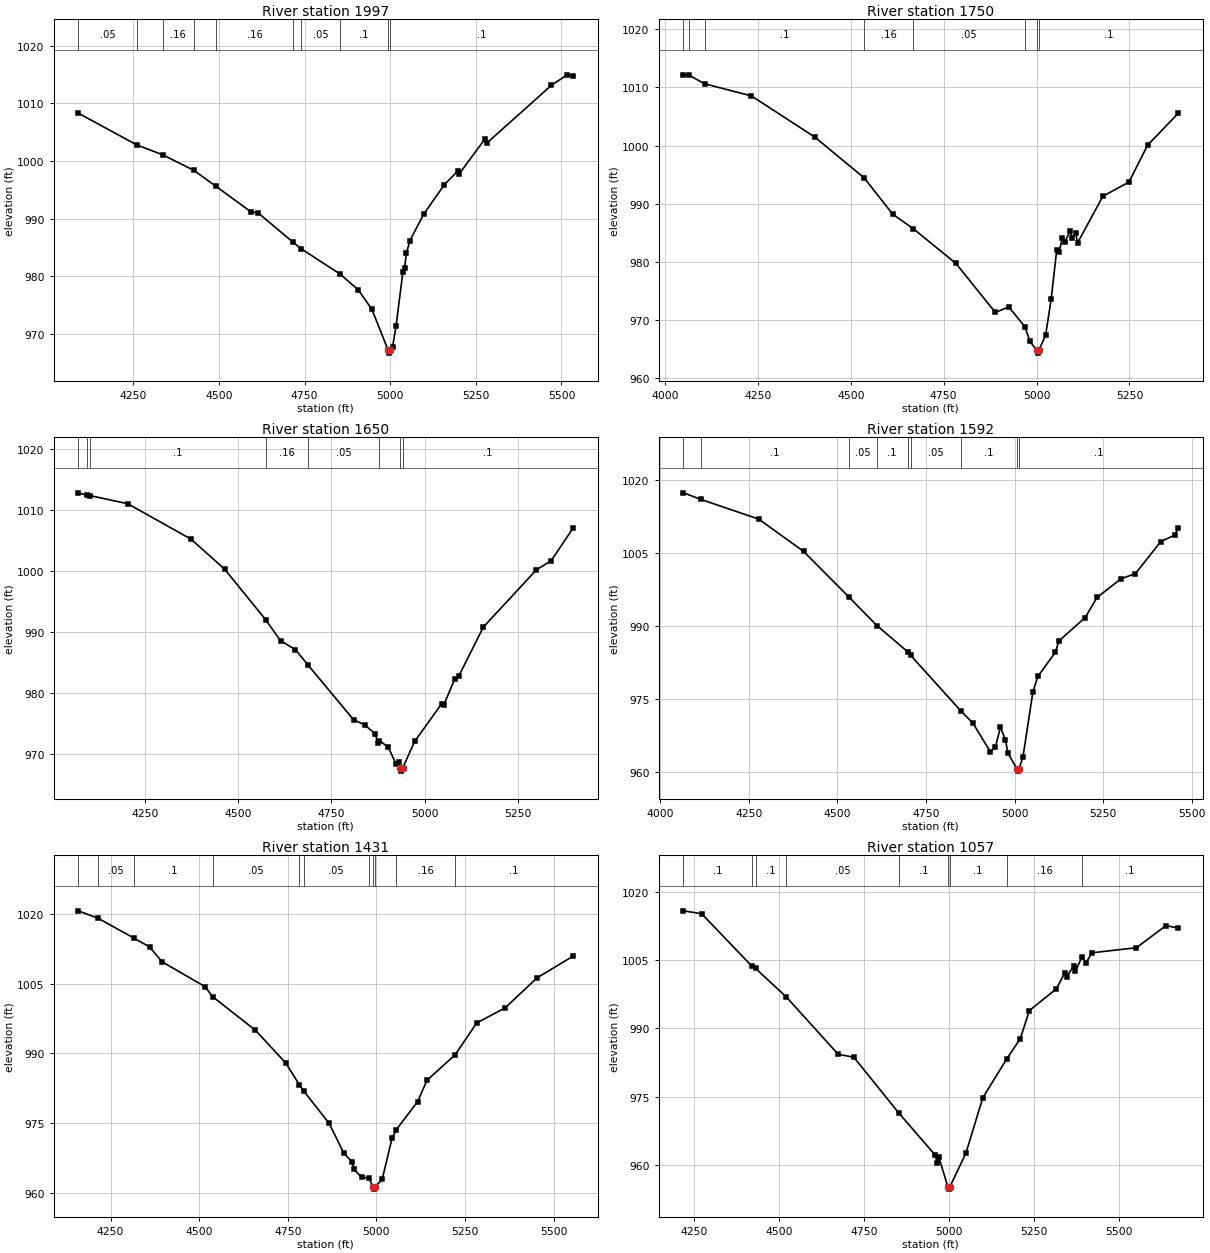
Type RM Length L Ch R = 1,1997,247,247,247
BEGIN DESCRIPTION:
UNT 1054 IN LATR 4.0
END DESCRIPTION:
XS GIS Cut Line= 2
      2931693.57     10077644.06      2931511.37     10076211.50
#Sta/Elev= 30
  4089.4 1008.32  4260.7 1002.79  4335.4 1001.10  4425.8  998.42  4491.6  995.61
  4593.8  991.16  4613.9  991.02  4716.6  985.89  4740.8  984.74  4852.6  980.42
  4906.3  977.66  4946.6  974.24  4994.0  967.14  4996.7  966.64  5000.0  967.14
  5007.1  967.79  5017.1  971.33  5036.8  980.65  5041.8  981.47  5047.4  984.01
  5057.5  986.18  5097.8  990.78  5158.3  995.92  5196.7  998.22  5201.7  997.80
  5276.7 1003.85  5281.7 1003.11  5470.8 1013.17  5516.5 1014.98  5533.5 1014.83
#Mann=10,-1,0
  4089.4    0.05       0  4260.7     0.1       0  4335.4    0.16       0
  4425.8     0.1       0  4491.6    0.16       0  4716.6     0.1       0
  4740.8    0.05       0  4852.6     0.1       0  4994.0    0.07       0
  5000.0     0.1       0
Bank Sta=4994,5000
Exp/Cntr=0.3,0.1

Type RM Length L Ch R = 1,1750,100,100,100
BEGIN DESCRIPTION:
Mapping XS 11735282
END DESCRIPTION:
XS GIS Cut Line= 4
      2931775.93     10077626.41      2931734.70     10076836.49
      2931884.44     10076610.80      2931908.31     10076341.70
#Sta/Elev= 30
  4049.4 1012.18  4065.0 1012.10  4106.1 1010.64  4232.3 1008.55  4402.6 1001.48
  4535.8  994.44  4612.8  988.19  4668.2  985.69  4783.1  979.70  4889.1  971.27
  4925.2  972.22  4968.7  968.81  4982.3  966.28  5000.3  964.77  5003.1  964.27
  5006.3  964.77  5024.4  967.34  5039.4  973.54  5054.5  982.09  5060.5  981.63
  5069.5  984.05  5075.5  983.37  5090.6  985.25  5096.6  984.07  5105.6  984.96
  5110.4  983.24  5178.6  991.27  5248.9  993.72  5299.0 1000.07  5381.4 1005.55
#Mann=8,-1,0
  4049.4     0.1       0  4065.0    0.05       0  4106.1     0.1       0
  4535.8    0.16       0  4668.2    0.05       0  4968.7     0.1       0
  5000.3    0.07       0  5006.3     0.1       0
Bank Sta=5000.3,5006.3
Exp/Cntr=0.3,0.1

Type RM Length L Ch R = 1,1650,58,58,58
BEGIN DESCRIPTION:
Mapping XS 6467026c
END DESCRIPTION:
XS GIS Cut Line= 4
      2931793.29     10077626.39      2931786.78     10076899.42
      2931969.08     10076669.39      2932023.04     10076367.17
#Sta/Elev= 30
  4070.7 1012.79  4094.3 1012.39  4102.0 1012.34  4203.4 1011.01  4373.4 1005.20
  4463.4 1000.30  4573.7  992.01  4613.4  988.59  4653.4  987.13  4686.8  984.64
  4809.9  975.62  4838.8  974.84  4867.6  973.34  4874.0  971.91  4878.7  972.25
  4902.9  971.13  4923.7  968.34  4931.7  968.76  4935.1  967.74  4937.8  967.24
  4941.1  967.74  4973.3  972.09  5045.5  978.24  5051.9  978.11  5080.7  982.29
  5091.2  982.73  5157.9  990.83  5300.1 1000.19  5339.7 1001.68  5398.2 1006.99
#Mann=8,-1,0
  4070.7     0.1       0  4094.3    0.05       0  4102.0     0.1       0
  4573.7    0.16       0  4686.8    0.05       0  4878.7     0.1       0
  4935.1    0.07       0  4941.1     0.1       0
Bank Sta=4935.1,4941.1
Exp/Cntr=0.3,0.1

Type RM Length L Ch R = 1,1592,161,161,161
BEGIN DESCRIPTION:
Mapping XS dbb30e45
END DESCRIPTION:
XS GIS Cut Line= 4
      2931854.06     10077652.44      2931817.17     10076918.96
      2932045.03     10076686.75      2932103.55     10076355.12
#Sta/Elev= 30
  4065.5 1017.34  4114.9 1015.98  4277.9 1011.95  4404.6 1005.31  4531.9  995.99
  4611.5  990.09  4698.1  984.72  4707.0  983.96  4848.7  972.54  4882.3  970.08
  4931.9  964.16  4946.0  965.11  4960.2  969.20  4974.3  966.65  4981.3  963.90
  5006.6  960.70  5009.3  960.20  5012.6  960.70  5023.7  963.05  5052.0  976.52
  5066.2  979.67  5115.6  984.63  5125.2  986.92  5199.4  991.73  5233.1  995.86
  5300.9  999.71  5341.4 1000.75  5412.6 1007.33  5453.3 1008.70  5462.0 1010.15
#Mann=9,-1,0
  4065.5    0.05       0  4114.9     0.1       0  4531.9    0.05       0
  4611.5     0.1       0  4698.1    0.16       0  4707.0    0.05       0
  4848.7     0.1       0  5006.6    0.07       0  5012.6     0.1       0
Bank Sta=5006.6,5012.6
Exp/Cntr=0.3,0.1

Type RM Length L Ch R = 1,1431,374,374,374
BEGIN DESCRIPTION:
UNT 1054 IN LATR 3.0
END DESCRIPTION:
XS GIS Cut Line= 4
      2931932.94     10077661.96      2931850.77     10077176.07
      2932143.73     10076790.22      2932147.30     10076372.19
#Sta/Elev= 30
  4159.1 1020.70  4215.7 1019.07  4316.2 1014.82  4360.1 1012.92  4395.7 1009.72
  4516.6 1004.37  4537.7 1002.23  4658.7  994.99  4744.0  987.96  4782.5  983.27
  4795.0  981.90  4866.7  974.93  4908.3  968.47  4931.0  966.71  4937.4  965.01
  4958.2  963.31  4978.3  963.18  4990.8  961.27  4993.6  960.77  4996.8  961.27
  5016.4  962.89  5044.1  971.73  5056.5  973.60  5116.2  979.62  5142.8  984.22
  5222.0  989.69  5282.8  996.56  5362.8  999.78  5452.9 1006.25  5554.4 1010.93
#Mann=11,-1,0
  4159.1     0.1       0  4215.7    0.05       0  4316.2     0.1       0
  4537.7    0.05       0  4782.5     0.1       0  4795.0    0.05       0
  4978.3     0.1       0  4990.8    0.07       0  4996.8     0.1       0
  5056.5    0.16       0  5222.0     0.1       0
Bank Sta=4990.8,4996.8
Exp/Cntr=0.3,0.1

Type RM Length L Ch R = 1,1057,631,631,631
BEGIN DESCRIPTION:
UNT 1054 IN LATR 2.0
END DESCRIPTION:
XS GIS Cut Line= 4
      2932236.62     10077815.54      2932383.09     10077258.24
      2932358.08     10076815.23      2932211.61     10076404.40
#Sta/Elev= 30
  4219.0 1015.77  4272.6 1015.13  4419.5 1003.70  4431.0 1003.15  4521.4  996.91
  4674.7  984.30  4720.2  983.70  4852.7  971.46  4960.0  962.22  4965.5  960.57
  4970.5  961.84  4997.1  955.27  4999.8  954.77  5003.1  955.27  5050.1  962.61
  5100.2  974.83  5170.0  983.25  5210.4  987.77  5237.2  993.92  5316.2  998.64
  5341.7 1002.19  5347.0 1001.33  5367.2 1003.65  5372.5 1002.53  5392.7 1005.75
  5403.3 1004.28  5421.0 1006.57  5552.1 1007.68  5639.2 1012.54  5675.1 1012.00
#Mann=9,-1,0
  4219.0     0.1       0  4419.5    0.05       0  4431.0     0.1       0
  4521.4    0.05       0  4852.7     0.1       0  4997.1    0.07       0
  5003.1     0.1       0  5170.0    0.16       0  5392.7     0.1       0
Bank Sta=4997.1,5003.1
Exp/Cntr=0.3,0.1

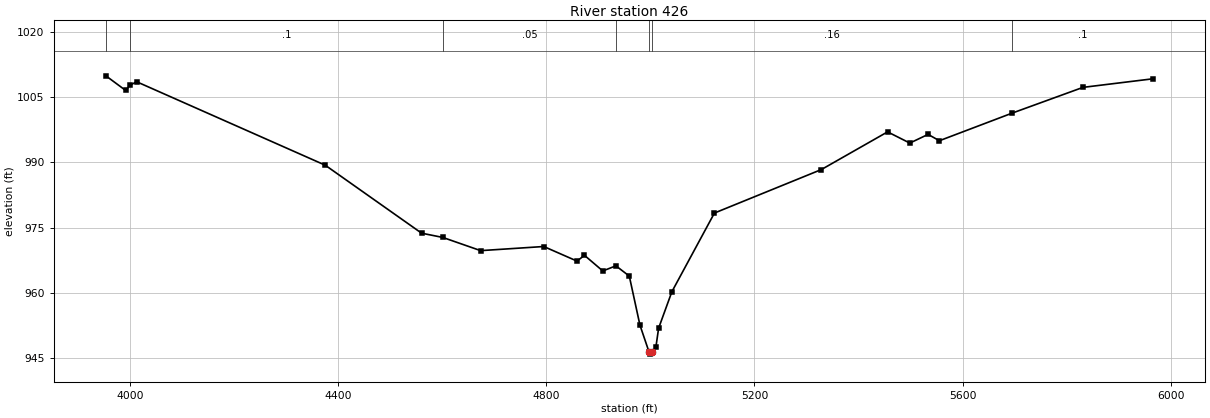
Type RM Length L Ch R = 1,426,0,0,0
BEGIN DESCRIPTION:
UNT 1054 IN LATR 1.0
END DESCRIPTION:
XS GIS Cut Line= 4
      2932359.32     10077918.28      2932973.23     10077171.31
      2932933.92     10076986.85      2932362.91     10076349.37
#Sta/Elev= 30
  3954.3 1009.96  3992.4 1006.58  4000.1 1007.75  4013.3 1008.60  4375.6  989.37
  4560.7  973.71  4601.4  972.73  4674.1  969.69  4795.3  970.64  4859.2  967.28
  4873.5  968.61  4908.7  965.01  4933.9  966.19  4959.6  963.83  4980.0  952.55
  4997.5  946.35  5000.2  945.85  5003.5  946.35  5010.7  947.48  5015.9  951.82
  5041.4  960.23  5123.1  978.35  5328.7  988.38  5455.7  997.05  5498.4  994.47
  5533.5  996.47  5555.2  995.01  5695.4 1001.39  5831.0 1007.30  5965.6 1009.28
#Mann=7,-1,0
  3954.3    0.05       0  4000.1     0.1       0  4601.4    0.05       0
  4933.9    0.16       0  4997.5    0.07       0  5003.5    0.16       0
  5695.4     0.1       0
Bank Sta=4997.5,5003.5
Exp/Cntr=0.3,0.1

Chan Stop Cuts=-1