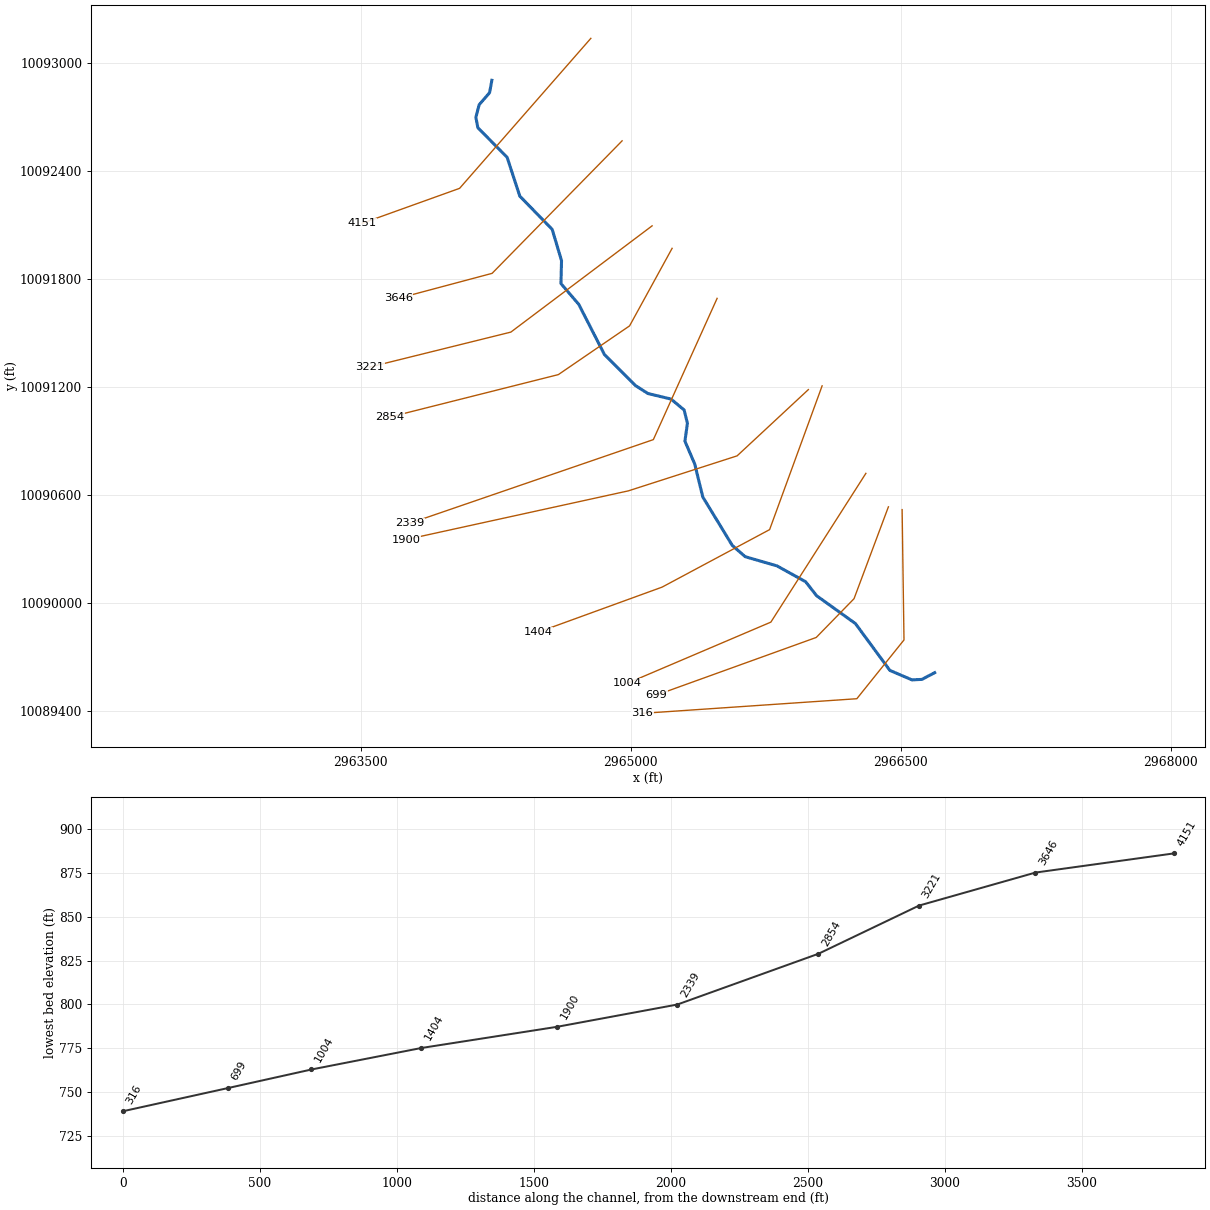
--- UNT 0055 IN LATR.prj (project) ---

Proj Title=UNT 1055 IN LATR Base Level Engineering
Current Plan=p01
Default Exp/Contr=0.3,0.1
English Units
Geom File=g01
Flow File=f01
Plan File=p01
BEGIN DESCRIPTION:
UNT 1055 IN LATR
END DESCRIPTION:

--- UNT 0055 IN LATR.p01 (plan) ---

Plan Title=Multiple Run
Short Identifier=Multiple
Geom File=g01
Flow File=f01
Subcritical Flow
K Sum by GR= 0
Std Step Tol= 0.01
Critical Tol= 0.01
Num of Std Step Trials= 20
Max Error Tol= 0.3
Flow Tol Ratio= 0.001
Split Flow NTrial= 30
Split Flow Tol= 0.02
Split Flow Ratio= 0.02
Log Output Level= 0
Friction Slope Method= 1
Unsteady Friction Slope Method= 2
Unsteady Bridges Friction Slope Method= 1
Parabolic Critical Depth
Global Vel Dist=  1 , 1 , 1
Global Log Level= 0
CheckData=True
Encroach Param= -1, 0, 0, 0
BEGIN DESCRIPTION:
Multiple Run
END DESCRIPTION:

--- UNT 0055 IN LATR.f01 (steady flow) ---

Flow Title=Multiple
Number of Profiles=7
Profile Names=10-year,25-year,50-year,1pct_min,100-year,1pct_plu,500-year
River Rch & RM= UNT 1055 IN LATR,Reach-1,4151
     878    1279    1628    1519    2054    2778    3281
River Rch & RM= UNT 1055 IN LATR,Reach-1,3221
    1196    1776    2291    2165    2928    3960    4798
Boundary for River Rch & Prof#=UNT 1055 IN LATR,Reach-1,1
Up Type=0
Dn Type=3
Dn Slope=0.005
Boundary for River Rch & Prof#=UNT 1055 IN LATR,Reach-1,2
Up Type=0
Dn Type=3
Dn Slope=0.005
Boundary for River Rch & Prof#=UNT 1055 IN LATR,Reach-1,3
Up Type=0
Dn Type=3
Dn Slope=0.005
Boundary for River Rch & Prof#=UNT 1055 IN LATR,Reach-1,4
Up Type=0
Dn Type=3
Dn Slope=0.005
Boundary for River Rch & Prof#=UNT 1055 IN LATR,Reach-1,5
Up Type=0
Dn Type=3
Dn Slope=0.005
Boundary for River Rch & Prof#=UNT 1055 IN LATR,Reach-1,6
Up Type=0
Dn Type=3
Dn Slope=0.005
Boundary for River Rch & Prof#=UNT 1055 IN LATR,Reach-1,7
Up Type=0
Dn Type=3
Dn Slope=0.005

--- UNT 0055 IN LATR.g01 (geometry) ---

Geom Title=Existing Conditions

River Reach=UNT 1055 IN LATR,Reach-1
Reach XY= 30
      2964228.27     10092904.45      2964215.26     10092835.10
      2964157.62     10092768.86      2964139.32     10092698.71
      2964150.53     10092640.95      2964313.01     10092476.21
      2964383.39     10092260.85      2964563.25     10092076.28
      2964615.14     10091902.72      2964612.04     10091775.22
      2964710.78     10091660.06      2964853.51     10091381.04
      2965025.53     10091208.83      2965095.15     10091164.41
      2965223.47     10091133.62      2965296.27     10091072.89
      2965314.56     10090998.87      2965300.65     10090899.78
      2965355.25     10090772.40      2965400.00     10090589.37
      2965563.65     10090320.80      2965635.51     10090258.00
      2965812.36     10090206.74      2965971.04     10090118.86
      2966032.03     10090041.28      2966247.65     10089886.49
      2966439.39     10089626.16      2966562.11     10089573.50
      2966617.23     10089576.39      2966688.47     10089613.73

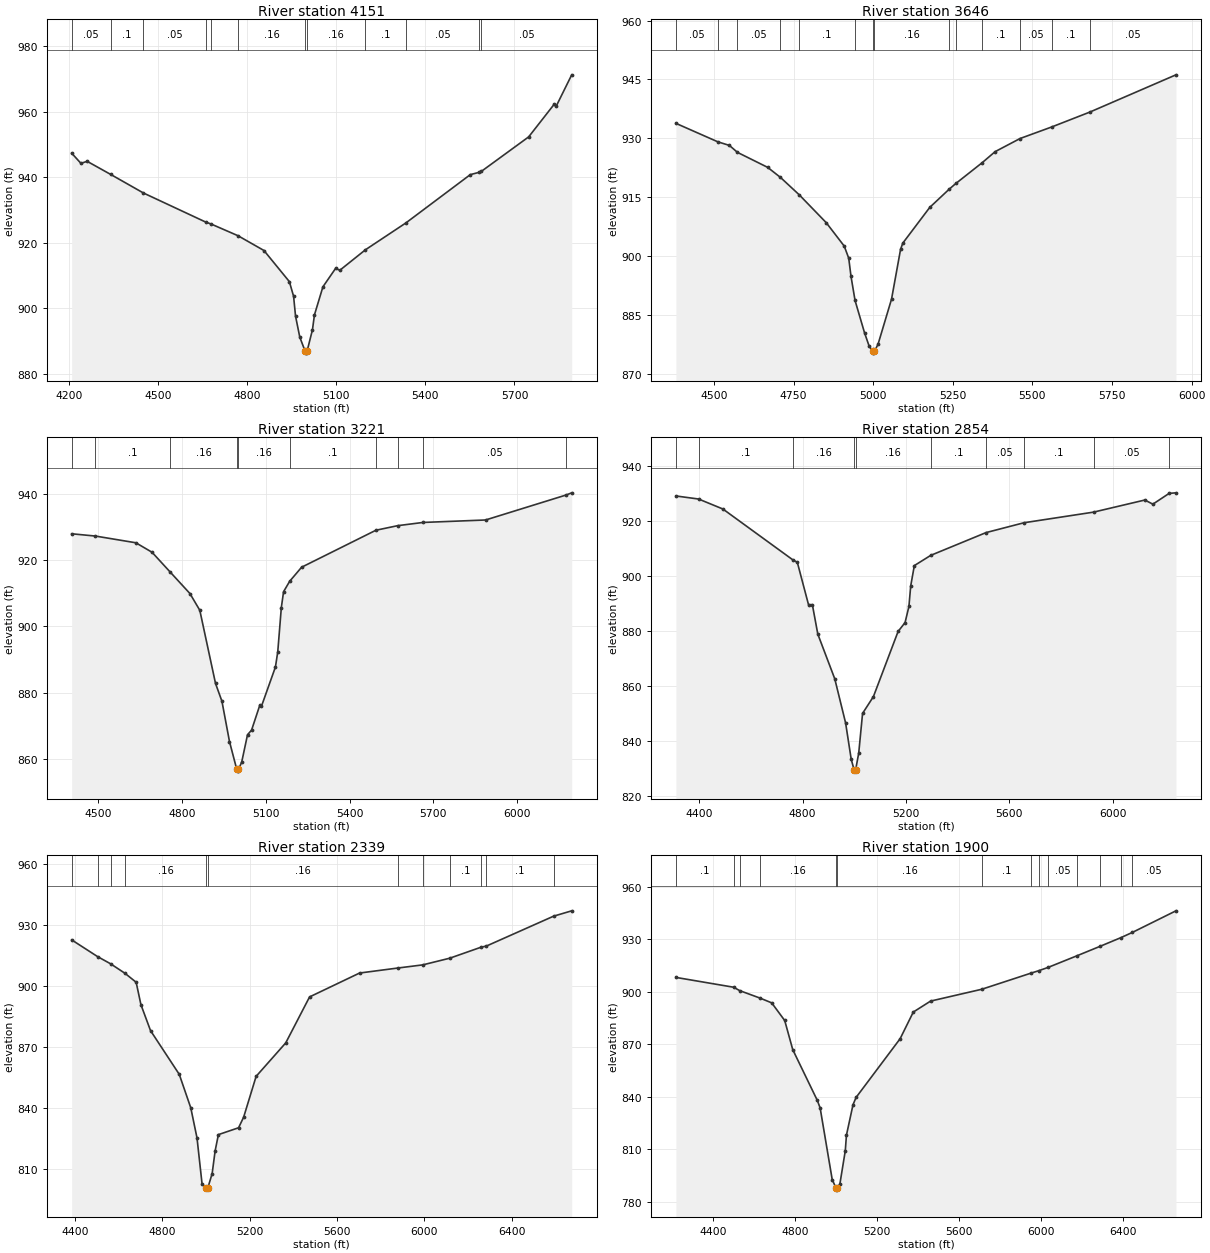
Type RM Length L Ch R = 1,4151,505,505,505
BEGIN DESCRIPTION:
UNT 1055 IN LATR 9.0
END DESCRIPTION:
XS GIS Cut Line= 3
      2964778.06     10093137.52      2964048.90     10092304.19
      2963507.24     10092109.75
#Sta/Elev= 30
  4209.8  947.33  4241.0  944.21  4261.8  944.84  4340.8  940.85  4451.4  935.16
  4660.4  926.31  4679.4  925.68  4769.6  922.12  4856.9  917.61  4942.4  908.11
  4956.6  903.65  4963.2  897.56  4977.5  891.16  4995.8  886.78  4998.6  886.28
  5001.8  886.78  5020.2  893.45  5026.8  897.94  5055.3  906.52  5098.0  912.15
  5112.3  911.58  5198.4  917.83  5334.6  926.03  5551.3  940.77  5580.8  941.47
  5588.0  941.73  5747.8  952.30  5834.6  962.37  5840.0  961.59  5892.6  971.24
#Mann=12,-1,0
  4209.8    0.05       0  4340.8     0.1       0  4451.4    0.05       0
  4660.4     0.1       0  4679.4    0.05       0  4769.6    0.16       0
  4995.8    0.07       0  5001.8    0.16       0  5198.4     0.1       0
  5334.6    0.05       0  5580.8     0.1       0  5588.0    0.05       0
Bank Sta=4995.8,5001.8
Exp/Cntr=0.3,0.1

Type RM Length L Ch R = 1,3646,425,425,425
BEGIN DESCRIPTION:
UNT 1055 IN LATR 8.0
END DESCRIPTION:
XS GIS Cut Line= 3
      2964951.67     10092568.08      2964229.45     10091831.97
      2963708.60     10091693.08
#Sta/Elev= 30
  4380.4  933.83  4511.9  929.13  4548.4  928.21  4573.7  926.44  4668.6  922.62
  4708.8  920.06  4768.0  915.61  4852.4  908.55  4909.0  902.58  4923.1  899.50
  4930.3  894.86  4943.0  888.73  4972.7  880.52  4986.9  877.19  4998.0  875.83
  5000.8  875.33  5004.0  875.83  5015.1  877.57  5057.6  889.09  5085.9  901.74
  5092.9  903.33  5177.7  912.44  5238.5  917.06  5259.7  918.53  5342.8  923.85
  5382.8  926.62  5461.3  929.97  5561.0  932.92  5679.5  936.67  5950.7  946.18
#Mann=14,-1,0
  4380.4    0.05       0  4511.9     0.1       0  4573.7    0.05       0
  4708.8    0.16       0  4768.0     0.1       0  4943.0    0.16       0
  4998.0    0.07       0  5004.0    0.16       0  5238.5     0.1       0
  5259.7    0.05       0  5342.8     0.1       0  5461.3    0.05       0
  5561.0     0.1       0  5679.5    0.05       0
Bank Sta=4998,5004
Exp/Cntr=0.3,0.1

Type RM Length L Ch R = 1,3221,367,367,367
BEGIN DESCRIPTION:
UNT 1055 IN LATR 7.0
END DESCRIPTION:
XS GIS Cut Line= 3
      2965118.38     10092095.89      2964333.62     10091505.58
      2963548.94     10091311.15
#Sta/Elev= 30
  4404.8  927.92  4490.0  927.23  4634.6  925.21  4692.5  922.36  4758.6  916.30
  4828.2  909.93  4863.6  904.88  4919.9  882.84  4942.8  877.50  4969.9  865.35
  4996.0  856.95  4998.8  856.45  5002.0  856.95  5013.6  859.17  5034.4  867.40
  5049.0  868.81  5078.1  876.22  5084.4  875.99  5134.4  887.81  5142.7  892.37
  5155.5  905.71  5163.5  910.48  5185.4  913.62  5228.1  917.85  5494.0  928.98
  5572.0  930.36  5662.6  931.33  5886.6  932.07  6175.4  939.60  6195.2  940.25
#Mann=10,-1,0
  4404.8    0.05       0  4490.0     0.1       0  4758.6    0.16       0
  4996.0    0.07       0  5002.0    0.16       0  5185.4     0.1       0
  5494.0    0.05       0  5572.0     0.1       0  5662.6    0.05       0
  6175.4     0.1       0
Bank Sta=4996,5002
Exp/Cntr=0.3,0.1

Type RM Length L Ch R = 1,2854,515,515,515
BEGIN DESCRIPTION:
UNT 1055 IN LATR 6.0
END DESCRIPTION:
XS GIS Cut Line= 4
      2965229.47     10091970.89      2964993.34     10091540.31
      2964597.51     10091269.47      2963661.73     10091033.79
#Sta/Elev= 30
  4309.6  929.11  4397.5  927.99  4491.5  924.36  4763.0  905.79  4779.6  904.95
  4823.0  889.50  4837.9  889.51  4858.9  878.81  4924.6  862.51  4966.5  846.47
  4988.3  833.19  4999.4  829.41  5002.1  828.91  5005.4  829.41  5017.3  835.47
  5032.2  849.93  5074.2  856.05  5169.7  879.76  5196.7  883.01  5211.6  888.86
  5218.6  896.39  5232.6  903.75  5296.1  907.48  5510.2  915.77  5656.8  919.35
  5926.3  923.22  6124.9  927.63  6155.9  926.12  6219.0  930.05  6245.3  930.25
#Mann=10,-1,0
  4309.6    0.05       0  4397.5     0.1       0  4763.0    0.16       0
  4999.4    0.07       0  5005.4    0.16       0  5296.1     0.1       0
  5510.2    0.05       0  5656.8     0.1       0  5926.3    0.05       0
  6219.0    0.16       0
Bank Sta=4999.4,5005.4
Exp/Cntr=0.3,0.1

Type RM Length L Ch R = 1,2339,439,439,439
BEGIN DESCRIPTION:
UNT 1055 IN LATR 5.0
END DESCRIPTION:
XS GIS Cut Line= 3
      2965479.44     10091693.05      2965125.29     10090908.36
      2963772.33     10090443.50
#Sta/Elev= 30
  4384.3  922.49  4503.7  914.22  4562.9  910.71  4628.7  906.04  4679.8  901.64
  4701.7  890.61  4745.6  877.87  4877.3  856.35  4930.1  839.88  4958.7  825.05
  4981.9  802.38  5002.0  800.38  5004.7  799.88  5008.0  800.38  5028.1  807.55
  5041.8  818.75  5056.7  826.69  5149.2  830.07  5172.4  835.28  5229.6  855.36
  5365.3  871.82  5474.5  894.43  5703.7  906.18  5880.2  908.66  5993.1  910.19
  6117.0  913.48  6260.7  918.90  6284.5  919.43  6593.0  934.16  6675.8  936.78
#Mann=12,-1,0
  4384.3     0.1       0  4503.7    0.16       0  4562.9     0.1       0
  4628.7    0.16       0  5002.0    0.07       0  5008.0    0.16       0
  5880.2     0.1       0  5993.1    0.16       0  6117.0     0.1       0
  6260.7    0.05       0  6284.5     0.1       0  6593.0    0.05       0
Bank Sta=5002,5008
Exp/Cntr=0.3,0.1

Type RM Length L Ch R = 1,1900,496,496,496
BEGIN DESCRIPTION:
UNT 1055 IN LATR 4.0
END DESCRIPTION:
XS GIS Cut Line= 4
      2965986.37     10091186.12      2965590.56     10090818.08
      2964986.40     10090623.64      2963751.84     10090353.15
#Sta/Elev= 30
  4218.4  908.16  4500.4  902.54  4529.4  900.61  4629.6  896.30  4685.6  893.62
  4749.1  883.53  4788.4  866.85  4908.2  837.84  4921.9  833.56  4980.8  792.61
  4999.7  787.64  5002.4  787.14  5005.7  787.64  5018.2  790.05  5044.7  809.15
  5050.2  817.96  5082.3  835.40  5097.2  839.55  5312.1  873.12  5376.3  888.36
  5460.6  894.62  5710.0  901.38  5951.1  910.63  5988.7  912.01  6034.7  913.92
  6176.4  920.61  6289.0  926.01  6389.1  930.90  6444.6  933.87  6657.4  946.22
#Mann=14,-1,0
  4218.4     0.1       0  4500.4    0.16       0  4529.4     0.1       0
  4629.6    0.16       0  4999.7    0.07       0  5005.7    0.16       0
  5710.0     0.1       0  5951.1    0.05       0  5988.7    0.16       0
  6034.7    0.05       0  6176.4     0.1       0  6289.0    0.05       0
  6389.1     0.1       0  6444.6    0.05       0
Bank Sta=4999.7,5005.7
Exp/Cntr=0.3,0.1

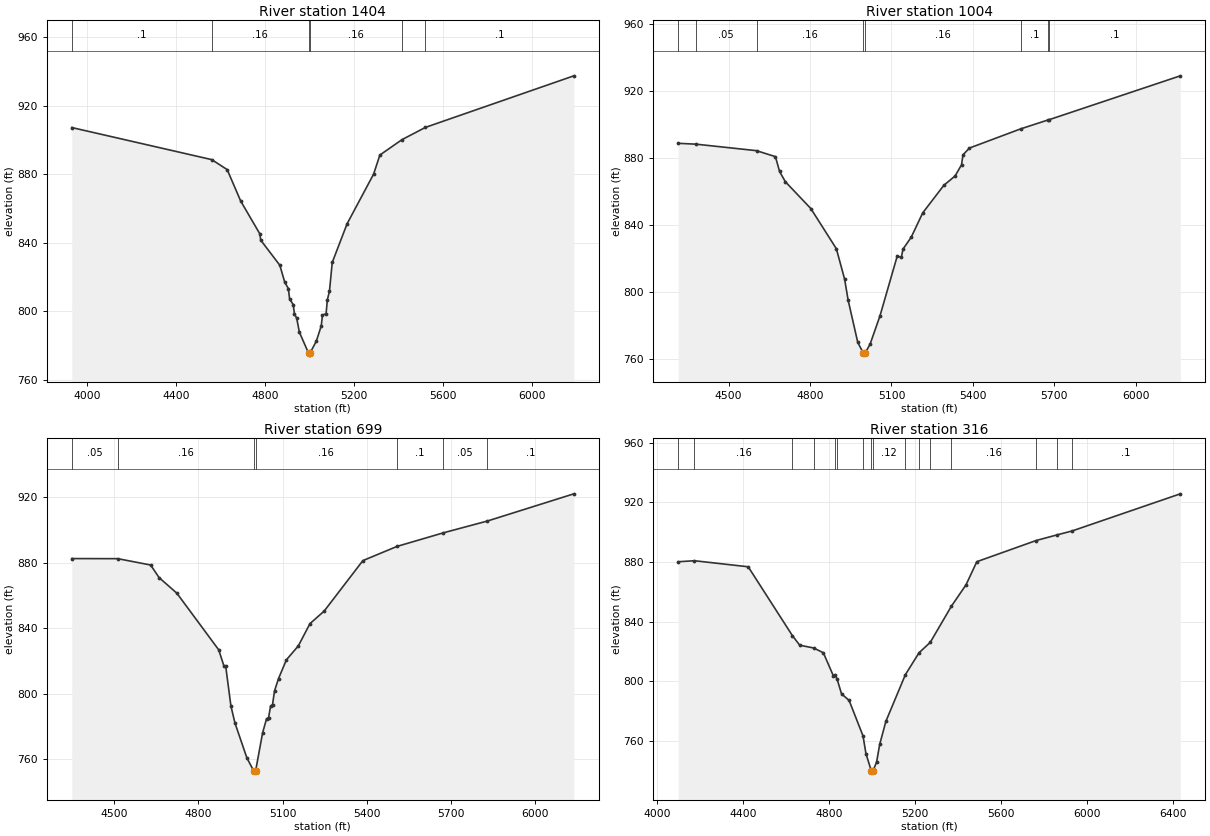
Type RM Length L Ch R = 1,1404,400,400,400
BEGIN DESCRIPTION:
UNT 1055 IN LATR 3.0
END DESCRIPTION:
XS GIS Cut Line= 4
      2966062.80     10091207.01      2965771.12     10090408.36
      2965173.90     10090088.92      2964486.38     10089838.91
#Sta/Elev= 30
  3931.3  907.25  4561.2  888.52  4630.5  882.70  4691.6  864.29  4777.9  845.12
  4781.4  841.54  4867.6  826.87  4889.5  817.00  4905.8  813.30  4911.5  807.16
  4927.7  803.94  4933.4  798.40  4943.3  796.02  4955.4  787.82  4997.0  775.51
  4999.8  775.01  5003.0  775.51  5031.8  782.63  5053.7  791.41  5059.4  797.82
  5075.7  798.61  5081.3  806.73  5090.8  811.72  5103.3  828.50  5170.1  851.08
  5289.4  880.06  5317.6  891.20  5416.9  900.17  5522.6  907.34  6190.4  937.43
#Mann=6,-1,0
  3931.3     0.1       0  4561.2    0.16       0  4997.0    0.07       0
  5003.0    0.16       0  5416.9    0.05       0  5522.6     0.1       0
Bank Sta=4997,5003
Exp/Cntr=0.3,0.1

Type RM Length L Ch R = 1,1004,305,305,305
BEGIN DESCRIPTION:
UNT 1055 IN LATR 2.0
END DESCRIPTION:
XS GIS Cut Line= 3
      2966305.82     10090720.83      2965778.06     10089894.47
      2964979.45     10089554.19
#Sta/Elev= 30
  4314.9  888.85  4380.5  888.34  4603.1  884.45  4672.8  880.87  4688.0  872.00
  4709.2  865.89  4803.1  849.83  4897.0  825.82  4927.5  807.61  4940.3  795.17
  4975.9  769.76  4996.7  763.25  4999.4  762.75  5002.7  763.25  5021.4  768.75
  5057.7  785.65  5121.2  821.38  5136.4  820.68  5142.4  825.56  5172.8  832.70
  5215.1  847.25  5292.9  863.74  5334.3  869.32  5357.9  876.00  5363.4  881.98
  5387.0  886.01  5575.2  897.46  5677.1  902.85  5680.5  902.98  6163.5  929.22
#Mann=8,-1,0
  4314.9     0.1       0  4380.5    0.05       0  4603.1    0.16       0
  4996.7    0.07       0  5002.7    0.16       0  5575.2     0.1       0
  5677.1    0.05       0  5680.5     0.1       0
Bank Sta=4996.7,5002.7
Exp/Cntr=0.3,0.1

Type RM Length L Ch R = 1,699,383,383,383
BEGIN DESCRIPTION:
Mapping XS 9626476b
END DESCRIPTION:
XS GIS Cut Line= 4
      2966431.05     10090534.97      2966240.06     10090024.51
      2966029.99     10089809.23      2965140.28     10089488.38
#Sta/Elev= 30
  4348.0  882.66  4512.4  882.60  4629.4  878.72  4659.7  871.01  4723.0  861.50
  4872.5  826.84  4890.8  817.08  4897.1  817.08  4915.9  792.56  4930.1  782.26
  4972.5  760.99  4997.8  752.62  5000.5  752.12  5003.8  752.62  5029.1  776.26
  5043.2  784.79  5050.2  785.40  5057.4  792.42  5064.4  793.41  5071.5  801.75
  5085.7  809.29  5114.0  820.80  5156.4  829.27  5198.0  842.90  5248.6  850.55
  5386.8  881.42  5508.8  890.11  5673.1  898.36  5831.4  905.63  6139.6  922.24
#Mann=7,-1,0
  4348.0    0.05       0  4512.4    0.16       0  4997.8    0.07       0
  5003.8    0.16       0  5508.8     0.1       0  5673.1    0.05       0
  5831.4     0.1       0
Bank Sta=4997.8,5003.8
Exp/Cntr=0.3,0.1

Type RM Length L Ch R = 1,316,0,0,0
BEGIN DESCRIPTION:
UNT 1055 IN LATR 1.0
END DESCRIPTION:
XS GIS Cut Line= 4
      2966507.23     10090519.46      2966517.65     10089795.51
      2966255.69     10089468.96      2965063.13     10089387.55
#Sta/Elev= 30
  4098.0  880.12  4173.2  880.81  4423.8  876.75  4630.0  830.44  4663.8  824.08
  4728.3  822.25  4773.8  819.02  4820.4  803.54  4828.1  804.38  4838.1  801.15
  4858.5  791.42  4893.7  787.02  4958.5  763.20  4972.1  751.27  4997.9  739.38
  5000.7  738.88  5003.9  739.38  5021.7  745.61  5036.2  757.55  5065.0  773.00
  5155.9  804.37  5219.5  819.05  5271.5  825.99  5370.1  850.30  5438.3  864.68
  5488.5  880.17  5764.6  894.38  5863.2  898.21  5931.7  900.78  6436.0  925.73
#Mann=16,-1,0
  4098.0    0.05       0  4173.2    0.16       0  4630.0    0.05       0
  4728.3     0.1       0  4828.1    0.05       0  4838.1     0.1       0
  4958.5    0.12       0  4997.9    0.07       0  5003.9    0.12       0
  5155.9    0.16       0  5219.5     0.1       0  5271.5    0.05       0
  5370.1    0.16       0  5764.6     0.1       0  5863.2    0.05       0
  5931.7     0.1       0
Bank Sta=4997.9,5003.9
Exp/Cntr=0.3,0.1

Chan Stop Cuts=-1