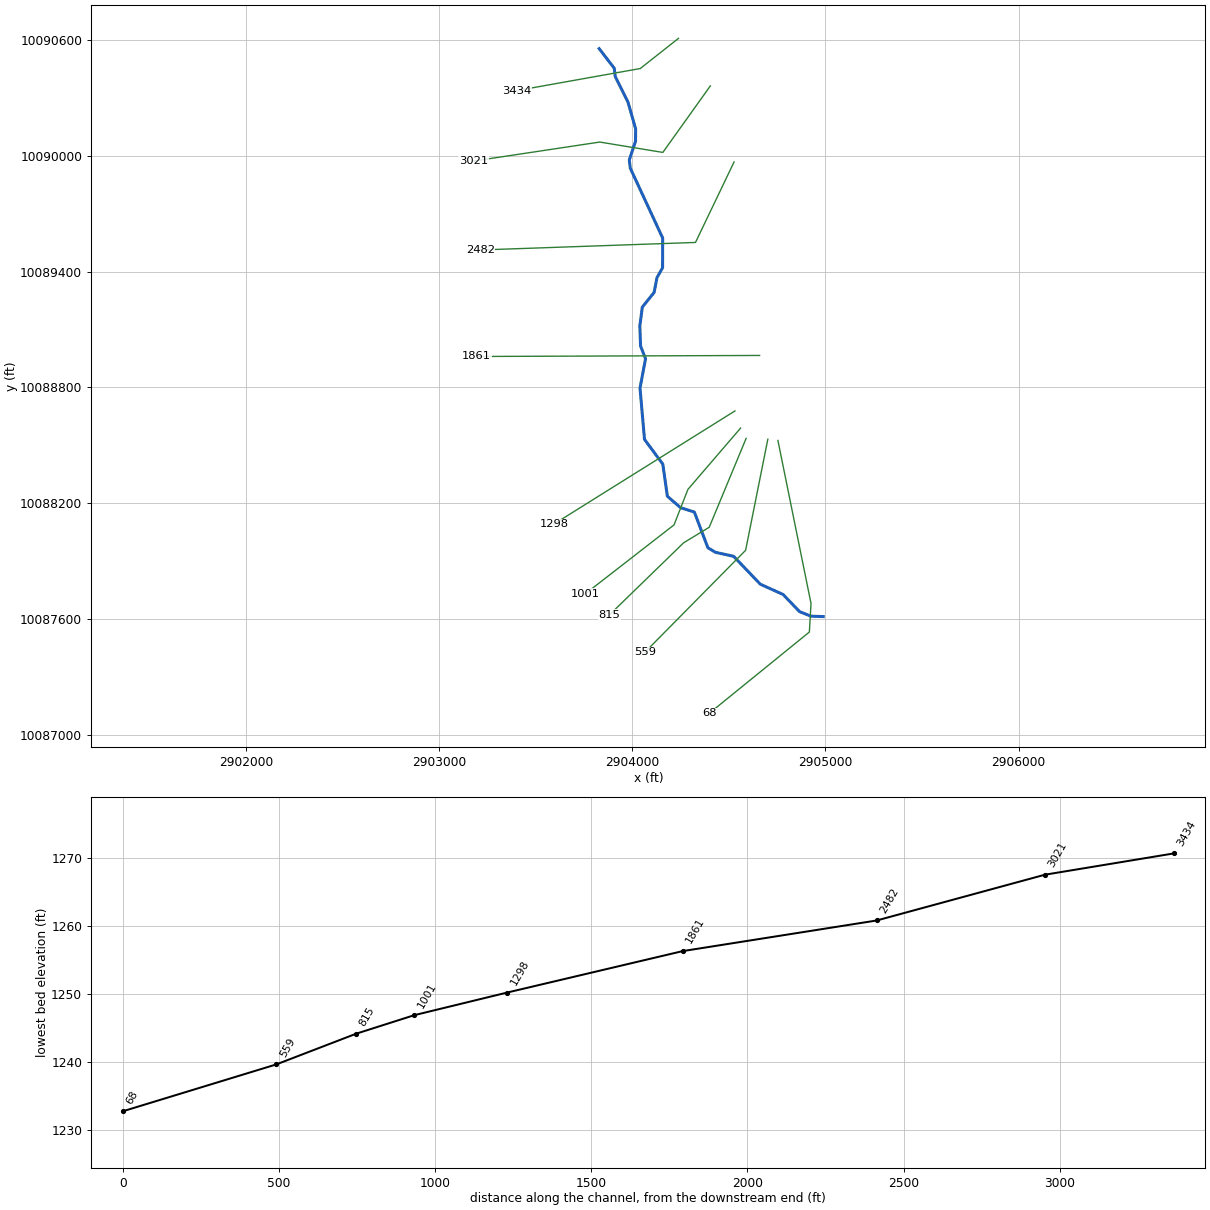
--- UNT 0057 IN LATR.prj (project) ---

Proj Title=UNT 1057 IN LATR Base Level Engineering
Current Plan=p01
Default Exp/Contr=0.3,0.1
English Units
Geom File=g01
Flow File=f01
Plan File=p01
Y Axis Title=Elevation
X Axis Title(PF)=Main Channel Distance
X Axis Title(XS)=Station
BEGIN DESCRIPTION:
UNT 1057 IN LATR
END DESCRIPTION:
DSS Export Rating Curves= 0
DSS Export Rating Curve Sorted= 0
DSS Export Volume Flow Curves= 0
DXF OffsetX= 0
DXF OffsetY= 0
DXF ScaleX= 1
DXF ScaleY= 10

--- UNT 0057 IN LATR.p01 (plan) ---

Plan Title=Multiple Run
Short Identifier=Multiple
Geom File=g01
Flow File=f01
Subcritical Flow
K Sum by GR= 0
Std Step Tol= 0.01
Critical Tol= 0.01
Num of Std Step Trials= 20
Max Error Tol= 0.3
Flow Tol Ratio= 0.001
Split Flow NTrial= 30
Split Flow Tol= 0.02
Split Flow Ratio= 0.02
Log Output Level= 0
Friction Slope Method= 1
Unsteady Friction Slope Method= 2
Unsteady Bridges Friction Slope Method= 1
Parabolic Critical Depth
Global Vel Dist=  1 , 1 , 1
Global Log Level= 0
CheckData=True
Encroach Param= -1, 0, 0, 0
BEGIN DESCRIPTION:
Multiple Run
END DESCRIPTION:

--- UNT 0057 IN LATR.f01 (steady flow) ---

Flow Title=Multiple
Number of Profiles=7
Profile Names=10-year,25-year,50-year,1pct_min,100-year,1pct_plu,500-year
River Rch & RM= UNT 1057 IN LATR,Reach-1,3434
     820    1182    1495    1384    1872    2532    2946
River Rch & RM= UNT 1057 IN LATR,Reach-1,3021
     950    1378    1750    1626    2199    2974    3485
Boundary for River Rch & Prof#=UNT 1057 IN LATR,Reach-1,1
Up Type=0
Dn Type=3
Dn Slope=0.005
Boundary for River Rch & Prof#=UNT 1057 IN LATR,Reach-1,2
Up Type=0
Dn Type=3
Dn Slope=0.005
Boundary for River Rch & Prof#=UNT 1057 IN LATR,Reach-1,3
Up Type=0
Dn Type=3
Dn Slope=0.005
Boundary for River Rch & Prof#=UNT 1057 IN LATR,Reach-1,4
Up Type=0
Dn Type=3
Dn Slope=0.005
Boundary for River Rch & Prof#=UNT 1057 IN LATR,Reach-1,5
Up Type=0
Dn Type=3
Dn Slope=0.005
Boundary for River Rch & Prof#=UNT 1057 IN LATR,Reach-1,6
Up Type=0
Dn Type=3
Dn Slope=0.005
Boundary for River Rch & Prof#=UNT 1057 IN LATR,Reach-1,7
Up Type=0
Dn Type=3
Dn Slope=0.005

--- UNT 0057 IN LATR.g01 (geometry) ---

Geom Title=Existing Conditions
Program Version=4.10

River Reach=UNT 1057 IN LATR,Reach-1
Reach XY= 30
      2903828.47     10090553.73      2903906.63     10090452.22
      2903911.83     10090409.15      2903977.23     10090278.22
      2904017.29     10090138.78      2904016.85      10090074.6
      2903984.56      10089977.4       2903989.5     10089935.25
      2904157.33     10089573.26      2904156.75      10089419.2
      2904127.81     10089368.54      2904112.85     10089291.46
      2904051.91      10089215.6      2904039.12     10089118.28
       2904042.8     10089014.53      2904068.64     10088948.71
      2904039.96     10088796.31      2904063.33     10088530.85
      2904157.97     10088402.82      2904181.56     10088236.78
      2904250.04     10088177.24      2904321.24     10088154.95
      2904391.37     10087970.08      2904429.57      10087946.7
      2904524.63     10087925.71      2904662.62      10087781.5
      2904780.65     10087728.12      2904865.87     10087639.44
      2904924.41     10087615.82      2904988.47     10087613.73

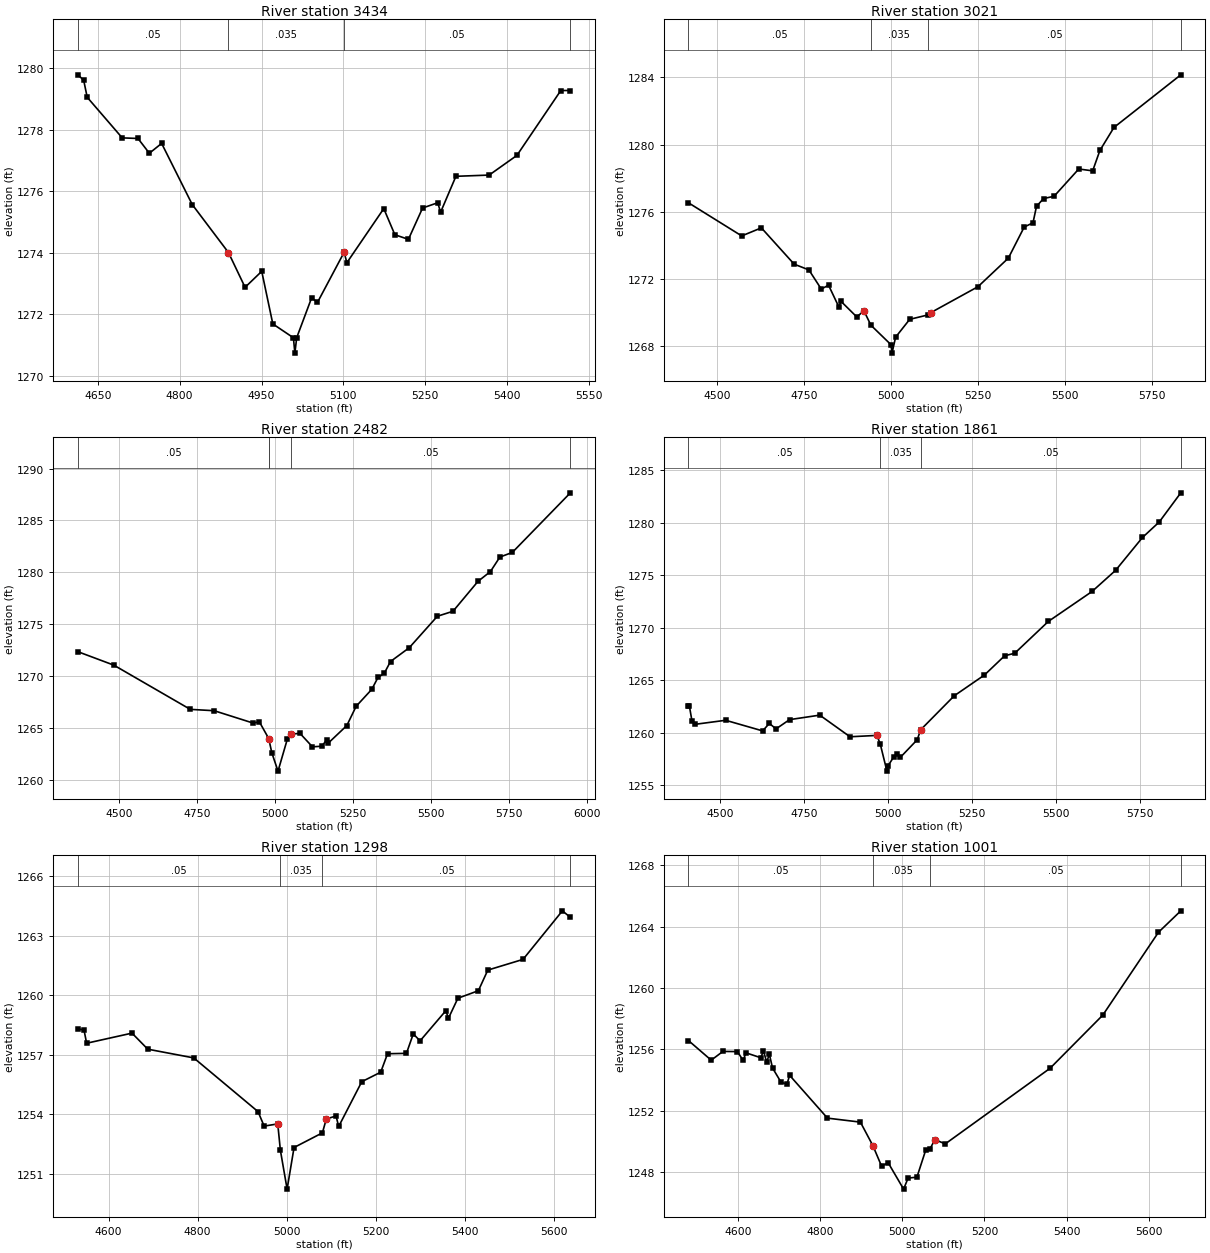
Type RM Length L Ch R = 1 ,3434    ,413,413,413
BEGIN DESCRIPTION:
UNT 1057 IN LATR 10.0
END DESCRIPTION:
XS GIS Cut Line= 3
      2904239.32       10090607.      2904041.39     10090450.75
      2903402.11      10090336.4
#Sta/Elev= 30
    4614 1279.79  4624.4 1279.61  4630.8 1279.06  4694.9 1277.74  4723.8 1277.72
  4744.6 1277.24  4767.1 1277.56  4823.2 1275.57  4889.5 1274.01  4919.9 1272.88
  4950.4  1273.4  4970.7 1271.69  5008.4 1271.24  5011.1 1270.74  5014.4 1271.24
  5041.8 1272.54  5052.5 1272.39  5101.3 1274.02  5106.3 1273.68  5173.9 1275.44
  5194.2 1274.59    5219 1274.44    5245 1275.46  5272.8 1275.63  5277.9 1275.32
    5306 1276.49  5366.9 1276.53  5417.7 1277.17  5498.1 1279.28  5515.6 1279.28
#Mann= 4 ,-1 , 0
    4614     .05       0  4889.5    .035       0  5101.3     .05       0
  5515.6      .1       0
Bank Sta=4889.5,5101.3
XS Rating Curve= 0 ,0
Exp/Cntr=0.3,0.1

Type RM Length L Ch R = 1 ,3021    ,539,539,539
BEGIN DESCRIPTION:
Mapping XS 942f05c1
END DESCRIPTION:
XS GIS Cut Line= 4
      2904404.11     10090360.87      2904158.08     10090016.43
      2903831.55     10090070.11      2903178.52      10089971.7
#Sta/Elev= 30
  4417.1 1276.54  4570.1 1274.57  4626.6 1275.05  4720.8 1272.89  4763.1 1272.55
  4798.7 1271.41  4819.6 1271.64  4849.8 1270.32  4854.9 1270.69  4900.8 1269.75
  4921.2 1270.12  4941.3 1269.26  4999.1  1268.1  5001.9  1267.6  5012.3 1268.55
  5052.8 1269.61  5104.9 1269.87  5113.6 1270.01  5248.9 1271.55  5336.2 1273.25
  5381.8  1275.1    5407 1275.35  5417.1 1276.33  5437.3 1276.79  5467.7 1276.93
  5538.5 1278.55  5578.5 1278.44  5599.2 1279.65  5639.6 1281.02  5831.7 1284.15
#Mann= 4 ,-1 , 0
  4417.1     .05       0  4941.3    .035       0  5104.9     .05       0
  5831.7     .05       0
Bank Sta=4921.2,5113.6
XS Rating Curve= 0 ,0
Exp/Cntr=0.3,0.1

Type RM Length L Ch R = 1 ,2482    ,621,621,621
BEGIN DESCRIPTION:
Mapping XS f82c286d
END DESCRIPTION:
XS GIS Cut Line= 3
      2904526.91     10089967.13      2904327.26     10089550.46
      2903212.67     10089511.43
#Sta/Elev= 30
  4368.3 1272.35    4483 1271.06  4727.9  1266.8  4804.5 1266.67  4929.2 1265.48
  4949.2  1265.6  4979.2 1263.99  4989.2 1262.61    5009 1260.85  5039.2 1263.97
  5049.3 1264.41  5079.3 1264.49  5119.3 1263.19  5149.3 1263.25  5164.9 1263.86
    5170 1263.55  5229.4 1265.24  5259.4  1267.1  5309.4 1268.73  5329.4 1269.88
  5349.4 1270.28  5369.4 1271.41  5429.5 1272.74  5519.5 1275.77  5569.6 1276.25
  5649.6 1279.13  5689.6 1280.08  5719.7 1281.47  5759.7 1281.92  5945.6 1287.66
#Mann= 5 ,-1 , 0
  4368.3     .05       0  4979.2      .1       0  4979.2    .035       0
  5049.3     .05       0  5945.6     .05       0
Bank Sta=4979.2,5049.3
XS Rating Curve= 0 ,0
Exp/Cntr=0.3,0.1

Type RM Length L Ch R = 1 ,1861    ,563,563,563
BEGIN DESCRIPTION:
Mapping XS 0a753fca
END DESCRIPTION:
XS GIS Cut Line= 2
      2904659.07     10088965.45      2903194.48     10088960.19
#Sta/Elev= 30
  4407.1 1262.52  4409.9 1262.52  4417.7 1261.09  4427.7  1260.8  4517.7 1261.18
  4627.7 1260.17  4647.7 1260.88  4667.7 1260.36  4707.7 1261.24  4797.7 1261.67
  4887.7 1259.61  4967.7 1259.74  4977.7 1258.91  4997.5 1256.34  5000.7 1256.84
  5017.7 1257.69  5027.7 1257.96  5037.7 1257.66  5087.7 1259.33  5097.7 1260.27
  5197.7 1263.51  5287.7 1265.49  5347.7 1267.32  5377.7 1267.56  5477.7 1270.59
  5607.7 1273.44  5677.7 1275.45  5757.7 1278.58  5807.7 1280.06  5871.7 1282.83
#Mann= 4 ,-1 , 0
  4407.1     .05       0  4977.7    .035       0  5097.7     .05       0
  5871.7     .16       0
Bank Sta=4967.7,5097.7
XS Rating Curve= 0 ,0
Exp/Cntr=0.3,0.1

Type RM Length L Ch R = 1 ,1298    ,297,297,297
BEGIN DESCRIPTION:
Mapping XS e55d19e0
END DESCRIPTION:
XS GIS Cut Line= 2
      2904531.26     10088678.07      2903593.71     10088092.11
#Sta/Elev= 30
  4531.5  1258.3  4544.9 1258.25  4550.8 1257.58  4652.7 1258.09  4688.1 1257.28
  4791.4 1256.84  4935.7 1254.13  4949.4  1253.4    4980 1253.51  4985.9 1252.18
    5001 1250.22  5016.6 1252.32  5080.3 1253.06    5089 1253.76  5110.9 1253.91
  5116.8 1253.38  5168.7 1255.64  5211.2 1256.12  5226.5 1257.05    5269 1257.07
  5284.3 1258.05  5299.6  1257.7  5357.4 1259.22  5363.3 1258.84  5384.5 1259.85
  5430.5 1260.23  5451.7 1261.27  5530.8 1261.81  5619.2 1264.26  5637.1 1263.93
#Mann= 4 ,-1 , 0
  4531.5     .05       0  4985.9    .035       0  5080.3     .05       0
  5637.1      .1       0
Bank Sta=4980,5089
XS Rating Curve= 0 ,0
Exp/Cntr=0.3,0.1

Type RM Length L Ch R = 1 ,1001    ,186,186,186
BEGIN DESCRIPTION:
Mapping XS e7c964bf
END DESCRIPTION:
XS GIS Cut Line= 4
      2904560.65     10088589.51       2904287.8     10088271.93
      2904216.23     10088088.53      2903755.53     10087730.71
#Sta/Elev= 30
  4479.4 1256.58  4534.8  1255.3  4563.3 1255.87  4598.5 1255.86  4612.7 1255.28
  4619.3 1255.78  4655.5 1255.46  4662.1 1255.91  4669.8 1255.17  4676.4 1255.69
  4684.1 1254.79  4704.9 1253.86  4719.2 1253.74  4725.8 1254.31  4817.9 1251.52
  4898.1 1251.26  4928.4 1249.73  4949.8 1248.38  4965.5 1248.62  5003.3 1246.89
  5014.2 1247.61  5035.7 1247.67  5057.2 1249.44  5067.9 1249.53  5079.5 1250.12
  5104.7 1249.84  5359.9 1254.77  5488.4 1258.24  5623.9 1263.64  5678.3 1265.04
#Mann= 4 ,-1 , 0
  4479.4     .05       0  4928.4    .035       0  5067.9     .05       0
  5678.3      .1       0
Bank Sta=4928.4,5079.5
XS Rating Curve= 0 ,0
Exp/Cntr=0.3,0.1

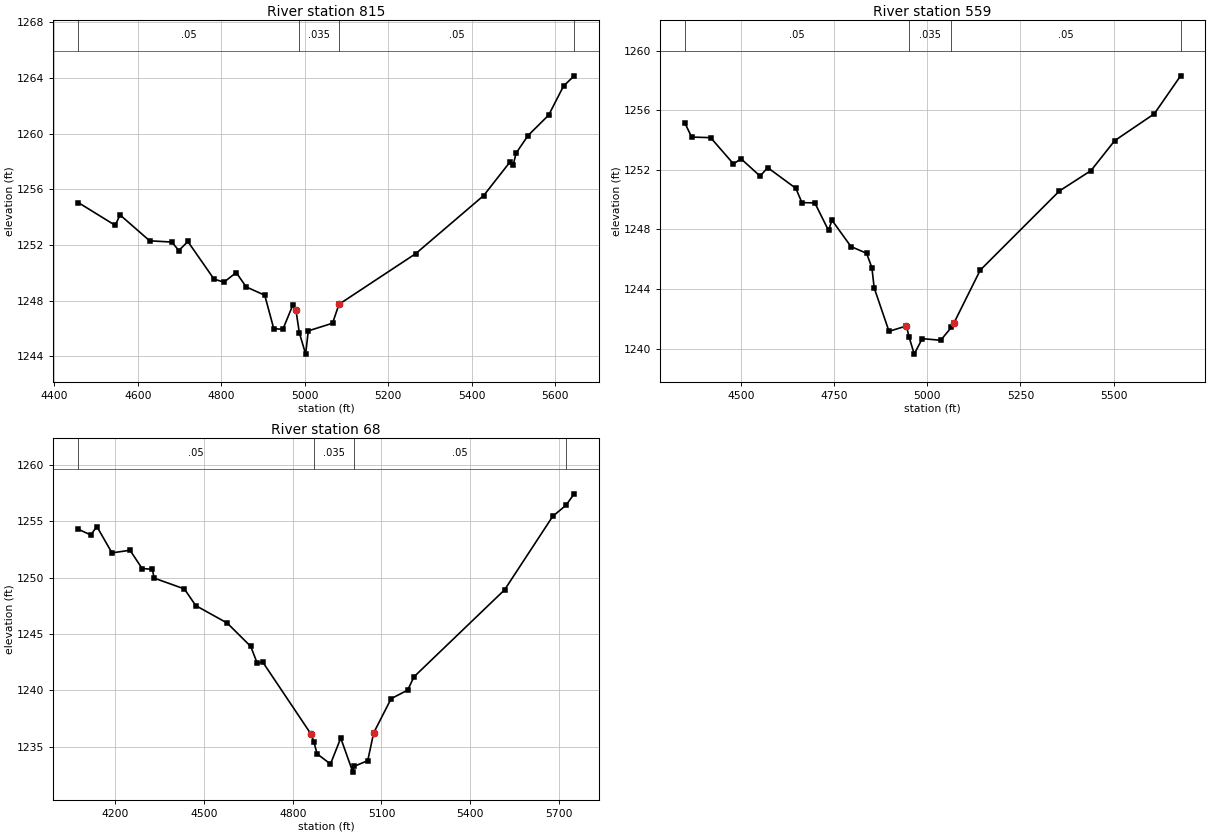
Type RM Length L Ch R = 1 ,815     ,256,256,256
BEGIN DESCRIPTION:
Mapping XS 4f2fcb02
END DESCRIPTION:
XS GIS Cut Line= 4
      2904589.27      10088536.2      2904398.29     10088076.11
      2904265.91     10087995.82      2903882.64     10087623.38
#Sta/Elev= 30
  4457.5 1255.05  4546.1 1253.41  4557.6 1254.16  4628.6  1252.3  4681.7 1252.21
  4698.4  1251.6    4720 1252.25  4782.6 1249.55  4806.5 1249.33  4835.8 1250.02
  4859.6 1248.99  4904.1 1248.39  4925.7 1245.99  4947.5 1245.94  4971.4 1247.69
  4978.8 1247.32  4986.9  1245.7    5002 1244.16  5008.3 1245.83  5066.4 1246.38
  5081.9 1247.74  5265.7 1251.38  5428.3 1255.55    5492 1257.99    5499 1257.77
  5506.2 1258.61  5534.5 1259.86  5583.9 1261.33  5619.4 1263.41  5644.9 1264.15
#Mann= 4 ,-1 , 0
  4457.5     .05       0  4986.9    .035       0  5081.9     .05       0
  5644.9      .1       0
Bank Sta=4978.8,5081.9
XS Rating Curve= 0 ,0
Exp/Cntr=0.3,0.1

Type RM Length L Ch R = 1 ,559     ,491,491,491
BEGIN DESCRIPTION:
Mapping XS ac96298e
END DESCRIPTION:
XS GIS Cut Line= 3
      2904701.72     10088531.99       2904586.7     10087956.89
      2904064.36     10087428.05
#Sta/Elev= 30
  4349.6 1255.17  4368.2  1254.2  4419.2 1254.16  4480.4  1252.4  4500.8 1252.74
  4551.8 1251.58  4572.2 1252.15  4647.6 1250.76    4664  1249.8  4698.6 1249.78
  4735.3 1247.93  4744.5 1248.62  4795.5 1246.85  4837.3  1246.4  4851.6 1245.43
  4857.7 1244.08  4897.5 1241.16  4944.1 1241.52  4951.2 1240.79  4965.1 1239.63
  4986.5 1240.67  5036.1 1240.56  5064.4 1241.42  5071.4 1241.71  5142.1 1245.27
  5354.3 1250.58  5439.1 1251.95  5502.7 1253.96  5608.8 1255.76  5679.4 1258.31
#Mann= 4 ,-1 , 0
  4349.6     .05       0  4951.2    .035       0  5064.4     .05       0
  5679.4     .16       0
Bank Sta=4944.1,5071.4
XS Rating Curve= 0 ,0
Exp/Cntr=0.3,0.1

Type RM Length L Ch R = 1 ,68      ,0,0,0
BEGIN DESCRIPTION:
UNT 1057 IN LATR 1.0
END DESCRIPTION:
XS GIS Cut Line= 4
      2904753.79     10088525.51      2904925.24     10087681.28
      2904916.56     10087533.71       2904397.9     10087112.71
#Sta/Elev= 30
  4074.4 1254.29    4117 1253.78  4137.4 1254.53  4188.5 1252.19  4249.7 1252.42
  4290.5  1250.8  4325.1 1250.73  4331.3 1249.95  4433.4 1248.99  4471.9 1247.51
  4578.3 1245.96  4657.8 1243.89  4679.5 1242.42  4698.7 1242.49  4861.9  1236.1
  4871.9 1235.37  4882.3 1234.35  4927.6 1233.45  4962.3 1235.75  5003.3 1232.73
  5006.5 1233.23  5053.6 1233.75  5073.6 1236.21  5132.7 1239.25  5188.7 1240.01
    5210 1241.19  5516.4 1248.91  5679.4 1255.44  5724.3 1256.42  5751.7 1257.43
#Mann= 4 ,-1 , 0
  4074.4     .05       0  4871.9    .035       0  5006.5     .05       0
  5724.3      .1       0
Bank Sta=4861.9,5073.6
XS Rating Curve= 0 ,0
Exp/Cntr=0.3,0.1

Chan Stop Cuts=-1
Use User Specified Reach Order=0
Composite Channel Slope=5