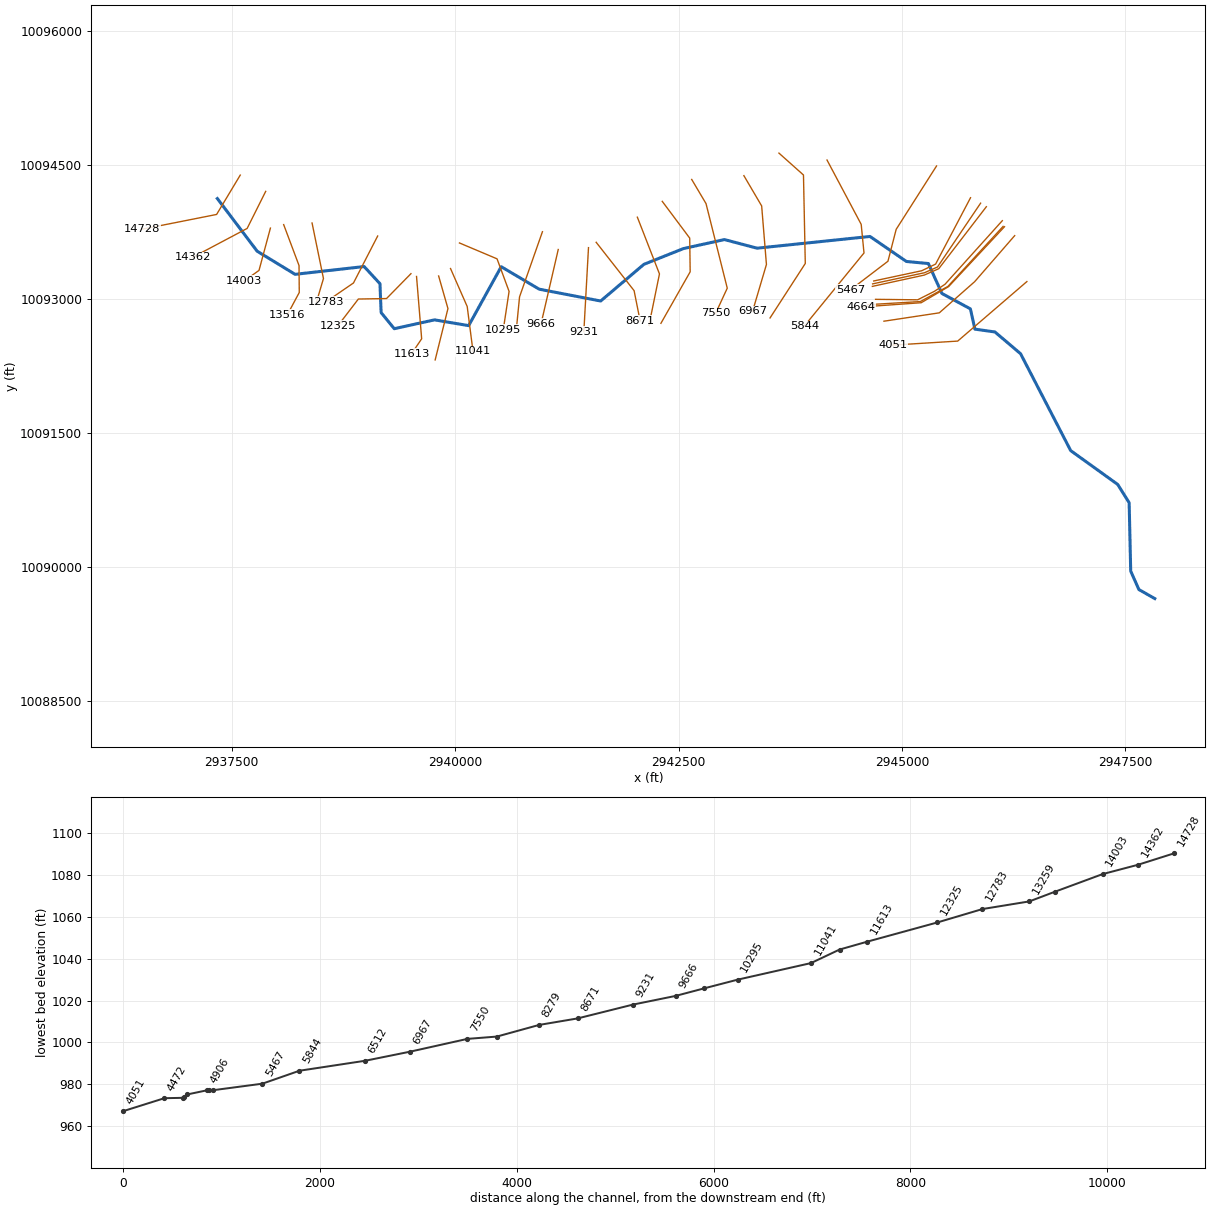
--- UNT 0060 IN LATR.prj (project) ---

Proj Title=UNT 1060 IN LATR Base Level Engineering
Current Plan=p01
Default Exp/Contr=0.3,0.1
English Units
Geom File=g01
Flow File=f01
Plan File=p01
Y Axis Title=Elevation
X Axis Title(PF)=Main Channel Distance
X Axis Title(XS)=Station
BEGIN DESCRIPTION:
UNT 1060 IN LATR
END DESCRIPTION:
DSS Export Rating Curves= 0
DSS Export Rating Curve Sorted= 0
DSS Export Volume Flow Curves= 0
DXF OffsetX= 0
DXF OffsetY= 0
DXF ScaleX= 1
DXF ScaleY= 10

--- UNT 0060 IN LATR.p01 (plan) ---

Plan Title=Multiple Run
Short Identifier=Multiple
Geom File=g01
Flow File=f01
Subcritical Flow
K Sum by GR= 0
Std Step Tol= 0.01
Critical Tol= 0.01
Num of Std Step Trials= 20
Max Error Tol= 0.3
Flow Tol Ratio= 0.001
Split Flow NTrial= 30
Split Flow Tol= 0.02
Split Flow Ratio= 0.02
Log Output Level= 0
Friction Slope Method= 1
Unsteady Friction Slope Method= 2
Unsteady Bridges Friction Slope Method= 1
Parabolic Critical Depth
Global Vel Dist=  1 , 1 , 1
Global Log Level= 0
CheckData=True
Encroach Param= -1, 0, 0, 0
BEGIN DESCRIPTION:
Multiple Run
END DESCRIPTION:

--- UNT 0060 IN LATR.f01 (steady flow) ---

Flow Title=Multiple
Program Version=4.10
Number of Profiles= 7
Profile Names=10-year,25-year,50-year,1pct_min,100-year,1pct_plu,500-year
River Rch & RM=UNT 1060 IN LATR,Reach-1         ,14728
    1505    2240    2895    2734    3697    5000    6055
River Rch & RM=UNT 1060 IN LATR,Reach-1         ,5467
    2701    4141    5458    5248    7097    9598   12059
River Rch & RM=UNT 1060 IN LATR,Reach-1         ,4472
    2701    4141    5458    5248    7097    9598   12059
River Rch & RM=UNT 1060 IN LATR,Reach-1         ,4051
    2701    4141    5458    5248    7097    9598   12059
Boundary for River Rch & Prof#=UNT 1060 IN LATR,Reach-1         , 1
Up Type= 0
Dn Type= 3
Dn Slope=0.005
Boundary for River Rch & Prof#=UNT 1060 IN LATR,Reach-1         , 2
Up Type= 0
Dn Type= 3
Dn Slope=0.005
Boundary for River Rch & Prof#=UNT 1060 IN LATR,Reach-1         , 3
Up Type= 0
Dn Type= 3
Dn Slope=0.005
Boundary for River Rch & Prof#=UNT 1060 IN LATR,Reach-1         , 4
Up Type= 0
Dn Type= 3
Dn Slope=0.005
Boundary for River Rch & Prof#=UNT 1060 IN LATR,Reach-1         , 5
Up Type= 0
Dn Type= 3
Dn Slope=0.005
Boundary for River Rch & Prof#=UNT 1060 IN LATR,Reach-1         , 6
Up Type= 0
Dn Type= 3
Dn Slope=0.005
Boundary for River Rch & Prof#=UNT 1060 IN LATR,Reach-1         , 7
Up Type= 0
Dn Type= 3
Dn Slope=0.005
DSS Import GetInterval= 0
DSS Import GetPeak= 0
DSS Import FillOption= 0

--- UNT 0060 IN LATR.g01 (geometry) ---

Geom Title=Existing Conditions
Program Version=4.10

River Reach=UNT 1060 IN LATR,Reach-1
Reach XY= 30
       2937338.3     10094122.57       2937784.1     10093532.49
      2938208.47     10093273.73      2938981.12     10093360.88
      2939158.24     10093168.63      2939171.43     10092845.02
      2939318.29      10092664.7      2939768.65     10092763.66
      2940151.01     10092699.11      2940515.26     10093358.96
        2940940.     10093107.48      2941628.44      10092974.8
      2942112.41      10093385.6      2942554.14      10093561.8
      2943013.75     10093663.04      2943378.41     10093566.37
      2944642.42     10093697.81       2945050.1     10093417.69
      2945296.25      10093394.4      2945447.19     10093059.42
      2945765.94     10092886.92      2945816.96      10092659.8
      2946040.95     10092628.22      2946327.76     10092384.82
      2946888.75     10091299.39       2947414.3     10090921.08
      2947543.05     10090716.29      2947560.43     10089949.53
      2947651.76     10089743.63      2947829.87       10089642.

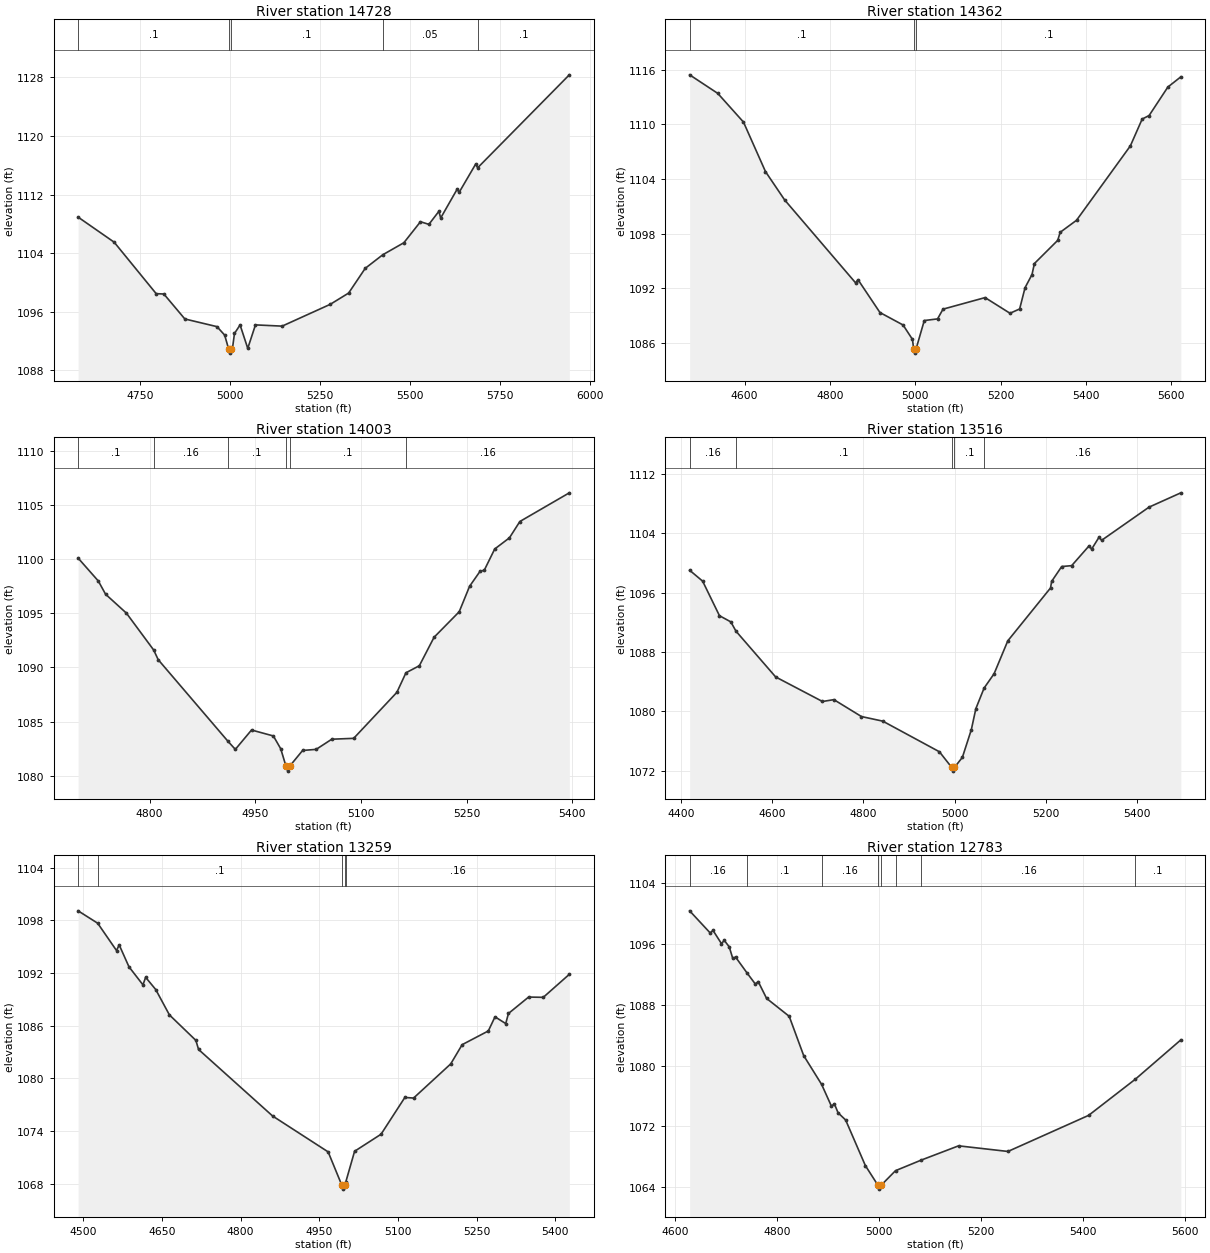
Type RM Length L Ch R = 1 ,14728   ,366,366,366
BEGIN DESCRIPTION:
UNT 1060 IN LATR 30.0
END DESCRIPTION:
XS GIS Cut Line= 3
      2937594.93     10094385.09      2937330.02     10093944.26
      2936495.72     10093778.56
#Sta/Elev= 30
  4576.9 1108.91  4677.2 1105.48  4793.8 1098.45  4815.2  1098.4  4873.5 1094.99
  4962.8 1093.94  4984.2 1092.78  4995.5 1090.82  4998.2 1090.32  5001.5 1090.82
  5005.6 1090.89  5011.4 1093.01    5027 1094.17  5048.3 1090.97  5069.7 1094.18
  5143.8 1094.01  5277.5 1096.99  5328.6 1098.53  5374.7 1101.91  5423.3 1103.76
  5482.1 1105.41  5528.2 1108.28  5551.6 1107.92  5579.3  1109.7  5584.4 1108.79
  5630.5 1112.76  5635.6 1112.29  5681.6 1116.16    5687 1115.65  5941.8 1128.36
#Mann= 5 ,-1 , 0
  4576.9      .1       0  4995.5     .07       0  5001.5      .1       0
  5423.3     .05       0    5687      .1       0
Bank Sta=4995.5,5001.5
XS Rating Curve= 0 ,0
Exp/Cntr=0.3,0.1

Type RM Length L Ch R = 1 ,14362   ,359,359,359
BEGIN DESCRIPTION:
Mapping XS 801930a1
END DESCRIPTION:
XS GIS Cut Line= 3
      2937879.36     10094202.74      2937671.82     10093787.66
      2937064.67      10093465.5
#Sta/Elev= 30
    4471 1115.44    4537  1113.4  4597.2 1110.25  4648.8 1104.81  4693.5 1101.71
    4860 1092.59  4865.6 1092.94  4917.1 1089.33  4971.3 1087.96  4993.3 1086.38
    4996 1085.37  4998.7 1084.87    5002 1085.37    5021 1088.45  5052.1 1088.63
  5064.9  1089.7  5163.5 1090.97  5221.9 1089.25  5244.5 1089.72  5257.2 1092.06
  5273.5  1093.5  5279.1 1094.71  5333.8 1097.26  5339.5 1098.14  5377.8 1099.46
    5504 1107.63  5531.7 1110.58    5548 1110.97    5592  1114.1  5622.4 1115.22
#Mann= 3 ,-1 , 0
    4471      .1       0    4996     .07       0    5002      .1       0
Bank Sta=4996,5002
XS Rating Curve= 0 ,0
Exp/Cntr=0.3,0.1

Type RM Length L Ch R = 1 ,14003   ,487,487,487
BEGIN DESCRIPTION:
UNT 1060 IN LATR 29.0
END DESCRIPTION:
XS GIS Cut Line= 3
      2937932.27     10093791.44      2937804.65     10093317.43
      2937636.16     10093198.19
#Sta/Elev= 30
  4698.5 1100.11  4727.2 1097.99  4737.5 1096.77  4767.1 1095.02  4805.8 1091.61
  4812.2 1090.72  4911.2 1083.18  4921.7 1082.43  4944.7 1084.22  4975.7 1083.67
  4986.1 1082.49  4993.4 1080.92  4996.2 1080.42  4999.4 1080.92  5017.2 1082.33
  5036.4 1082.43  5058.6 1083.37  5089.7 1083.45    5151  1087.7  5163.9 1089.51
  5182.9 1090.16  5203.8 1092.79  5239.5 1095.15  5254.2  1097.5    5269 1098.88
  5275.1 1098.99  5289.9 1100.95  5310.8 1101.98  5325.6 1103.49  5395.8 1106.14
#Mann= 6 ,-1 , 0
  4698.5      .1       0  4805.8     .16       0  4911.2      .1       0
  4993.4     .07       0  4999.4      .1       0  5163.9     .16       0
Bank Sta=4993.4,4999.4
XS Rating Curve= 0 ,0
Exp/Cntr=0.3,0.1

Type RM Length L Ch R = 1 ,13516   ,257,257,257
BEGIN DESCRIPTION:
UNT 1060 IN LATR 28.0
END DESCRIPTION:
XS GIS Cut Line= 4
       2938080.7     10093830.44      2938252.57     10093372.12
      2938255.17     10093070.04      2938120.08     10092818.05
#Sta/Elev= 30
  4418.7 1099.04  4447.2 1097.57  4484.1 1092.91    4509 1092.08  4520.4 1090.82
  4607.4 1084.65  4710.1 1081.34  4735.1 1081.59  4795.6 1079.31  4842.4 1078.69
  4966.6 1074.56  4993.6 1072.45  4996.3 1071.95  4999.6 1072.45    5017 1073.81
  5036.6 1077.54  5046.6 1080.39  5064.6 1083.15  5086.6 1085.09  5116.6 1089.52
  5210.3 1096.65  5212.8 1097.54  5234.8 1099.54  5256.7 1099.66  5294.9 1102.33
  5300.5 1101.89  5316.8  1103.5  5322.5 1103.08  5426.4 1107.55  5496.2 1109.48
#Mann= 5 ,-1 , 0
  4418.7     .16       0  4520.4      .1       0  4993.6     .07       0
  4999.6      .1       0  5064.6     .16       0
Bank Sta=4993.6,4999.6
XS Rating Curve= 0 ,0
Exp/Cntr=0.3,0.1

Type RM Length L Ch R = 1 ,13259   ,476,476,476
BEGIN DESCRIPTION:
UNT 1060 IN LATR 27.0
END DESCRIPTION:
XS GIS Cut Line= 3
       2938398.4     10093848.67        2938526.     10093226.29
      2938440.29     10092937.98
#Sta/Elev= 30
  4490.4 1099.07  4527.7 1097.66  4563.6 1094.55  4568.7 1095.19  4587.3  1092.7
    4614 1090.64  4619.1  1091.5  4638.3 1090.11  4664.4 1087.22  4714.8 1084.32
    4720 1083.28    4861 1075.71  4966.9 1071.62  4992.6 1067.88  4995.4 1067.38
  4998.6 1067.88  5000.5 1068.19  5017.3 1071.69  5067.7 1073.63  5113.1 1077.82
  5129.7 1077.75  5200.5 1081.64  5222.3 1083.83  5272.1 1085.39  5284.9    1087
  5305.3 1086.23  5310.5 1087.38  5348.9 1089.25  5376.9 1089.22  5426.5 1091.84
#Mann= 5 ,-1 , 0
  4490.4     .16       0  4527.7      .1       0  4992.6     .07       0
  4998.6      .1       0  5000.5     .16       0
Bank Sta=4992.6,4998.6
XS Rating Curve= 0 ,0
Exp/Cntr=0.3,0.1

Type RM Length L Ch R = 1 ,12783   ,458,458,458
BEGIN DESCRIPTION:
UNT 1060 IN LATR 26.0
END DESCRIPTION:
XS GIS Cut Line= 3
      2939132.77     10093702.84      2938861.94     10093176.81
      2938554.63     10092965.86
#Sta/Elev= 30
  4627.8 1100.37  4668.1 1097.46  4673.7 1097.79  4690.2 1096.06  4695.9 1096.47
  4705.5 1095.63  4712.4 1094.12    4718 1094.28  4740.6 1092.18  4756.8 1090.73
  4762.4 1091.06  4778.9 1088.84  4823.3 1086.48  4851.7 1081.31  4886.9 1077.52
  4906.3 1074.63  4911.9 1074.97  4919.2 1073.78  4934.1 1072.83  4972.8 1066.83
  4997.6 1064.23  5000.4 1063.73  5003.6 1064.23    5032 1066.16  5082.8 1067.56
  5155.8 1069.43  5252.7 1068.69  5411.1 1073.44    5503 1078.21  5592.2 1083.38
#Mann= 8 ,-1 , 0
  4627.8     .16       0  4740.6      .1       0  4886.9     .16       0
  4997.6     .07       0  5003.6     .16       0    5032      .1       0
  5082.8     .16       0    5503      .1       0
Bank Sta=4997.6,5003.6
XS Rating Curve= 0 ,0
Exp/Cntr=0.3,0.1

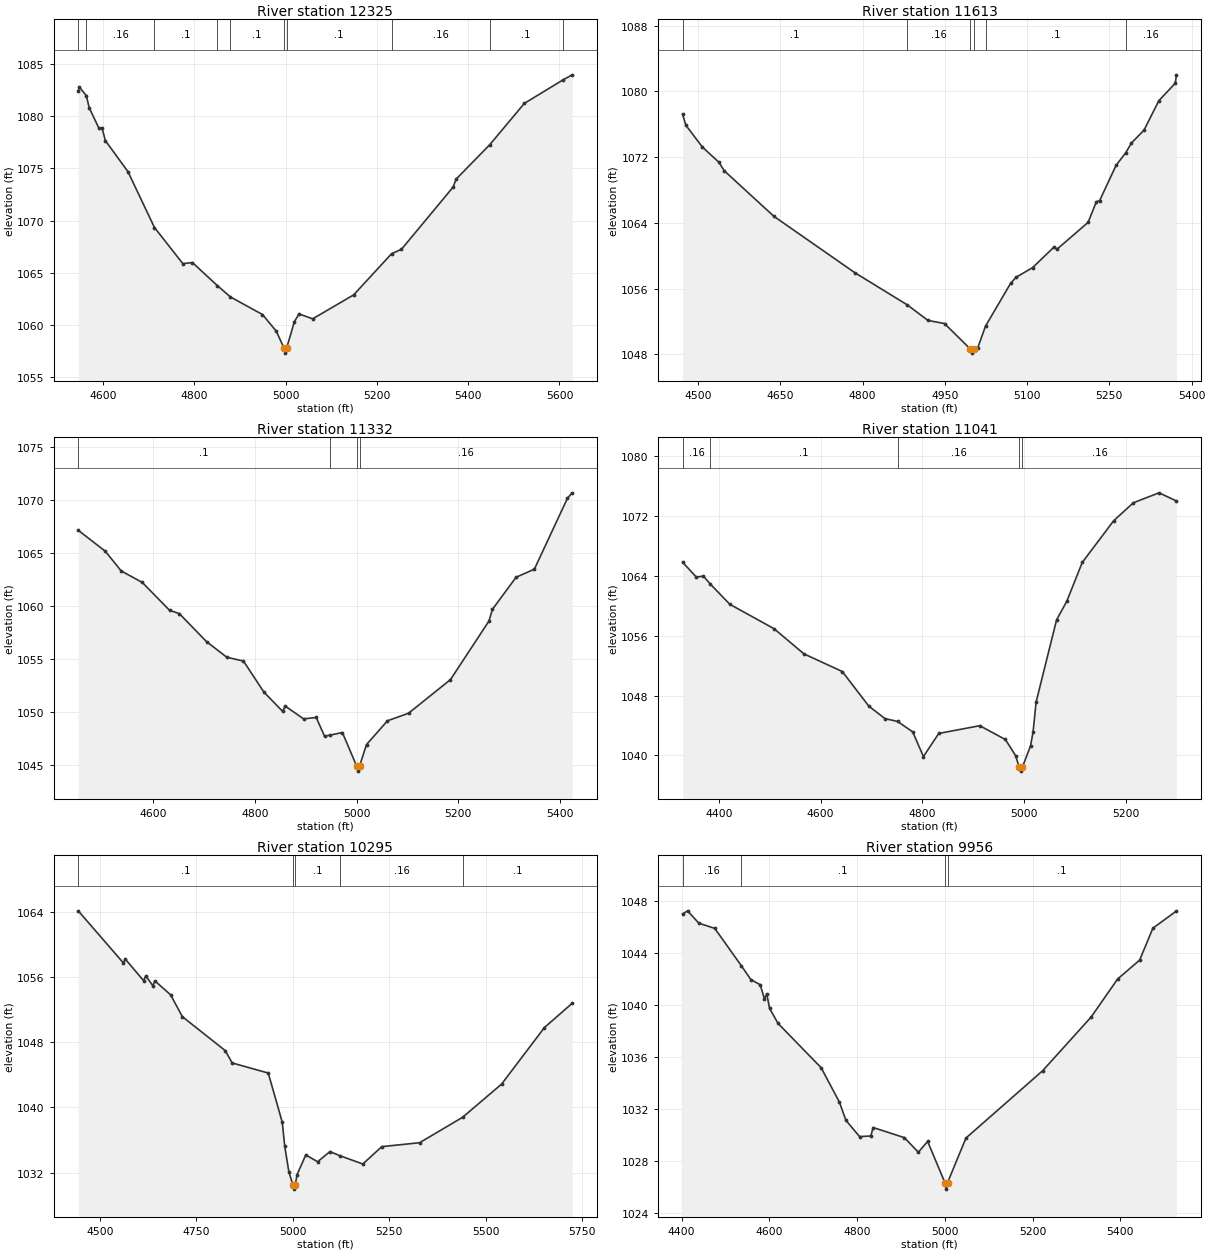
Type RM Length L Ch R = 1 ,12325   ,712,712,712
BEGIN DESCRIPTION:
UNT 1060 IN LATR 25.0
END DESCRIPTION:
XS GIS Cut Line= 4
      2939505.14     10093280.95      2939231.73     10093002.33
      2938916.63     10092997.12      2938687.89      10092698.2
#Sta/Elev= 30
  4545.9 1082.41  4548.6 1082.76  4563.7 1081.94  4569.9  1080.8  4591.1 1078.84
  4598.1 1078.86  4605.2 1077.66  4654.7 1074.69  4712.9 1069.34    4775 1065.89
  4796.1 1065.99  4850.5 1063.79  4879.4  1062.7  4949.5 1061.02  4979.5 1059.44
  4996.5 1057.83  4999.3 1057.33  5002.5 1057.83  5019.5 1060.35  5029.5 1061.08
  5059.5 1060.61  5149.2  1062.9  5232.2 1066.83    5254 1067.26  5367.3 1073.22
  5373.5 1073.96  5447.4 1077.26  5523.1 1081.21  5606.8 1083.43  5627.8 1083.94
#Mann= 10 ,-1 , 0
  4545.9      .1       0  4563.7     .16       0  4712.9      .1       0
  4850.5     .16       0  4879.4      .1       0  4996.5     .07       0
  5002.5      .1       0  5232.2     .16       0  5447.4      .1       0
  5606.8     .16       0
Bank Sta=4996.5,5002.5
XS Rating Curve= 0 ,0
Exp/Cntr=0.3,0.1

Type RM Length L Ch R = 1 ,11613   ,281,281,281
BEGIN DESCRIPTION:
UNT 1060 IN LATR 24.0
END DESCRIPTION:
XS GIS Cut Line= 3
      2939567.67     10093249.71      2939624.96     10092551.81
      2939513.23     10092385.51
#Sta/Elev= 30
  4471.8 1077.21  4477.8 1075.88  4507.9 1073.23  4537.8 1071.39    4548 1070.33
  4638.3  1064.8  4785.4 1057.96  4881.1 1054.04  4919.3 1052.13  4949.4 1051.75
  4996.5 1048.65  4999.3 1048.15  5002.5 1048.65  5009.6 1048.72  5024.2 1051.44
  5069.8 1056.63  5079.8 1057.38  5109.9 1058.55  5149.4 1061.08  5154.4 1060.79
  5211.2 1064.06  5226.2 1066.56  5232.3 1066.72  5262.2    1071    5280 1072.55
  5290.2 1073.72  5313.2 1075.29  5340.3 1078.88  5370.2    1081  5372.4 1082.02
#Mann= 6 ,-1 , 0
  4471.8      .1       0  4881.1     .16       0  4996.5     .07       0
  5002.5     .16       0  5024.2      .1       0    5280     .16       0
Bank Sta=4996.5,5002.5
XS Rating Curve= 0 ,0
Exp/Cntr=0.3,0.1

Type RM Length L Ch R = 1 ,11332   ,291,291,291
BEGIN DESCRIPTION:
UNT 1060 IN LATR 23.0
END DESCRIPTION:
XS GIS Cut Line= 3
      2939815.06     10093254.96      2939919.23     10092890.35
        2939776.     10092314.81
#Sta/Elev= 30
  4452.1 1067.15  4505.4 1065.17  4536.6 1063.31  4578.2 1062.22  4631.8 1059.59
    4651 1059.28  4704.6 1056.63  4744.6 1055.15  4777.4 1054.79  4817.4 1051.87
  4854.4 1050.04  4859.5 1050.54  4895.7 1049.33  4920.6 1049.46    4937 1047.69
  4946.9 1047.78  4972.1 1048.04    5000 1044.89  5002.8 1044.39    5006 1044.89
  5019.6  1046.9  5060.9 1049.15  5102.3 1049.86  5184.9 1053.04  5260.6 1058.57
  5267.5 1059.68    5314 1062.71  5350.1 1063.48  5415.2 1070.18  5424.4 1070.69
#Mann= 4 ,-1 , 0
  4452.1      .1       0  4946.9     .16       0    5000     .07       0
    5006     .16       0
Bank Sta=5000,5006
XS Rating Curve= 0 ,0
Exp/Cntr=0.3,0.1

Type RM Length L Ch R = 1 ,11041   ,746,746,746
BEGIN DESCRIPTION:
Mapping XS 0efb74ac
END DESCRIPTION:
XS GIS Cut Line= 3
      2939948.07      10093338.5      2940134.68      10092913.2
      2940199.79     10092409.73
#Sta/Elev= 30
  4328.2 1065.79  4355.2  1063.8  4369.1 1063.93  4382.8 1062.87  4421.3 1060.16
  4508.1 1056.92  4566.9 1053.56  4642.5  1051.2  4694.6 1046.59  4726.5 1044.92
  4751.3 1044.54  4781.1 1043.15  4802.2 1039.85  4832.4 1042.94  4913.1 1043.97
  4963.5 1042.13  4983.7 1039.97  4990.8 1038.41  4993.5 1037.91  4996.8 1038.41
    5013 1041.28    5018 1043.12    5024 1047.13  5064.3 1058.09  5084.5 1060.59
  5114.8 1065.75  5176.7 1071.32  5215.6 1073.72    5266 1075.04  5300.3 1073.95
#Mann= 5 ,-1 , 0
  4328.2     .16       0  4382.8      .1       0  4751.3     .16       0
  4990.8     .07       0  4996.8     .16       0
Bank Sta=4990.8,4996.8
XS Rating Curve= 0 ,0
Exp/Cntr=0.3,0.1

Type RM Length L Ch R = 1 ,10295   ,339,339,339
BEGIN DESCRIPTION:
UNT 1060 IN LATR 22.0
END DESCRIPTION:
XS GIS Cut Line= 4
      2940047.89       10093625.      2940468.89     10093447.05
      2940603.43     10093082.47      2940538.33     10092652.75
#Sta/Elev= 30
  4443.7  1064.1  4560.4 1057.73  4565.9 1058.17  4613.3 1055.53  4618.7 1056.13
    4637 1054.92  4642.4 1055.51  4683.2  1053.8  4713.5 1051.13  4824.6 1046.97
  4842.8 1045.45  4936.3 1044.21  4972.7 1038.16  4978.9 1035.26  4989.6 1032.13
  5000.1 1030.48  5002.8 1029.98  5006.1 1030.48  5010.9 1031.75  5033.5 1034.17
  5064.2 1033.34  5096.2 1034.58    5123 1034.06  5181.4 1033.06  5230.6 1035.19
  5328.6 1035.67  5440.1 1038.79    5541 1042.85  5652.2 1049.79    5724 1052.76
#Mann= 5 ,-1 , 0
  4443.7      .1       0  5000.1     .07       0  5006.1      .1       0
    5123     .16       0  5440.1      .1       0
Bank Sta=5000.1,5006.1
XS Rating Curve= 0 ,0
Exp/Cntr=0.3,0.1

Type RM Length L Ch R = 1 ,9956    ,290,290,290
BEGIN DESCRIPTION:
UNT 1060 IN LATR 21.0
END DESCRIPTION:
XS GIS Cut Line= 3
      2940976.69     10093750.85      2940720.62      10093021.7
       2940685.9     10092670.12
#Sta/Elev= 30
  4402.2 1047.01  4413.5 1047.25  4439.2  1046.3  4475.5  1045.9  4536.3 1043.02
  4557.8 1041.96  4579.3 1041.56  4588.8 1040.47  4594.1 1040.86  4600.5 1039.75
  4619.8 1038.59  4718.1 1035.18  4759.5 1032.55  4774.7 1031.13  4805.7 1029.88
  4831.4 1029.93  4836.7 1030.58  4907.9  1029.8  4939.7 1028.68  4960.9 1029.51
  5000.3 1026.34    5003 1025.84  5006.3 1026.34  5048.3 1029.77  5223.2 1034.95
  5333.7 1039.08    5394    1042  5444.3 1043.46  5474.4 1045.91  5528.3 1047.24
#Mann= 4 ,-1 , 0
  4402.2     .16       0  4536.3      .1       0  5000.3     .07       0
  5006.3      .1       0
Bank Sta=5000.3,5006.3
XS Rating Curve= 0 ,0
Exp/Cntr=0.3,0.1

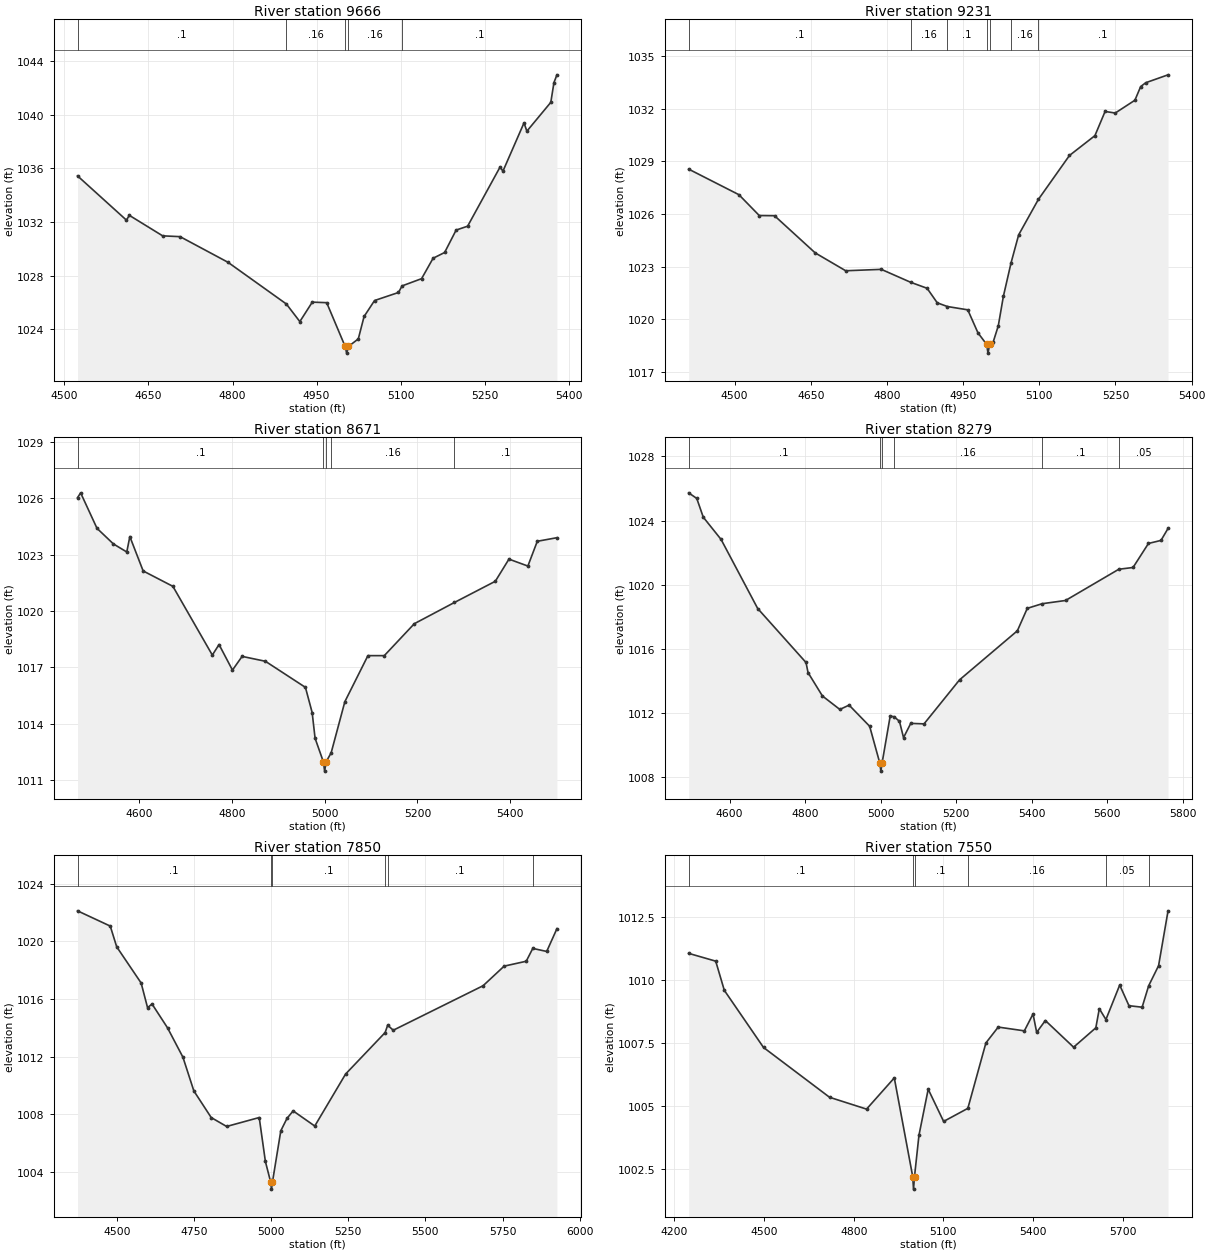
Type RM Length L Ch R = 1 ,9666    ,435,435,435
BEGIN DESCRIPTION:
UNT 1060 IN LATR 20.0
END DESCRIPTION:
XS GIS Cut Line= 2
       2941153.6     10093551.77      2940960.92     10092718.56
#Sta/Elev= 30
  4523.5 1035.44  4610.8 1032.14  4615.9  1032.5  4675.4 1030.97  4706.5 1030.91
  4791.9    1029  4896.1 1025.89  4920.1 1024.58  4942.3 1026.03    4968 1025.99
  5000.9 1022.73  5003.6 1022.23  5006.9 1022.73  5024.4 1023.29  5034.7 1024.96
  5053.4 1026.15  5096.1 1026.75  5102.5 1027.24  5137.3 1027.78  5157.8  1029.3
  5178.4 1029.73  5198.9  1031.4  5219.4 1031.69  5277.3  1036.1  5282.4 1035.79
    5320 1039.39  5325.1 1038.77  5367.8 1040.92  5373.4 1042.39  5378.7 1042.97
#Mann= 5 ,-1 , 0
  4523.5      .1       0  4896.1     .16       0  5000.9     .07       0
  5006.9     .16       0  5102.5      .1       0
Bank Sta=5000.9,5006.9
XS Rating Curve= 0 ,0
Exp/Cntr=0.3,0.1

Type RM Length L Ch R = 1 ,9231    ,560,560,560
BEGIN DESCRIPTION:
UNT 1060 IN LATR 19.0
END DESCRIPTION:
XS GIS Cut Line= 2
      2941492.15      10093572.6      2941440.07     10092629.93
#Sta/Elev= 30
  4409.4 1028.56  4508.4  1027.1  4548.5 1025.91  4578.5  1025.9  4658.6 1023.78
  4718.7 1022.76  4788.8 1022.84  4846.8  1022.1    4879 1021.76    4899 1020.93
  4918.9 1020.72  4959.1 1020.53  4979.1 1019.22  4996.2 1018.56  4998.9 1018.06
  5002.2 1018.56  5009.2  1018.7  5019.2 1019.62  5029.2  1021.3  5044.4 1023.22
  5059.3 1024.81  5098.1 1026.83  5159.4 1029.34  5209.5 1030.47  5229.5 1031.85
  5249.5 1031.76  5288.2 1032.49  5299.6 1033.27  5309.6 1033.49  5353.5 1033.94
#Mann= 7 ,-1 , 0
  4409.4      .1       0  4846.8     .16       0  4918.9      .1       0
  4996.2     .07       0  5002.2      .1       0  5044.4     .16       0
  5098.1      .1       0
Bank Sta=4996.2,5002.2
XS Rating Curve= 0 ,0
Exp/Cntr=0.3,0.1

Type RM Length L Ch R = 1 ,8671    ,392,392,392
BEGIN DESCRIPTION:
UNT 1060 IN LATR 18.0
END DESCRIPTION:
XS GIS Cut Line= 3
      2941578.12      10093632.5      2942002.57     10093090.87
      2942070.28      10092752.3
#Sta/Elev= 30
  4467.3 1026.04    4474  1026.3  4509.3 1024.41  4544.6 1023.58  4573.5 1023.15
  4580.1 1023.97  4608.8 1022.14  4672.9 1021.32  4757.9 1017.66  4772.4 1018.22
  4801.3 1016.86  4822.1 1017.59  4872.3 1017.33  4958.6 1015.94  4973.1  1014.6
  4979.4 1013.23  4997.2 1011.98    5000 1011.48  5003.2 1011.98    5014 1012.45
  5043.6 1015.18  5093.3 1017.63  5128.6 1017.63  5193.3 1019.33  5279.7 1020.46
  5367.9 1021.59  5397.3 1022.77  5438.1  1022.4  5458.4 1023.72  5500.7 1023.91
#Mann= 5 ,-1 , 0
  4467.3      .1       0  4997.2     .07       0  5003.2      .1       0
    5014     .16       0  5279.7      .1       0
Bank Sta=4997.2,5003.2
XS Rating Curve= 0 ,0
Exp/Cntr=0.3,0.1

Type RM Length L Ch R = 1 ,8279    ,429,429,429
BEGIN DESCRIPTION:
UNT 1060 IN LATR 17.0
END DESCRIPTION:
XS GIS Cut Line= 3
      2942039.02     10093913.81      2942286.42     10093278.37
      2942169.24     10092702.88
#Sta/Elev= 30
  4491.4 1025.73  4512.9 1025.38  4530.1 1024.21  4577.3 1022.82  4674.2 1018.51
  4802.1 1015.14  4807.5 1014.51  4845.6 1013.05  4891.7 1012.21  4916.2 1012.48
  4970.6 1011.16  4997.5 1008.86  5000.3 1008.36  5003.5 1008.86    5025  1011.8
  5035.6 1011.75  5049.5 1011.47  5060.3 1010.45  5079.4 1011.34  5114.6 1011.31
  5208.7 1014.06  5361.7 1017.12  5387.9 1018.52  5427.4 1018.81  5489.1 1019.01
  5630.2 1020.96  5667.9 1021.07  5708.7 1022.57  5741.9 1022.76  5760.6 1023.51
#Mann= 6 ,-1 , 0
  4491.4      .1       0  4997.5     .07       0  5003.5      .1       0
  5035.6     .16       0  5427.4      .1       0  5630.2     .05       0
Bank Sta=4997.5,5003.5
XS Rating Curve= 0 ,0
Exp/Cntr=0.3,0.1

Type RM Length L Ch R = 1 ,7850    ,300,300,300
BEGIN DESCRIPTION:
UNT 1060 IN LATR 16.0
END DESCRIPTION:
XS GIS Cut Line= 4
      2942317.67     10094090.88      2942624.96     10093679.41
      2942630.17     10093301.81      2942302.76     10092724.94
#Sta/Elev= 30
  4371.9 1022.12  4478.1 1021.06    4499 1019.62  4578.2 1017.11    4599  1015.4
  4613.6 1015.65  4663.7    1014  4713.7 1011.96  4749.1 1009.62  4805.4 1007.77
  4855.4 1007.15  4961.1 1007.77  4981.1 1004.72  4998.1  1003.3  5000.9  1002.8
  5004.1  1003.3  5031.1 1006.85  5051.1 1007.71  5071.1 1008.23  5141.2 1007.18
  5241.2 1010.79  5369.4 1013.67  5377.6 1014.18  5395.7 1013.83    5687 1016.92
  5755.3 1018.28  5826.9 1018.62  5848.1 1019.51  5893.3  1019.3  5926.4 1020.88
#Mann= 6 ,-1 , 0
  4371.9      .1       0  4998.1     .07       0  5004.1      .1       0
  5369.4     .16       0  5377.6      .1       0  5848.1     .05       0
Bank Sta=4998.1,5004.1
XS Rating Curve= 0 ,0
Exp/Cntr=0.3,0.1

Type RM Length L Ch R = 1 ,7550    ,583,583,583
BEGIN DESCRIPTION:
UNT 1060 IN LATR 15.0
END DESCRIPTION:
XS GIS Cut Line= 4
      2942647.23     10094336.43       2942807.5     10094065.63
      2943045.16     10093118.69      2942914.35     10092834.97
#Sta/Elev= 30
  4247.9 1011.06  4338.4 1010.75  4367.2 1009.59  4498.3 1007.32  4719.2 1005.34
  4842.9 1004.87  4935.7 1006.11  4997.3 1002.19    5000 1001.69  5003.3 1002.19
  5018.2 1003.83  5049.1 1005.66  5100.7 1004.38  5181.7  1004.9  5242.1  1007.5
  5283.3 1008.13  5370.7 1007.98  5399.7 1008.65  5411.9 1007.92  5440.9 1008.39
  5535.4 1007.33  5609.7  1008.1  5621.4 1008.86  5643.5 1008.43  5689.6  1009.8
  5720.5 1008.98  5764.6 1008.92  5786.4 1009.77  5819.6 1010.57  5851.3 1012.75
#Mann= 6 ,-1 , 0
  4247.9      .1       0  4997.3     .07       0  5003.3      .1       0
  5181.7     .16       0  5643.5     .05       0  5786.4      .1       0
Bank Sta=4997.3,5003.3
XS Rating Curve= 0 ,0
Exp/Cntr=0.3,0.1

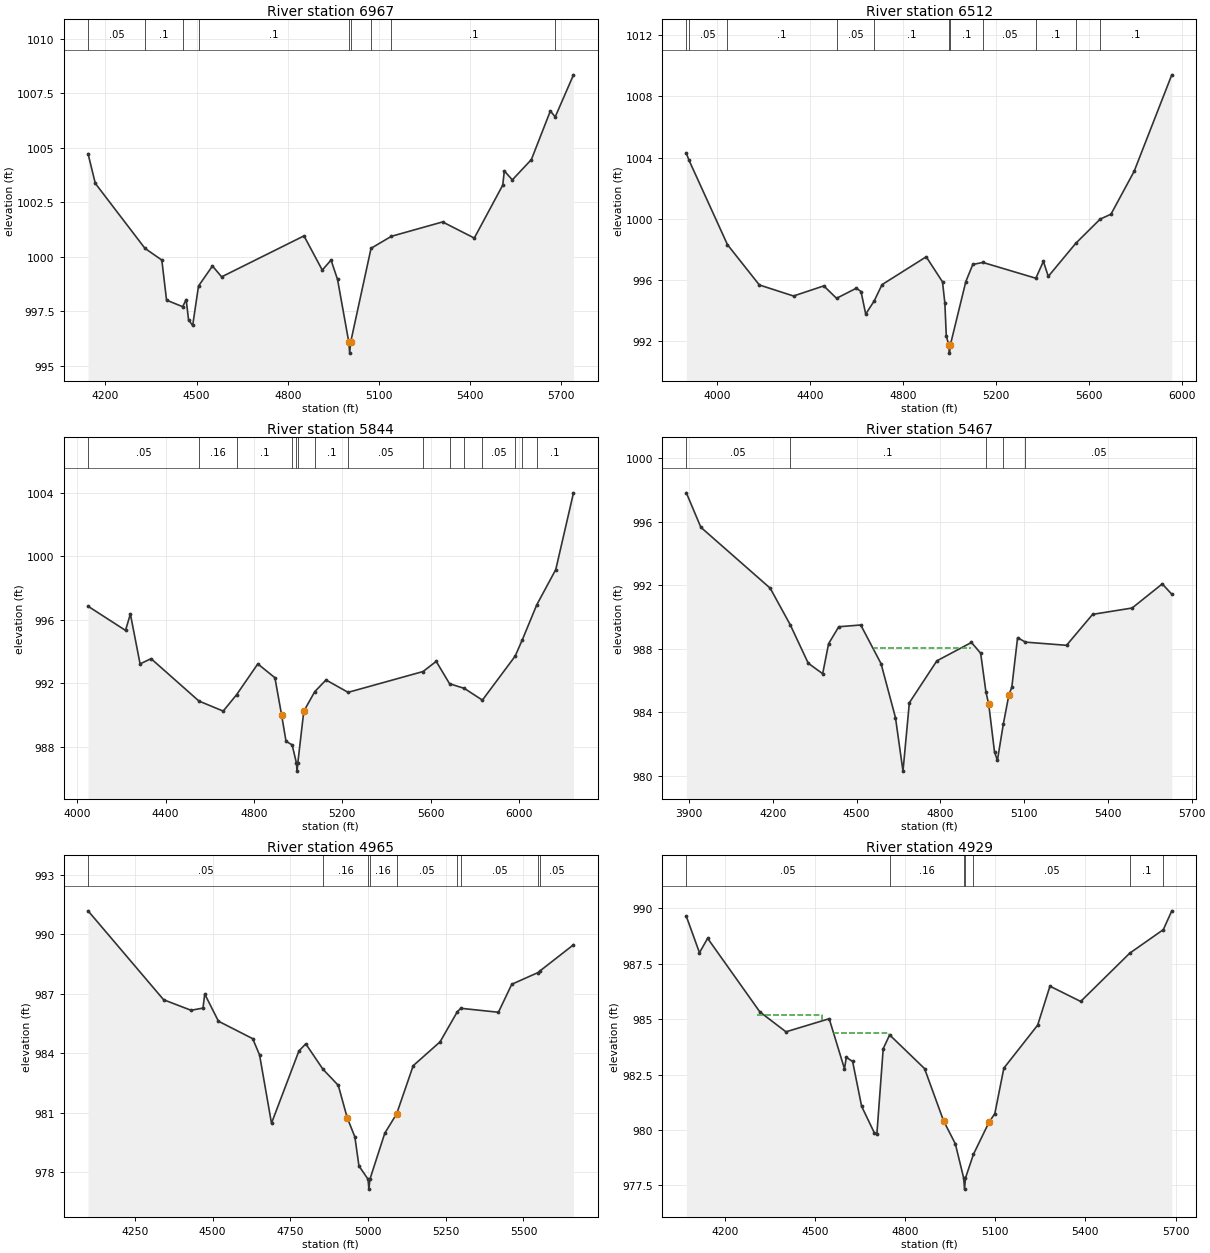
Type RM Length L Ch R = 1 ,6967    ,455,455,455
BEGIN DESCRIPTION:
UNT 1060 IN LATR 14.0
END DESCRIPTION:
XS GIS Cut Line= 4
      2943231.21     10094378.84       2943430.2     10094039.83
      2943483.62     10093383.98      2943328.88      10092860.8
#Sta/Elev= 30
    4143 1004.72  4166.8 1003.36    4330 1000.38  4385.6  999.84  4401.2     998
  4454.2   997.7  4465.7  998.03  4473.6  997.09  4487.1  996.84  4506.3  998.65
  4552.2  999.57  4582.3  999.07  4853.2 1000.95  4913.4  999.38  4942.2  999.84
  4963.6  998.95  5000.7  996.07  5003.5  995.57  5006.7  996.07  5073.8 1000.38
  5140.6 1000.93  5309.1 1001.59  5413.4 1000.85    5507 1003.28  5512.2 1003.93
  5538.5 1003.52  5601.1 1004.45  5663.6 1006.68  5679.6 1006.41  5739.7 1008.34
#Mann= 9 ,-1 , 0
    4143     .05       0    4330      .1       0  4454.2     .05       0
  4506.3      .1       0  5000.7     .07       0  5006.7      .1       0
  5073.8     .05       0  5140.6      .1       0  5679.6     .05       0
Bank Sta=5000.7,5006.7
XS Rating Curve= 0 ,0
Exp/Cntr=0.3,0.1

Type RM Length L Ch R = 1 ,6512    ,668,668,668
BEGIN DESCRIPTION:
UNT 1060 IN LATR 13.0
END DESCRIPTION:
XS GIS Cut Line= 4
      2943623.64      10094631.2      2943898.14     10094386.18
       2943918.4     10093395.04      2943524.17     10092785.27
#Sta/Elev= 30
  3869.4 1004.29  3880.6 1003.84  4046.1  998.32    4183  995.69  4329.8  994.97
  4459.8  995.63  4514.7  994.82  4599.9  995.48  4619.9  995.26  4639.9  993.79
  4676.5  994.65  4709.9  995.71  4899.9  997.53  4969.9  995.89  4979.9  994.51
  4986.1  992.38    4997  991.74  4999.7  991.24    5003  991.74    5070  995.91
    5100  997.03  5143.4  997.16  5370.8  996.13  5403.2  997.23  5424.3  996.25
  5542.3  998.41  5647.1  999.99  5693.5 1000.31  5793.1 1003.11  5954.8 1009.41
#Mann= 11 ,-1 , 0
  3869.4      .1       0  3880.6     .05       0  4046.1      .1       0
  4514.7     .05       0  4676.5      .1       0    4997     .07       0
    5003      .1       0  5143.4     .05       0  5370.8      .1       0
  5542.3     .05       0  5647.1      .1       0
Bank Sta=4997,5003
XS Rating Curve= 0 ,0
Exp/Cntr=0.3,0.1

Type RM Length L Ch R = 1 ,5844    ,377,377,377
BEGIN DESCRIPTION:
UNT 1060 IN LATR 12.0
END DESCRIPTION:
XS GIS Cut Line= 4
      2944161.57     10094553.85      2944544.23     10093833.06
      2944575.48     10093512.75      2943906.21     10092692.43
#Sta/Elev= 30
  4049.3  996.85  4218.8  995.33  4240.8  996.36  4284.7  993.22  4334.4  993.55
  4551.2  990.88  4660.8  990.25  4721.3  991.28  4817.4  993.22  4894.8  992.35
    4925  990.01  4945.1  988.35  4972.8  988.12  4992.3  986.97  4995.1  986.47
  4998.3  986.97  5025.5  990.24    5075  991.47  5125.9  992.21    5226  991.43
  5565.1  992.74  5624.7  993.38  5685.2  991.97  5751.8  991.68  5833.6  990.94
  5981.9  993.71  6014.7  994.75  6079.7  996.94  6165.7  999.16  6245.9 1003.99
#Mann= 15 ,-1 , 0
  4049.3     .05       0  4551.2     .16       0  4721.3      .1       0
  4972.8     .16       0  4992.3     .07       0  4998.3     .16       0
    5075      .1       0    5226     .05       0  5565.1      .1       0
  5685.2     .05       0  5751.8      .1       0  5833.6     .05       0
  5981.9      .1       0  6014.7     .05       0  6079.7      .1       0
Bank Sta=4925,5025.5
XS Rating Curve= 0 ,0
Exp/Cntr=0.3,0.1

Type RM Length L Ch R = 1 ,5467    ,502,502,502
BEGIN DESCRIPTION:
Mapping XS 39443bbd
END DESCRIPTION:
XS GIS Cut Line= 4
      2945387.65     10094487.53      2944935.66     10093777.44
      2944843.61     10093420.27      2944423.85     10093099.93
#Sta/Elev= 30
  3890.2  997.82  3942.1  995.65  4190.5  991.81  4262.1  989.51  4326.8  987.08
  4378.5  986.42  4399.6  988.31  4436.1  989.38  4514.8  989.49  4587.6  987.05
  4639.2  983.65  4666.1  980.28  4688.9  984.59  4787.4  987.23  4911.3  988.39
  4944.3  987.71    4963  985.29  4973.3  984.48  4993.9  981.49  5004.3  980.96
  5025.6  983.26  5045.6   985.1  5055.9  985.57  5076.5  988.69  5104.8  988.41
  5251.8  988.21  5345.3  990.16  5486.7  990.56  5594.7  992.08  5628.8  991.43
#Mann= 5 ,-1 , 0
  3890.2     .05       0  4262.1      .1       0    4963     .07       0
  5025.6     .16       0  5104.8     .05       0
#XS Ineff= 2 ,-1
                         4561.36 4907.95  988.04
Permanent Ineff=
       F       T
Bank Sta=4973.3,5045.6
XS Rating Curve= 0 ,0
Exp/Cntr=0.3,0.1

Type RM Length L Ch R = 1 ,4965    ,36,36,36
BEGIN DESCRIPTION:
UNT 1060 IN LATR 11.0
END DESCRIPTION:
XS GIS Cut Line= 4
      2945767.83     10094131.58      2945376.92     10093388.18
      2945220.67     10093313.53      2944684.25     10093198.95
#Sta/Elev= 30
  4099.4  991.18  4342.5   986.7  4430.7  986.17  4469.1  986.28  4474.7  986.99
  4518.8  985.62    4629  984.74  4651.1  983.92  4689.5  980.48  4777.7  984.12
  4799.7  984.48    4855   983.2  4904.3  982.39    4933  980.76  4957.7  979.79
  4970.8  978.33  5000.1  977.66  5002.8  977.16  5006.1  977.66    5054  979.98
    5092  980.95  5145.4  983.38  5231.8  984.58    5287  986.09  5298.3  986.27
  5419.5  986.07  5462.4  987.48  5546.9  988.07  5553.8  988.16    5661  989.47
#Mann= 9 ,-1 , 0
  4099.4     .05       0    4855     .16       0  5000.1     .07       0
  5006.1     .16       0    5092     .05       0    5287     .16       0
  5298.3     .05       0  5546.9      .1       0  5553.8     .05       0
#XS Ineff= 1 ,-1
 4583.98 4802.84  984.31
Permanent Ineff=
       T
Bank Sta=4933,5092
XS Rating Curve= 0 ,0
Exp/Cntr=0.3,0.1

Type RM Length L Ch R = 1 ,4929    ,23,23,23
BEGIN DESCRIPTION:
Mapping XS ca4aee55
END DESCRIPTION:
XS GIS Cut Line= 4
       2945880.7     10094070.86      2945397.97     10093355.63
      2945252.13     10093291.39      2944672.03     10093166.71
#Sta/Elev= 30
  4071.8  989.64  4115.5     988  4142.6  988.65  4316.4  985.33  4403.3  984.43
  4547.2  985.02  4598.1  982.76  4604.2  983.28  4625.2  983.09  4655.1  981.07
  4697.1  979.88    4706  979.83    4727  983.67  4748.4  984.29  4864.6  982.77
  4927.9  980.41  4966.9  979.38  4994.8  977.83  4997.6  977.33  5000.8  977.83
  5027.2   978.9  5078.8  980.34  5098.5  980.74  5128.5  982.79    5241  984.73
  5281.9  986.49  5384.2   985.8  5547.6  987.98  5659.2  989.04  5687.4  989.89
#Mann= 7 ,-1 , 0
  4071.8     .05       0  4748.4     .16       0  4994.8     .07       0
  5000.8     .16       0  5027.2     .05       0  5547.6      .1       0
  5659.2     .05       0
#XS Ineff= 2 ,-1
 4306.82 4522.61  985.18 4561.48 4747.61  984.38
Permanent Ineff=
       F       T
Bank Sta=4927.9,5078.8
XS Rating Curve= 0 ,0
Exp/Cntr=0.3,0.1

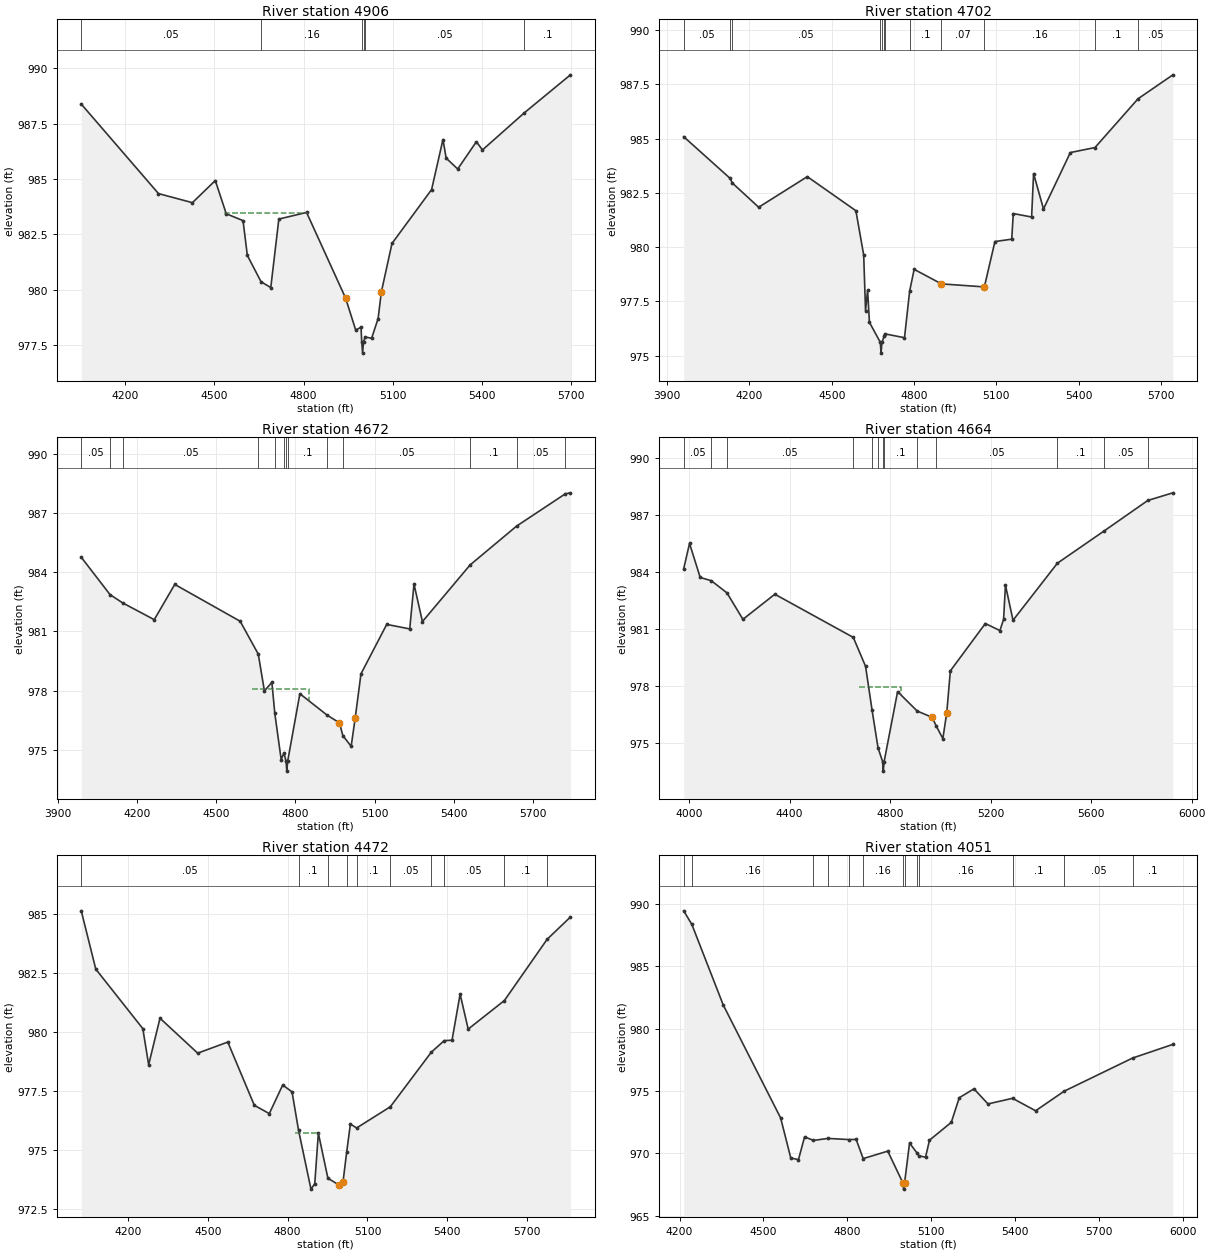
Type RM Length L Ch R = 1 ,4906    ,204,204,204
BEGIN DESCRIPTION:
Mapping XS fd9635ad
END DESCRIPTION:
XS GIS Cut Line= 4
      2945944.91      10094030.9      2945411.85     10093336.53
       2945250.4     10093265.35      2944669.07     10093138.67
#Sta/Elev= 30
  4051.8  988.38  4311.8  984.34    4426  983.93    4503  984.93  4539.9  983.43
  4596.4  983.12  4610.9  981.55  4657.1  980.36  4689.8   980.1  4716.9  983.19
  4810.3  983.49  4941.4  979.63  4975.7  978.18  4993.5  978.31    4996  977.64
  4998.8  977.14    5002  977.64  5007.2  977.87  5029.2  977.81  5051.1   978.7
    5062   979.9  5097.8  982.09  5231.1  984.52  5269.4  986.78  5280.2  985.94
    5319  985.45  5381.9  986.68  5402.4  986.31  5543.7  987.99  5698.6   989.7
#Mann= 6 ,-1 , 0
  4051.8     .05       0  4657.1     .16       0    4996     .07       0
    5002     .16       0  5007.2     .05       0  5543.7      .1       0
#XS Ineff= 2 ,-1
 4267.95  4504.2  984.74  4530.8 4812.05  983.48
Permanent Ineff=
       F       T
Bank Sta=4941.4,5062
XS Rating Curve= 0 ,0
Exp/Cntr=0.3,0.1

Type RM Length L Ch R = 1 ,4702    ,30,30,30
BEGIN DESCRIPTION:
Mapping XS 8a790e55
END DESCRIPTION:
XS GIS Cut Line= 5
      2946123.72     10093874.64      2945481.73     10093161.83
      2945364.55     10093083.71      2945175.74     10092988.22
      2944704.78     10092993.65
#Sta/Elev= 30
  3960.6  985.09  4129.8  983.17  4137.6  982.96  4233.8  981.84    4411  983.25
  4588.1  981.68  4616.5  979.64  4623.2  977.08  4630.7  978.02  4637.4  976.54
    4677  975.62  4679.8  975.12    4683  975.62  4691.5  975.91    4693  976.01
  4765.2  975.83    4784  977.98  4800.4  978.98  4899.8  978.31  5056.2  978.17
  5094.7  980.26    5156  980.37  5161.6  981.55  5228.4  981.39  5235.6  983.39
  5271.7  981.76  5369.6  984.36  5459.3  984.59  5616.5  986.84  5743.3  987.94
#Mann= 12 ,-1 , 0
  3960.6     .05       0  4129.8      .1       0  4137.6     .05       0
    4677    .035       0    4683     .05       0  4691.5      .1       0
    4693     .16       0    4784      .1       0  4899.8     .07       0
  5056.2     .16       0  5459.3      .1       0  5616.5     .05       0
#XS Ineff= 2 ,-1
 4025.57 4390.62  982.99  4562.5 4799.72  978.78
Permanent Ineff=
       F       T
Bank Sta=4899.8,5056.2
XS Rating Curve= 0 ,0
Exp/Cntr=0.3,0.1

Type RM Length L Ch R = 1 ,4672    ,8,8,8
BEGIN DESCRIPTION:
Mapping XS 0c616d35
END DESCRIPTION:
XS GIS Cut Line= 4
      2946132.42     10093810.42      2945514.29     10093137.96
      2945206.13     10092968.69      2944618.45     10092933.75
#Sta/Elev= 30
  3988.4  984.77  4097.6  982.87  4145.5  982.45    4265   981.6  4342.7  983.39
  4590.5  981.52  4659.2  979.85  4682.4  977.98  4710.7  978.42  4721.8  976.84
  4745.9   974.5  4756.5  974.83  4764.5  974.41  4767.2  973.91  4770.5  974.41
  4816.8  977.84  4919.3  976.76  4966.8  976.36  4979.7  975.71  5011.1  975.17
  5026.5  976.61  5048.3  978.85  5145.9  981.36  5233.1  981.13  5249.2  983.41
  5281.1   981.5  5461.9  984.38  5637.9  986.35  5822.6  987.99  5842.1  988.04
#Mann= 13 ,-1 , 0
  3988.4     .05       0  4097.6      .1       0  4145.5     .05       0
  4659.2      .1       0  4721.8     .16       0  4756.5      .1       0
  4764.5    .035       0  4770.5      .1       0  4919.3     .16       0
  4979.7     .05       0  5461.9      .1       0  5637.9     .05       0
  5822.6      .1       0
#XS Ineff= 2 ,-1
 4011.36 4346.59  982.99 4633.52 4850.85  978.06
Permanent Ineff=
       F       T
Bank Sta=4966.8,5026.5
XS Rating Curve= 0 ,0
Exp/Cntr=0.3,0.1

Type RM Length L Ch R = 1 ,4664    ,192,192,192
BEGIN DESCRIPTION:
Mapping XS bd0099ce
END DESCRIPTION:
XS GIS Cut Line= 4
      2946148.05     10093806.96      2945521.88     10093135.79
      2945215.89     10092955.67      2944543.78     10092907.71
#Sta/Elev= 30
  3978.6  984.17  4001.8   985.5  4044.3  983.71  4088.5  983.54  4150.8   982.9
  4214.3  981.51  4341.3  982.83  4653.5  980.56  4702.3  979.04  4728.3  976.73
    4752  974.75  4770.2  974.03  4772.9  973.53  4776.2  974.03  4829.8  977.71
  4907.7  976.69  4966.9  976.36  4984.1  975.89  5009.9  975.24  5025.5  976.61
  5039.7   978.8    5179  981.29    5237  980.92  5251.6  981.51    5259  983.31
  5289.1  981.46  5465.7  984.46    5650  986.14  5825.6  987.76  5925.4  988.16
#Mann= 13 ,-1 , 0
  3978.6     .05       0  4088.5      .1       0  4150.8     .05       0
  4653.5      .1       0  4728.3     .16       0    4752      .1       0
  4770.2    .035       0  4776.2      .1       0  4907.7     .16       0
  4984.1     .05       0  5465.7      .1       0    5650     .05       0
  5825.6      .1       0
#XS Ineff= 2 ,-1
 4019.89 4355.11  982.63 4677.56 4843.75  977.95
Permanent Ineff=
       F       T
Bank Sta=4966.9,5025.5
XS Rating Curve= 0 ,0
Exp/Cntr=0.3,0.1

Type RM Length L Ch R = 1 ,4472    ,421,421,421
BEGIN DESCRIPTION:
UNT 1060 IN LATR 10.0
END DESCRIPTION:
XS GIS Cut Line= 4
      2946261.93     10093706.96      2945814.03     10093191.35
      2945418.19     10092842.39      2944798.72     10092748.69
#Sta/Elev= 30
  4025.1  985.14  4079.7  982.67  4256.3  980.15  4278.2  978.62  4320.8  980.59
  4462.4  979.11  4575.4  979.58  4675.1   976.9  4731.3  976.55  4781.6  977.76
  4816.7  977.47    4841  975.85  4887.8  973.35    4902  973.58  4915.5  975.72
  4951.4  973.81  4994.1  973.52  5008.3  973.67  5022.1  974.94  5035.9  976.11
  5059.1  975.94  5185.9  976.84  5339.6  979.15  5388.1  979.64  5417.5  979.66
  5447.9  981.61  5478.2  980.13  5614.2  981.34  5774.4  983.93  5862.3  984.88
#Mann= 10 ,-1 , 0
  4025.1     .05       0    4841      .1       0  4951.4    .035       0
  5022.1     .05       0  5059.1      .1       0  5185.9     .05       0
  5339.6      .1       0  5388.1     .05       0  5614.2      .1       0
  5774.4     .05       0
#XS Ineff= 3 ,-1
 4163.64 4318.18  980.25                         4828.41 4917.05  975.71
Permanent Ineff=
       F       F       T
Bank Sta=4994.1,5008.3
XS Rating Curve= 0 ,0
Exp/Cntr=0.3,0.1

Type RM Length L Ch R = 1 ,4051    ,326,326,326
BEGIN DESCRIPTION:
UNT 1060 IN LATR 9.0
END DESCRIPTION:
XS GIS Cut Line= 3
      2946398.69     10093192.68      2945624.36     10092525.98
      2944898.66     10092480.84
#Sta/Elev= 30
    4215  989.46  4244.1  988.37  4356.4   981.9  4561.6  972.83  4597.8  969.62
  4625.3  969.49  4647.2  971.32    4679  971.03  4730.8  971.19  4804.6   971.1
  4831.5  971.11  4856.7  969.57  4944.5  970.17  4998.6  967.62  5001.3  967.12
  5004.6  967.62  5022.4  970.82  5047.9  970.06  5055.9   969.8  5079.5  969.68
  5093.7  971.05  5171.6  972.48  5200.2  974.46  5252.7  975.17  5302.8  973.96
  5390.6  974.41  5473.1  973.41    5575  974.98  5819.5  977.64  5963.9  978.74
#Mann= 13 ,-1 , 0
    4215      .1       0  4244.1     .16       0    4679      .1       0
  4730.8     .16       0  4804.6      .1       0  4856.7     .16       0
  4998.6     .07       0  5004.6     .16       0  5047.9      .1       0
  5055.9     .16       0  5390.6      .1       0    5575     .05       0
  5819.5      .1       0
Bank Sta=4998.6,5004.6
XS Rating Curve= 0 ,0
Exp/Cntr=0.3,0.1