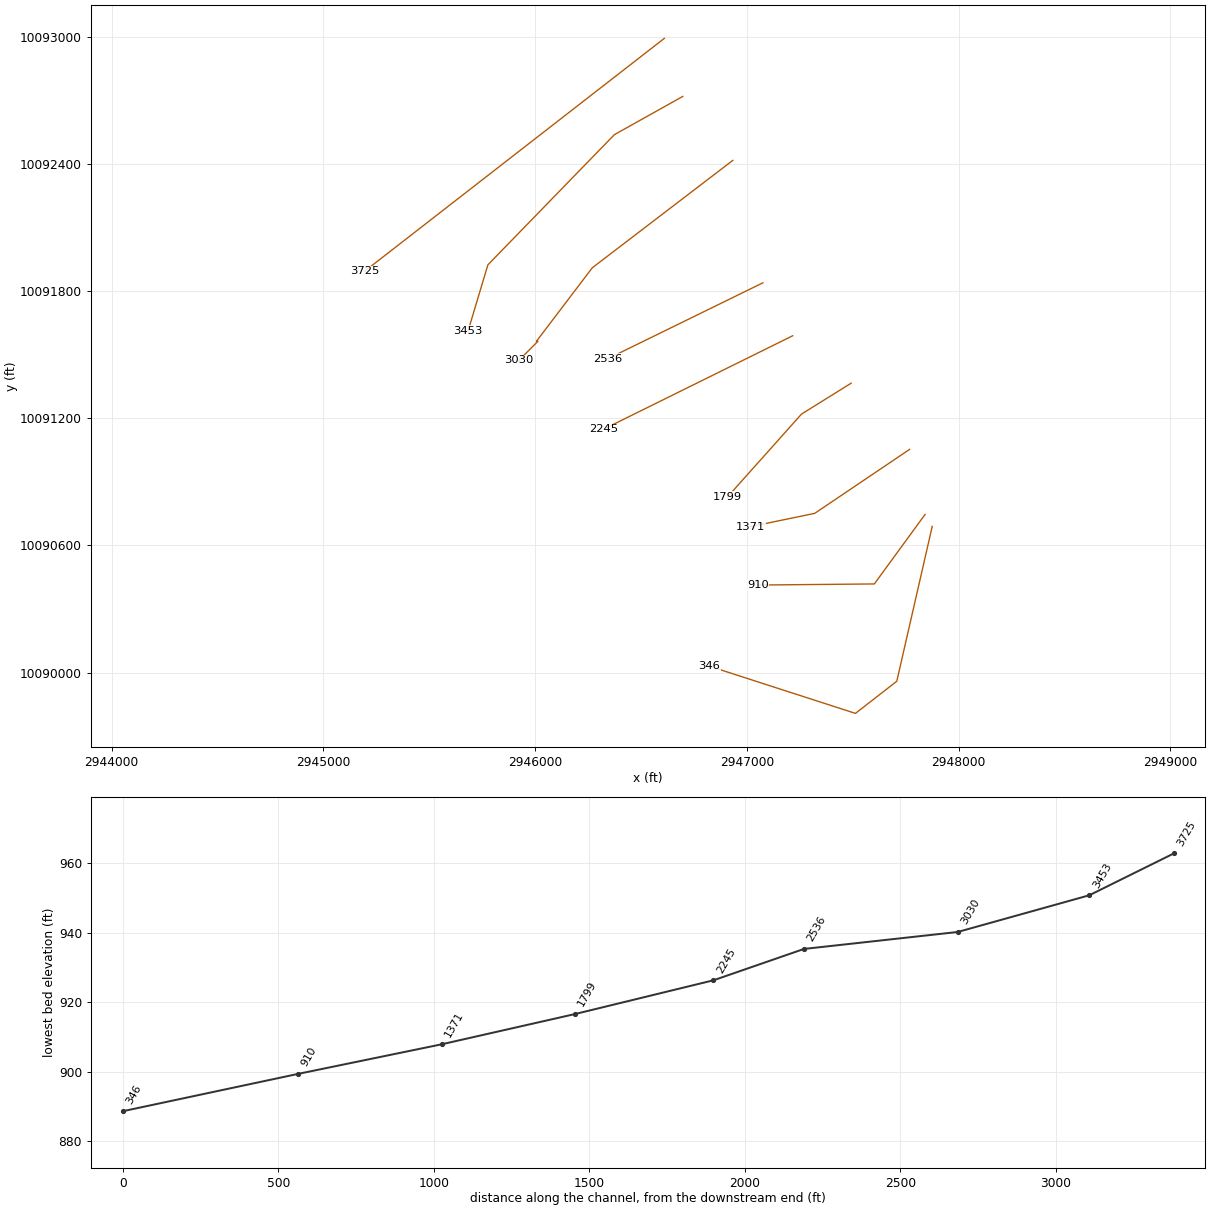
HEC-RAS study UNT 0060 IN LATR.prj: UNT 1060 IN LATR Base Level Engineering

--- UNT 0060 IN LATR.g01 (geometry) --- (continued)

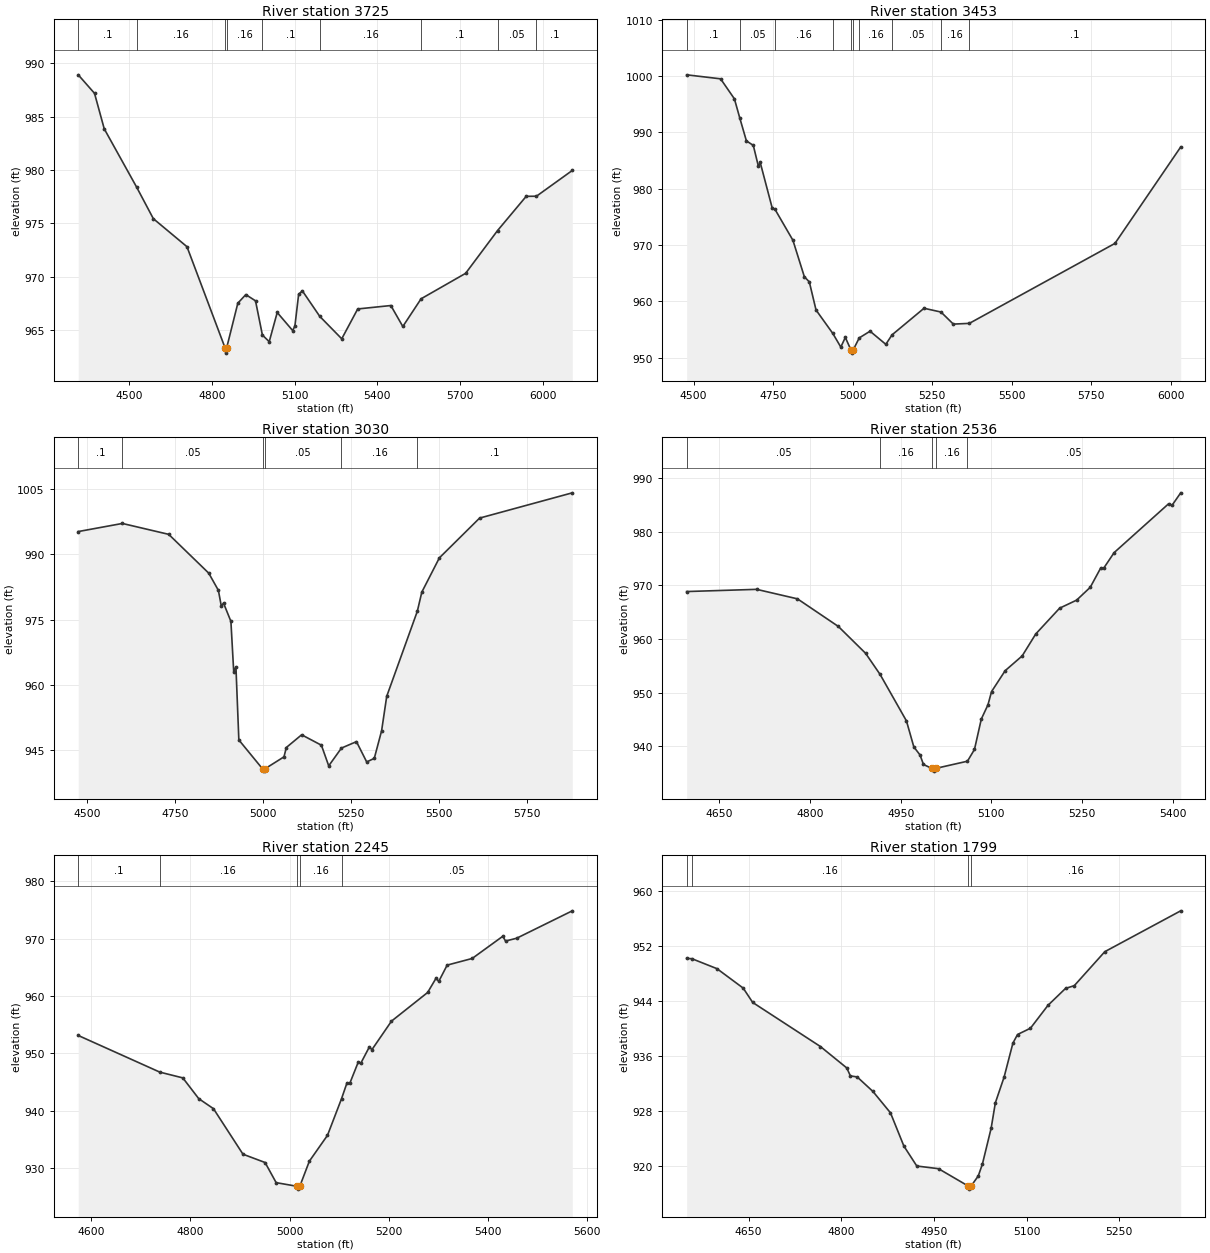
Type RM Length L Ch R = 1 ,3725    ,272,272,272
BEGIN DESCRIPTION:
Mapping XS 6e2d1cf6
END DESCRIPTION:
XS GIS Cut Line= 2
      2946610.45     10092994.72      2945193.79     10091894.03
#Sta/Elev= 30
  4314.2   988.9  4373.3  987.17  4408.6  983.85  4526.4  978.39  4586.9  975.45
    4709  972.83  4847.2  963.38    4850  962.88  4853.2  963.38  4893.7  967.55
  4922.6  968.35  4957.9  967.77  4982.9  964.57  5007.7  963.95  5036.7  966.68
  5092.8  964.99  5100.9  965.41  5114.5  968.38  5128.1   968.7  5191.1  966.32
    5271  964.22    5329  967.01  5449.3  967.33  5492.8  965.37  5559.1  967.96
  5720.8  970.34  5836.8  974.34  5940.8  977.54    5978  977.55  6108.2  979.96
#Mann= 9 ,-1 , 0
  4314.2      .1       0  4526.4     .16       0  4847.2     .07       0
  4853.2     .16       0  4982.9      .1       0  5191.1     .16       0
  5559.1      .1       0  5836.8     .05       0    5978      .1       0
Bank Sta=4847.2,4853.2
XS Rating Curve= 0 ,0
Exp/Cntr=0.3,0.1

Type RM Length L Ch R = 1 ,3453    ,423,423,423
BEGIN DESCRIPTION:
UNT 1060 IN LATR 8.0
END DESCRIPTION:
XS GIS Cut Line= 4
      2946697.31     10092720.44      2946374.36     10092539.87
      2945777.14     10091925.29      2945683.42     10091612.91
#Sta/Elev= 30
  4478.2  1000.2  4584.9  999.49  4628.3  995.94  4645.6  992.46    4666  988.48
  4687.7  987.68  4703.7  983.97  4709.4  984.66  4747.1  976.58  4756.1  976.31
  4812.2  970.85  4848.2  964.37  4863.8  963.46  4884.9  958.47  4937.7  954.31
  4962.8  951.89    4977  953.61  4995.1  951.32  4997.8  950.82  5001.1  951.32
  5020.7  953.52  5054.7  954.71  5104.3  952.38  5123.8  954.06  5224.4  958.78
  5277.7  958.11  5316.5  955.97  5366.8   956.1  5824.6  970.29  6031.3   987.4
#Mann= 10 ,-1 , 0
  4478.2      .1       0  4645.6     .05       0  4756.1     .16       0
  4937.7     .05       0  4995.1    .035       0  5001.1     .05       0
  5020.7     .16       0  5123.8     .05       0  5277.7     .16       0
  5366.8      .1       0
Bank Sta=4995.1,5001.1
XS Rating Curve= 0 ,0
Exp/Cntr=0.3,0.1

Type RM Length L Ch R = 1 ,3030    ,494,494,494
BEGIN DESCRIPTION:
Mapping XS ad942a44
END DESCRIPTION:
XS GIS Cut Line= 5
      2946933.41     10092418.36      2946270.19      10091911.4
       2946006.3     10091564.18      2946013.25     10091564.18
       2945923.2     10091474.13
#Sta/Elev= 30
  4474.8  995.24  4600.3   997.1  4732.1   994.6    4846  985.69  4873.4  981.74
  4881.7  978.13    4888  978.82    4909  974.63    4917  963.04  4923.3  964.18
  4931.6  947.41  4999.2  940.75    5002  940.25  5005.2  940.75    5060  943.53
  5066.6  945.67  5110.2  948.59  5166.4   946.2  5187.2  941.46  5223.4  945.54
  5266.1  947.02  5295.2  942.36  5316.8  943.18  5337.6   949.5  5352.2  957.43
  5439.2  976.94    5452  981.34  5501.9   989.2  5616.3  998.33    5880 1004.13
#Mann= 6 ,-1 , 0
  4474.8      .1       0  4600.3     .05       0  4999.2    .035       0
  5005.2     .05       0  5223.4     .16       0  5439.2      .1       0
Bank Sta=4999.2,5005.2
XS Rating Curve= 0 ,0
Exp/Cntr=0.3,0.1

Type RM Length L Ch R = 1 ,2536    ,291,291,291
BEGIN DESCRIPTION:
UNT 1060 IN LATR 6.0
END DESCRIPTION:
XS GIS Cut Line= 2
      2947075.67     10091840.34      2946342.37     10091481.48
#Sta/Elev= 30
  4596.4  968.84    4712  969.25  4779.5  967.48    4847  962.34  4892.1  957.33
  4916.1  953.38  4959.6  944.73  4971.8  939.88  4982.1  938.37  4987.7  936.61
  5001.6  935.87  5004.4  935.37  5007.6  935.87  5060.4  937.22    5072  939.41
  5083.3  945.08  5094.3  947.73  5100.2  950.19  5122.7  954.09  5150.8  956.84
  5173.3  960.94  5212.7  965.74  5240.8  967.24  5263.3  969.63  5280.3  973.17
  5285.8  973.24  5302.8   976.1  5392.8   985.2  5398.4   984.9  5412.8  987.24
#Mann= 5 ,-1 , 0
  4596.4     .05       0  4916.1     .16       0  5001.6     .07       0
  5007.6     .16       0  5060.4     .05       0
Bank Sta=5001.6,5007.6
XS Rating Curve= 0 ,0
Exp/Cntr=0.3,0.1

Type RM Length L Ch R = 1 ,2245    ,446,446,446
BEGIN DESCRIPTION:
UNT 1060 IN LATR 5.0
END DESCRIPTION:
XS GIS Cut Line= 2
      2947216.29     10091590.33      2946323.11     10091148.94
#Sta/Elev= 30
  4573.8  953.14  4738.2  946.75  4784.7  945.74  4816.8  942.12  4846.5  940.37
    4906  932.43  4950.6  930.98  4972.9  927.47  5014.6  926.84  5017.3  926.34
  5020.6  926.84  5039.9  931.22  5076.4  935.72  5104.7   942.1  5115.8  944.89
  5121.3  944.77  5138.2  948.44  5143.8  948.33  5160.6   951.1  5166.2  950.69
  5205.5  955.64  5278.4  960.64  5295.3  963.12  5300.8  962.57  5317.7  965.41
  5368.2  966.57  5429.9  970.44  5435.5  969.61  5457.9   970.1  5570.1  974.88
#Mann= 5 ,-1 , 0
  4573.8      .1       0  4738.2     .16       0  5014.6     .07       0
  5020.6     .16       0  5104.7     .05       0
Bank Sta=5014.6,5020.6
XS Rating Curve= 0 ,0
Exp/Cntr=0.3,0.1

Type RM Length L Ch R = 1 ,1799    ,428,428,428
BEGIN DESCRIPTION:
UNT 1060 IN LATR 4.0
END DESCRIPTION:
XS GIS Cut Line= 3
      2947492.38      10091366.4      2947257.99     10091220.56
        2946909.      10090829.9
#Sta/Elev= 30
  4549.6  950.14  4558.1   950.1  4598.7  948.65  4641.2  945.82  4656.5  943.74
  4766.2  937.33  4808.8  934.22  4814.7  933.06  4825.7  932.91  4851.2   930.8
  4879.6  927.69  4901.3  922.86  4922.2  919.96  4957.4  919.57  5004.5   917.1
  5007.3   916.6  5010.5   917.1  5021.7  918.51  5028.4  920.23  5042.6  925.46
  5049.4  929.15  5063.5  932.87  5077.8  937.82  5085.3  939.08  5106.2  939.99
  5134.6  943.32    5163  945.78  5177.2  946.18  5226.6  951.12  5349.5  957.06
#Mann= 4 ,-1 , 0
  4549.6      .1       0  4558.1     .16       0  5004.5     .07       0
  5010.5     .16       0
Bank Sta=5004.5,5010.5
XS Rating Curve= 0 ,0
Exp/Cntr=0.3,0.1

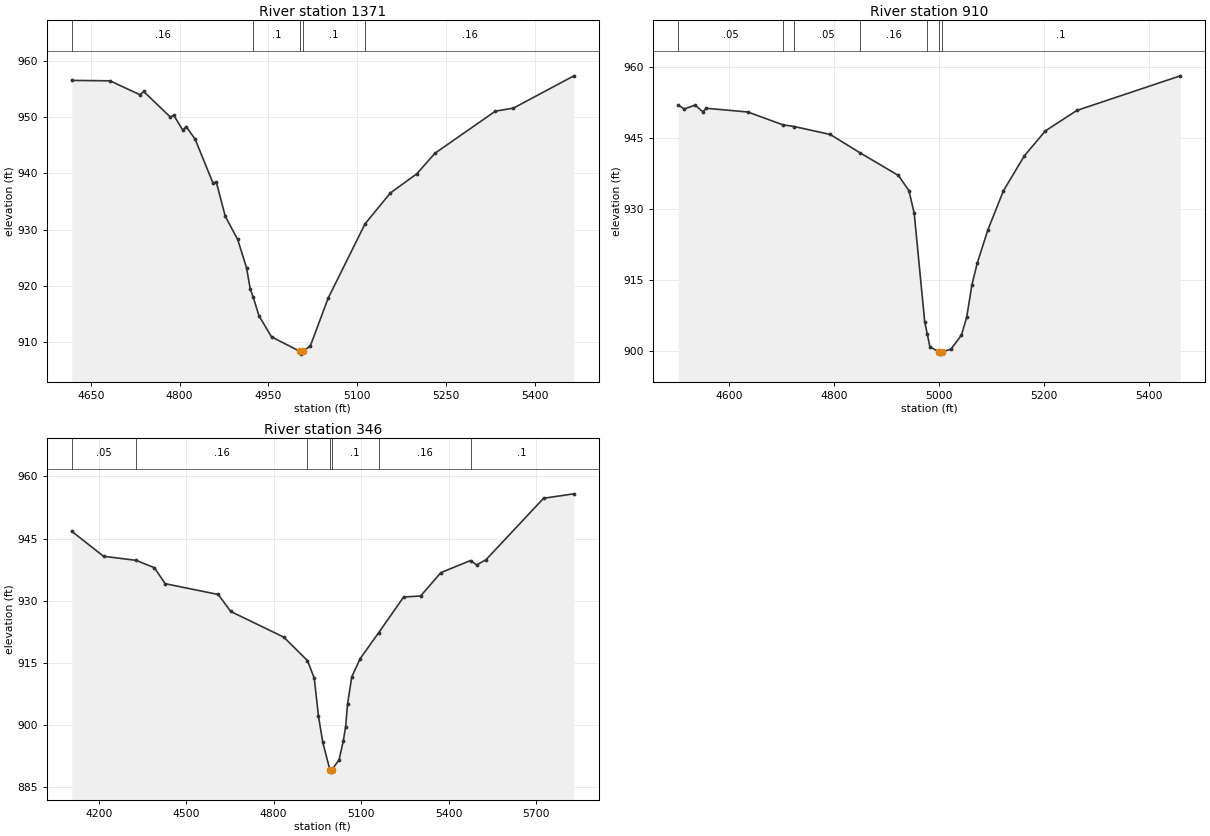
Type RM Length L Ch R = 1 ,1371    ,461,461,461
BEGIN DESCRIPTION:
UNT 1060 IN LATR 3.0
END DESCRIPTION:
XS GIS Cut Line= 3
       2947768.4     10091053.89      2947320.49     10090751.81
      2947018.44     10090689.32
#Sta/Elev= 30
  4617.7  956.53  4682.3  956.45  4733.2  953.97  4739.2  954.56  4784.2  950.03
  4790.2  950.33  4805.2   947.7  4811.2   948.3  4826.2  946.09  4856.1  938.36
  4862.2  938.39  4877.1  932.39  4898.1  928.27  4913.1  923.23  4919.2  919.54
  4924.5  917.98  4934.1  914.71  4955.3  910.97  5003.1   908.4  5005.8   907.9
  5009.1   908.4    5021  909.38    5051  917.83  5113.4  931.05  5156.2  936.53
  5200.9  939.94  5231.5  943.58  5333.6  951.06  5364.3  951.61  5466.4  957.34
#Mann= 5 ,-1 , 0
  4617.7     .16       0  4924.5      .1       0  5003.1     .07       0
  5009.1      .1       0  5113.4     .16       0
Bank Sta=5003.1,5009.1
XS Rating Curve= 0 ,0
Exp/Cntr=0.3,0.1

Type RM Length L Ch R = 1 ,910     ,564,564,564
BEGIN DESCRIPTION:
UNT 1060 IN LATR 2.0
END DESCRIPTION:
XS GIS Cut Line= 3
      2947841.34     10090746.62      2947601.74     10090418.47
      2947051.58     10090413.28
#Sta/Elev= 30
  4502.9  951.94  4514.5  951.11  4535.3  951.91    4550  950.49  4556.2  951.25
  4635.7  950.46  4701.9  947.77  4723.8   947.4  4792.5  945.72  4849.4  941.85
  4922.5  937.07  4942.5  933.86  4952.5   929.1  4972.5  906.23  4977.2  903.73
  4982.5  900.92  4999.5  899.89  5002.2  899.39  5005.5  899.89  5022.5  900.43
  5042.5   903.4  5052.5   907.2  5062.5  914.03  5072.5  918.54  5092.5   925.5
  5122.5  933.85  5162.5  941.24  5202.5  946.49  5262.5   950.8  5459.4  958.09
#Mann= 7 ,-1 , 0
  4502.9     .05       0  4701.9     .16       0  4723.8     .05       0
  4849.4     .16       0  4977.2      .1       0  4999.5     .07       0
  5005.5      .1       0
Bank Sta=4999.5,5005.5
XS Rating Curve= 0 ,0
Exp/Cntr=0.3,0.1

Type RM Length L Ch R = 1 ,346     ,0,0,0
BEGIN DESCRIPTION:
UNT 1060 IN LATR 1.0
END DESCRIPTION:
XS GIS Cut Line= 4
      2947875.13      10090690.1      2947707.86     10089959.09
      2947512.72     10089807.31      2946822.71     10090030.09
#Sta/Elev= 30
  4107.7  946.76  4216.8  940.73  4328.6  939.75  4391.2  937.97    4428  934.12
    4610  931.51    4653  927.41    4835  921.21  4916.1  915.55  4939.4   911.3
  4953.9  902.12  4968.4  895.88  4993.2  889.13  4995.9  888.63  4999.2  889.13
  5024.5  891.62  5038.9  896.15  5046.9  899.54  5053.4     905  5067.9  911.61
  5096.9  916.03  5159.8  922.24  5245.9  930.91  5304.2  931.15  5373.5  936.78
  5475.3  939.71  5496.4  938.64  5528.5  939.91  5725.9  954.74  5829.9  955.81
#Mann= 7 ,-1 , 0
  4107.7     .05       0  4328.6     .16       0  4916.1      .1       0
  4993.2     .07       0  4999.2      .1       0  5159.8     .16       0
  5475.3      .1       0
Bank Sta=4993.2,4999.2
XS Rating Curve= 0 ,0
Exp/Cntr=0.3,0.1

Chan Stop Cuts=-1
Use User Specified Reach Order=0
Composite Channel Slope=5