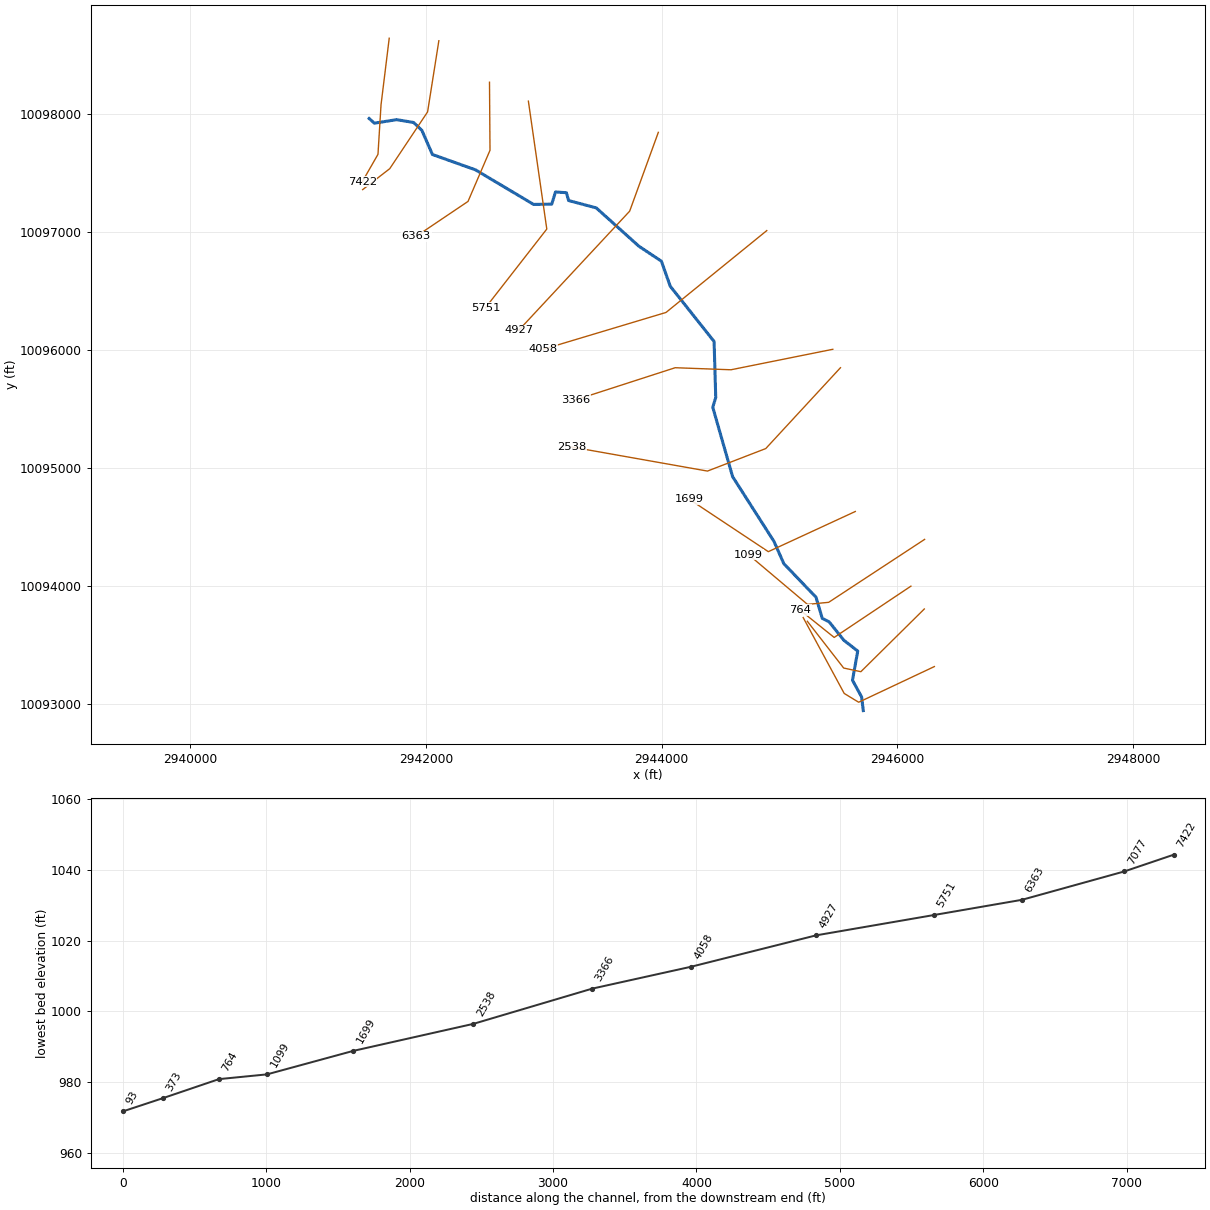
--- UNT 0061 IN LATR.prj (project) ---

Proj Title=UNT 1061 IN LATR Base Level Engineering
Current Plan=p01
Default Exp/Contr=0.3,0.1
English Units
Geom File=g01
Flow File=f01
Plan File=p01
BEGIN DESCRIPTION:
UNT 1061 IN LATR
END DESCRIPTION:

--- UNT 0061 IN LATR.p01 (plan) ---

Plan Title=Multiple Run
Short Identifier=Multiple
Geom File=g01
Flow File=f01
Subcritical Flow
K Sum by GR= 0
Std Step Tol= 0.01
Critical Tol= 0.01
Num of Std Step Trials= 20
Max Error Tol= 0.3
Flow Tol Ratio= 0.001
Split Flow NTrial= 30
Split Flow Tol= 0.02
Split Flow Ratio= 0.02
Log Output Level= 0
Friction Slope Method= 1
Unsteady Friction Slope Method= 2
Unsteady Bridges Friction Slope Method= 1
Parabolic Critical Depth
Global Vel Dist=  1 , 1 , 1
Global Log Level= 0
CheckData=True
Encroach Param= -1, 0, 0, 0
BEGIN DESCRIPTION:
Multiple Run
END DESCRIPTION:

--- UNT 0061 IN LATR.f01 (steady flow) ---

Flow Title=Multiple
Program Version=4.10
Number of Profiles= 7
Profile Names=10-year,25-year,50-year,1pct_min,100-year,1pct_plu,500-year
River Rch & RM=UNT 1061 IN LATR,Reach-1         ,7422
    1379    2051    2649    2501    3383    4575    5541
Boundary for River Rch & Prof#=UNT 1061 IN LATR,Reach-1         , 1
Up Type= 0
Dn Type= 3
Dn Slope=0.0134
Boundary for River Rch & Prof#=UNT 1061 IN LATR,Reach-1         , 2
Up Type= 0
Dn Type= 3
Dn Slope=0.0134
Boundary for River Rch & Prof#=UNT 1061 IN LATR,Reach-1         , 3
Up Type= 0
Dn Type= 3
Dn Slope=0.0134
Boundary for River Rch & Prof#=UNT 1061 IN LATR,Reach-1         , 4
Up Type= 0
Dn Type= 3
Dn Slope=0.0134
Boundary for River Rch & Prof#=UNT 1061 IN LATR,Reach-1         , 5
Up Type= 0
Dn Type= 3
Dn Slope=0.0134
Boundary for River Rch & Prof#=UNT 1061 IN LATR,Reach-1         , 6
Up Type= 0
Dn Type= 3
Dn Slope=0.0134
Boundary for River Rch & Prof#=UNT 1061 IN LATR,Reach-1         , 7
Up Type= 0
Dn Type= 3
Dn Slope=0.0134
DSS Import GetInterval= 0
DSS Import GetPeak= 0
DSS Import FillOption= 0

--- UNT 0061 IN LATR.g01 (geometry) ---

Geom Title=Existing Conditions
Program Version=4.10

River Reach=UNT 1061 IN LATR,Reach-1
Reach XY= 30
      2941518.47     10097963.73      2941563.05     10097924.13
      2941751.75     10097954.11      2941896.18     10097930.08
      2941965.98     10097862.88      2942055.46      10097658.5
      2942420.91     10097528.28      2942913.18     10097235.33
      2943067.25     10097237.28      2943099.36     10097340.42
      2943191.55     10097334.69      2943210.82      10097267.9
      2943444.99     10097205.65      2943807.36     10096880.14
      2943997.79      10096753.5      2944073.04     10096540.91
      2944444.83     10096072.28      2944458.87     10095596.86
      2944433.66     10095514.71      2944602.17     10094925.27
      2944953.04     10094376.28      2945036.55     10094187.64
      2945309.59      10093902.9       2945362.5     10093723.85
      2945421.62     10093693.65      2945545.46     10093538.23
      2945663.48     10093446.34      2945618.78     10093198.98
      2945696.27      10093057.8      2945710.75     10092941.41

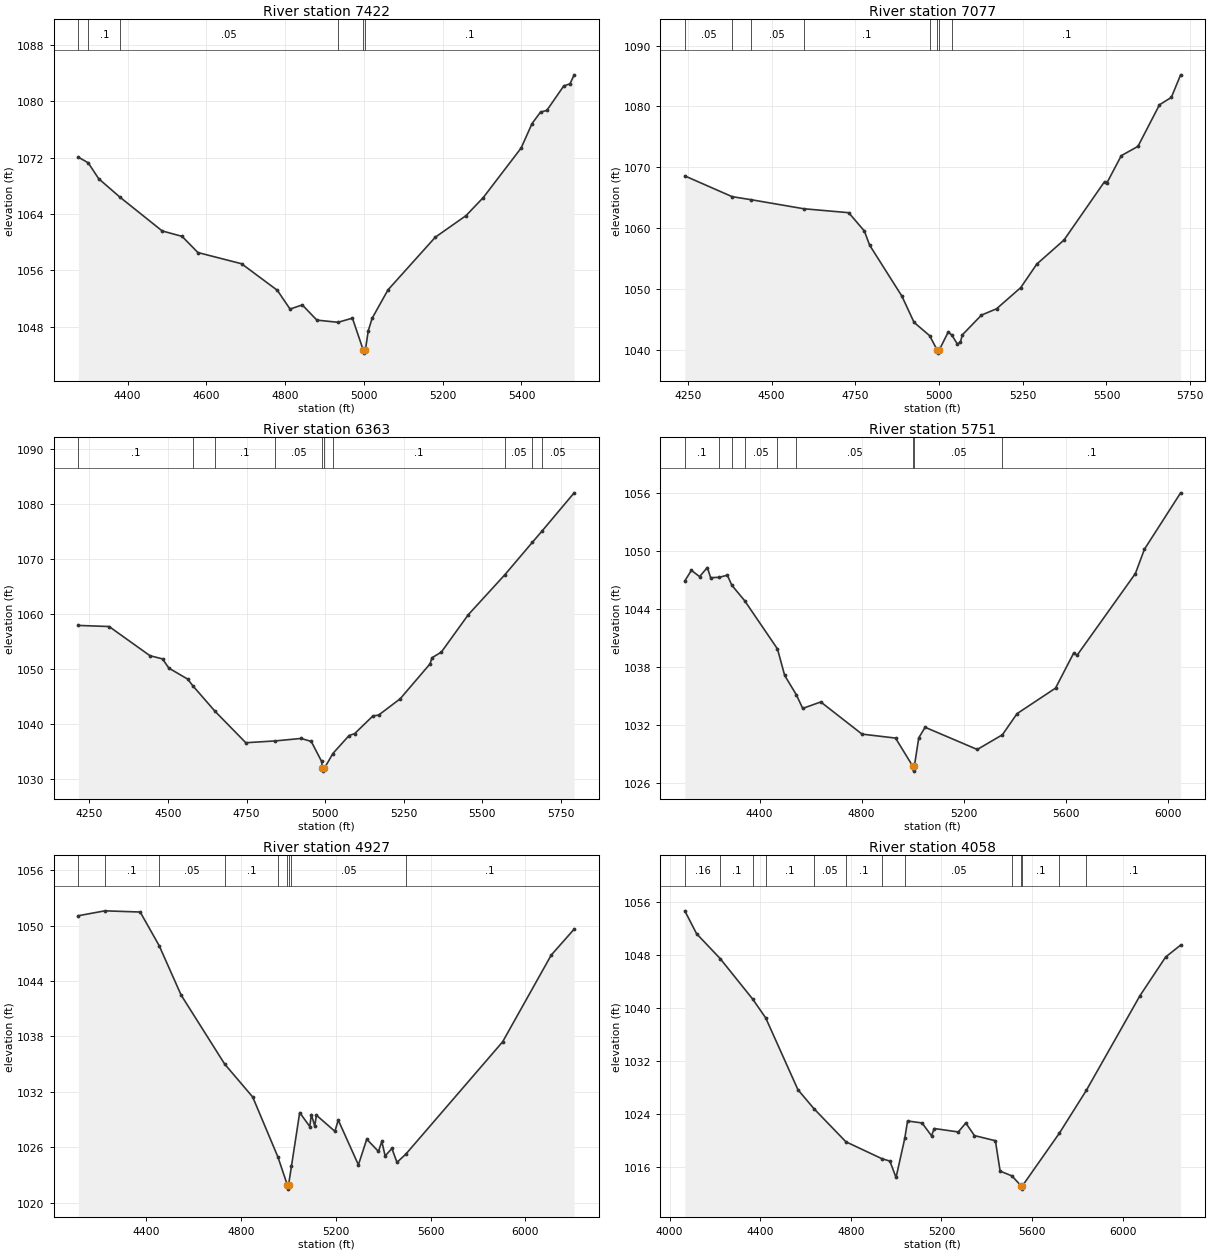
Type RM Length L Ch R = 1 ,7422    ,345,345,345
BEGIN DESCRIPTION:
UNT 1061 IN LATR 14.0
END DESCRIPTION:
XS GIS Cut Line= 4
      2941688.77     10098645.04      2941619.32     10098080.77
      2941593.28     10097659.77      2941459.67     10097427.03
#Sta/Elev= 30
    4275 1072.08  4300.1 1071.28  4326.7 1069.02  4381.5 1066.36  4487.9  1061.6
  4538.3 1060.83  4578.6 1058.53  4689.4 1056.94  4780.1 1053.17  4812.5  1050.5
  4843.5 1051.09  4880.6 1048.93  4934.3 1048.62  4970.8 1049.21  4997.9 1044.74
  5000.6 1044.24  5003.9 1044.74  5010.9 1047.39  5020.9  1049.2    5061 1053.22
  5181.2 1060.71  5259.3 1063.78  5303.1 1066.35  5399.1 1073.38  5426.8 1076.86
  5448.4 1078.49  5464.2 1078.72  5507.3  1082.2  5523.1  1082.5  5533.7 1083.78
#Mann= 6 ,-1 , 0
    4275     .05       0  4300.1      .1       0  4381.5     .05       0
  4934.3      .1       0  4997.9     .07       0  5003.9      .1       0
Bank Sta=4997.9,5003.9
XS Rating Curve= 0 ,0
Exp/Cntr=0.3,0.1

Type RM Length L Ch R = 1 ,7077    ,714,714,714
BEGIN DESCRIPTION:
UNT 1061 IN LATR 13.0
END DESCRIPTION:
XS GIS Cut Line= 4
      2942109.78     10098623.35      2942014.29     10098020.01
       2941693.1     10097538.24      2941463.23     10097360.41
#Sta/Elev= 30
  4240.9  1068.6  4382.4 1065.19  4438.1  1064.7  4595.8 1063.21  4730.3 1062.56
  4777.1 1059.55  4792.7 1057.24  4889.3 1048.85  4925.4 1044.56  4972.1 1042.37
  4994.5 1040.01  4997.2 1039.51  5000.5 1040.01  5027.5 1042.98  5038.5 1042.46
  5054.6 1041.01  5063.6 1041.27  5069.6 1042.51  5126.7 1045.75  5171.8 1046.79
  5243.9 1050.26    5292 1054.13  5373.1 1058.07  5494.4 1067.67  5500.8  1067.4
  5544.2 1071.92    5594 1073.45  5658.3 1080.28  5693.6 1081.48  5721.4 1085.19
#Mann= 8 ,-1 , 0
  4240.9     .05       0  4382.4      .1       0  4438.1     .05       0
  4595.8      .1       0  4972.1     .05       0  4994.5    .035       0
  5000.5     .05       0  5038.5      .1       0
Bank Sta=4994.5,5000.5
XS Rating Curve= 0 ,0
Exp/Cntr=0.3,0.1

Type RM Length L Ch R = 1 ,6363    ,612,612,612
BEGIN DESCRIPTION:
UNT 1061 IN LATR 12.0
END DESCRIPTION:
XS GIS Cut Line= 4
      2942539.46     10098271.77       2942543.8     10097694.49
      2942357.17     10097260.46      2941918.81     10096965.33
#Sta/Elev= 30
  4214.7 1057.97  4312.7 1057.77  4442.7 1052.47  4482.7 1051.89  4502.7 1050.22
  4562.7 1048.22  4579.1 1047.01  4649.5 1042.39  4747.7 1036.66  4841.7 1036.99
  4924.1 1037.44  4956.1 1036.89  4988.8 1033.29  4991.8    1032  4994.5  1031.5
  4997.8    1032  5024.7 1034.69  5076.3 1037.96  5094.4 1038.32  5152.4 1041.53
  5170.5 1041.68  5239.1 1044.64  5334.2 1050.99  5340.2 1052.09  5370.2 1053.13
  5455.8 1059.91    5572 1067.16  5660.2 1073.09  5690.7 1075.12  5792.9 1082.06
#Mann= 10 ,-1 , 0
  4214.7      .1       0  4579.1     .05       0  4649.5      .1       0
  4841.7     .05       0  4991.8    .035       0  4997.8     .05       0
  5024.7      .1       0    5572     .05       0  5660.2      .1       0
  5690.7     .05       0
Bank Sta=4991.8,4997.8
XS Rating Curve= 0 ,0
Exp/Cntr=0.3,0.1

Type RM Length L Ch R = 1 ,5751    ,824,824,824
BEGIN DESCRIPTION:
UNT 1061 IN LATR 10.0
END DESCRIPTION:
XS GIS Cut Line= 3
      2942869.33     10098111.11      2943025.57     10097026.08
      2942505.16     10096358.22
#Sta/Elev= 30
  4107.2  1046.9    4133    1048  4165.2 1047.35  4195.5 1048.29  4208.5 1047.24
  4242.7 1047.28  4273.9  1047.5  4291.4 1046.46  4341.4 1044.87  4470.3 1039.87
  4498.6 1037.12  4544.1 1035.13  4569.3 1033.71    4640 1034.38  4801.7 1031.05
    4933 1030.64  5000.7 1027.72  5003.5 1027.22  5006.7 1027.72  5023.9 1030.66
  5048.8 1031.76  5253.2 1029.46  5351.6 1030.98  5409.2 1033.17  5559.9 1035.81
  5630.5 1039.41  5644.9 1039.23  5872.9 1047.67  5908.2 1050.18  6050.1 1056.02
#Mann= 9 ,-1 , 0
  4107.2      .1       0  4242.7     .05       0  4291.4      .1       0
  4341.4     .05       0  4470.3      .1       0  4544.1     .05       0
  5000.7    .035       0  5006.7     .05       0  5351.6      .1       0
Bank Sta=5000.7,5006.7
XS Rating Curve= 0 ,0
Exp/Cntr=0.3,0.1

Type RM Length L Ch R = 1 ,4927    ,869,869,869
BEGIN DESCRIPTION:
UNT 1061 IN LATR 8.0
END DESCRIPTION:
XS GIS Cut Line= 3
      2943971.75      10097846.4      2943728.69     10097177.99
      2942787.78     10096167.71
#Sta/Elev= 30
  4113.6 1051.08  4225.6 1051.61  4374.5 1051.48  4454.6 1047.84  4547.4 1042.48
  4731.1 1035.01  4849.2 1031.45  4955.5 1024.96  4994.7 1021.97  4997.4 1021.47
  5000.7 1021.97  5012.7 1023.95  5047.5 1029.76    5090 1028.25  5096.9 1029.55
    5111 1028.29  5117.9 1029.48    5196 1027.73  5210.2 1028.95  5295.2  1024.1
  5330.4 1026.88  5379.7 1025.55  5393.9 1026.63  5408.1 1025.06  5436.4 1025.88
  5457.9 1024.37  5494.9 1025.25  5903.5 1037.42  6108.7 1046.82  6205.4 1049.63
#Mann= 9 ,-1 , 0
  4113.6     .05       0  4225.6      .1       0  4454.6     .05       0
  4731.1      .1       0  4955.5     .16       0  4994.7     .07       0
  5000.7     .16       0  5012.7     .05       0  5494.9      .1       0
Bank Sta=4994.7,5000.7
XS Rating Curve= 0 ,0
Exp/Cntr=0.3,0.1

Type RM Length L Ch R = 1 ,4058    ,692,692,692
BEGIN DESCRIPTION:
UNT 1061 IN LATR 7.0
END DESCRIPTION:
XS GIS Cut Line= 3
      2944891.88     10097013.06      2944036.85     10096318.62
      2942995.22     10096006.13
#Sta/Elev= 30
  4066.8 1054.74  4118.8 1051.28  4223.3  1047.5  4366.9 1041.37  4424.2 1038.53
  4566.3 1027.68  4637.2  1024.8  4778.1  1019.8  4935.9 1017.26  4972.2 1016.88
  4999.4  1014.4    5038 1020.33  5050.3 1022.95  5114.4 1022.65    5156 1020.71
  5168.2 1021.81  5274.3 1021.29  5307.3 1022.64  5345.6 1020.74  5438.1 1019.96
  5458.9 1015.37  5511.1 1014.64  5551.4 1013.14  5554.2 1012.64  5557.4 1013.14
  5720.5 1021.11  5839.3 1027.57  6076.4 1041.91  6189.8 1047.76  6255.8 1049.56
#Mann= 13 ,-1 , 0
  4066.8     .16       0  4223.3      .1       0  4366.9     .05       0
  4424.2      .1       0  4637.2     .05       0  4778.1      .1       0
  4935.9     .16       0    5038     .05       0  5511.1      .1       0
  5551.4     .07       0  5557.4      .1       0  5720.5     .05       0
  5839.3      .1       0
Bank Sta=5551.4,5557.4
XS Rating Curve= 0 ,0
Exp/Cntr=0.3,0.1

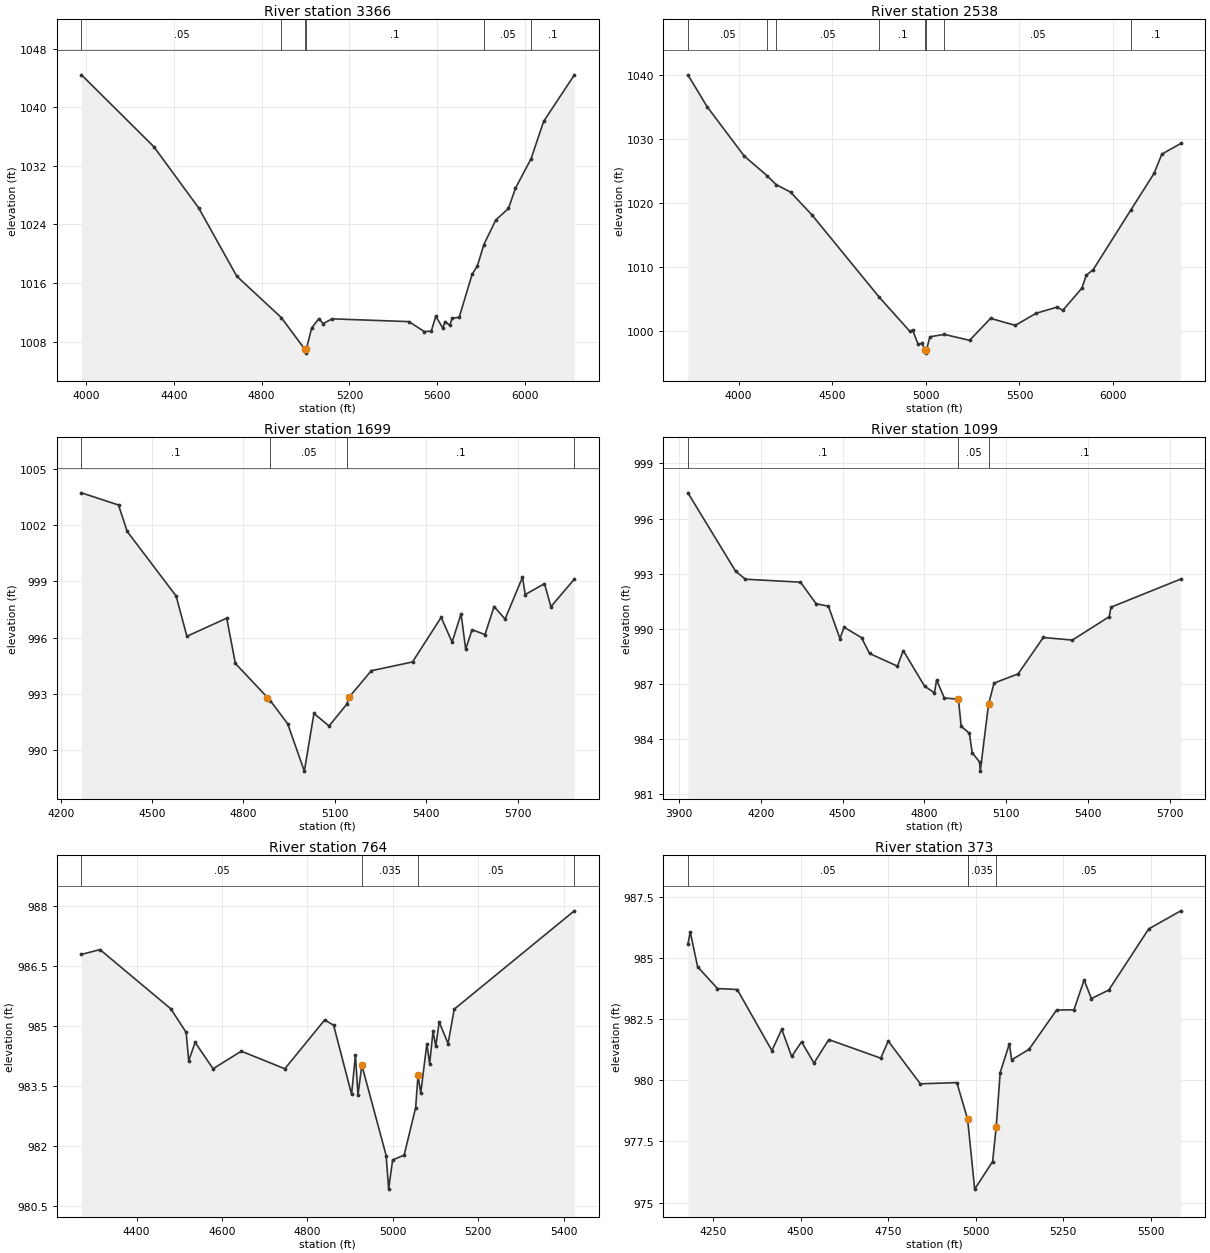
Type RM Length L Ch R = 1 ,3366    ,828,828,828
BEGIN DESCRIPTION:
UNT 1061 IN LATR 5.0
END DESCRIPTION:
XS GIS Cut Line= 4
      2945451.74     10096006.11      2944588.07     10095832.51
      2944114.98     10095849.87      2943268.61     10095576.43
#Sta/Elev= 30
  3979.7 1044.42  4309.4 1034.61  4513.4 1026.26  4686.8 1016.94  4889.7 1011.29
  4997.3 1006.94  5000.1 1006.44  5003.3 1006.94  5027.9 1009.88  5060.4 1011.14
  5080.4 1010.46  5120.4 1011.12  5470.1 1010.74  5540.6 1009.39  5572.1 1009.42
  5592.9 1011.48  5624.6 1009.87  5635.5 1010.74  5656.2 1010.22  5667.5 1011.19
  5699.5 1011.34  5758.3  1017.2  5782.3 1018.35  5811.8 1021.26  5866.3 1024.62
  5923.7 1026.18  5955.7 1028.95  6026.7 1032.97  6083.8 1038.06  6223.5  1044.4
#Mann= 6 ,-1 , 0
  3979.7     .05       0  4889.7      .1       0  4997.3     .07       0
  5003.3      .1       0  5811.8     .05       0  6026.7      .1       0
Bank Sta=4997.3,5003.3
XS Rating Curve= 0 ,0
Exp/Cntr=0.3,0.1

Type RM Length L Ch R = 1 ,2538    ,839,839,839
BEGIN DESCRIPTION:
UNT 1061 IN LATR 4.0
END DESCRIPTION:
XS GIS Cut Line= 4
      2945516.87     10095849.85      2944883.21     10095164.11
      2944388.42     10094973.13      2943238.22     10095177.13
#Sta/Elev= 30
  3729.4 1040.04  3831.9 1035.06  4029.8 1027.35  4152.9 1024.25    4200 1022.88
  4277.6 1021.69    4391 1018.16  4751.5 1005.25  4914.7  999.92  4929.4 1000.11
  4959.3  997.87  4978.6  998.04  4997.5  997.01  5000.2  996.51  5003.5  997.01
  5021.9  999.07  5098.8  999.44    5234  998.51  5345.7 1001.95  5477.8 1000.85
  5589.5 1002.75  5701.2 1003.71  5731.7  1003.2  5833.2 1006.66    5857 1008.69
  5894.2 1009.58  6094.5 1018.88  6219.2 1024.63  6260.6 1027.64  6361.6  1029.3
#Mann= 8 ,-1 , 0
  3729.4     .05       0  4152.9     .16       0    4200     .05       0
  4751.5      .1       0  4997.5     .07       0  5003.5      .1       0
  5098.8     .05       0  6094.5      .1       0
Bank Sta=4997.5,5003.5
XS Rating Curve= 0 ,0
Exp/Cntr=0.3,0.1

Type RM Length L Ch R = 1 ,1699    ,600,600,600
BEGIN DESCRIPTION:
UNT 1061 IN LATR 3.0
END DESCRIPTION:
XS GIS Cut Line= 3
      2945642.78     10094630.26      2944904.91     10094289.54
      2944234.31     10094734.44
#Sta/Elev= 30
  4268.2 1003.73  4389.9 1003.08  4418.3 1001.67  4578.9  998.22  4614.4  996.07
    4745  997.04  4773.4  994.62  4878.8   992.8  4888.2  992.63    4945   991.4
  4999.7  988.87  5031.3  991.95  5080.9  991.28  5138.2  992.43  5147.3  992.83
  5219.4  994.23  5354.7   994.7  5448.7  997.08  5484.7  995.76  5514.1  997.27
  5529.2  995.38  5550.2  996.42  5592.7  996.16  5622.4  997.66  5658.5  996.99
  5715.6  999.22  5724.7   998.3  5787.8  998.88  5808.9  997.65  5885.7  999.12
#Mann= 4 ,-1 , 0
  4268.2      .1       0  4888.2     .05       0  5138.2      .1       0
  5885.7     .05       0
Bank Sta=4878.8,5147.3
XS Rating Curve= 0 ,0
Exp/Cntr=0.3,0.1

Type RM Length L Ch R = 1 ,1099    ,335,335,335
BEGIN DESCRIPTION:
UNT 1061 IN LATR 2.0
END DESCRIPTION:
XS GIS Cut Line= 4
      2946230.84     10094393.69      2945417.06     10093859.85
      2945236.94     10093842.49      2944737.79     10094263.51
#Sta/Elev= 30
    3933   997.4  4107.7  993.14  4143.9   992.7  4345.8  992.54    4403  991.37
  4448.3  991.23  4490.5  989.47  4505.6  990.09  4569.7  989.52    4599  988.66
  4701.3  987.97  4722.6  988.82  4800.9  986.88  4837.1  986.52  4844.8  987.22
  4873.2  986.24  4924.9  986.17    4935   984.7  4965.1  984.32  4975.2  983.27
  5002.3  982.76    5005  982.26  5035.4   985.9  5055.5  987.05  5143.7  987.55
  5236.1  989.53  5342.7  989.39  5477.7  990.66  5484.4  991.18  5740.2  992.71
#Mann= 3 , 0 , 0
    3933      .1       0  4924.9     .05       0  5035.4      .1       0
Bank Sta=4924.9,5035.4
XS Rating Curve= 0 ,0
Exp/Cntr=0.3,0.1

Type RM Length L Ch R = 1 ,764     ,391,391,391
BEGIN DESCRIPTION:
Mapping XS 4280b67b
END DESCRIPTION:
XS GIS Cut Line= 3
      2946114.64     10093996.87      2945463.65     10093561.97
      2945173.74     10093794.44
#Sta/Elev= 30
  4270.8  986.79  4314.3  986.91  4480.1  985.43  4516.1  984.84  4522.1  984.13
  4537.1  984.59  4579.2  983.93  4645.3  984.37  4747.2  983.93  4840.5  985.15
  4861.5  985.02  4903.6  983.29  4912.6  984.27  4918.6  983.28  4927.6  984.02
  4984.6  981.76  4990.4  980.92  4999.7  981.65  5026.7  981.77  5053.7  982.96
  5059.2  983.77  5065.6  983.32    5080  984.56  5086.4  984.05  5094.4  984.87
  5100.8  984.49  5108.8   985.1  5129.6  984.56    5144  985.42  5425.3  987.88
#Mann= 4 ,-1 , 0
  4270.8     .05       0  4927.6    .035       0  5059.2     .05       0
  5425.3      .1       0
Bank Sta=4927.6,5059.2
XS Rating Curve= 0 ,0
Exp/Cntr=0.3,0.1

Type RM Length L Ch R = 1 ,373     ,280,280,280
BEGIN DESCRIPTION:
Mapping XS 5e5c02e7
END DESCRIPTION:
XS GIS Cut Line= 4
      2946228.23     10093803.36      2945690.01     10093271.35
       2945544.2     10093302.37      2945235.78     10093699.13
#Sta/Elev= 30
  4177.8  985.57  4184.4  986.08  4205.6  984.65  4262.2  983.76  4318.8  983.72
  4417.8  981.22    4446  982.09  4474.3  980.98  4502.6  981.58    4538  980.71
  4580.4  981.67  4728.9  980.91  4750.2  981.61    4842  979.86  4946.4  979.91
  4977.1  978.41  4997.3  975.55  5048.6  976.68  5058.8   978.1  5070.2  980.32
  5096.4   981.5  5102.8  980.84  5152.5  981.27  5231.3  982.88    5281  982.89
    5310  984.11  5330.8  983.35  5380.6   983.7  5494.6   986.2  5586.2  986.94
#Mann= 4 ,-1 , 0
  4177.8     .05       0  4977.1      .1       0  4977.1    .035       0
  5058.8     .05       0
Bank Sta=4977.1,5058.8
XS Rating Curve= 0 ,0
Exp/Cntr=0.3,0.1

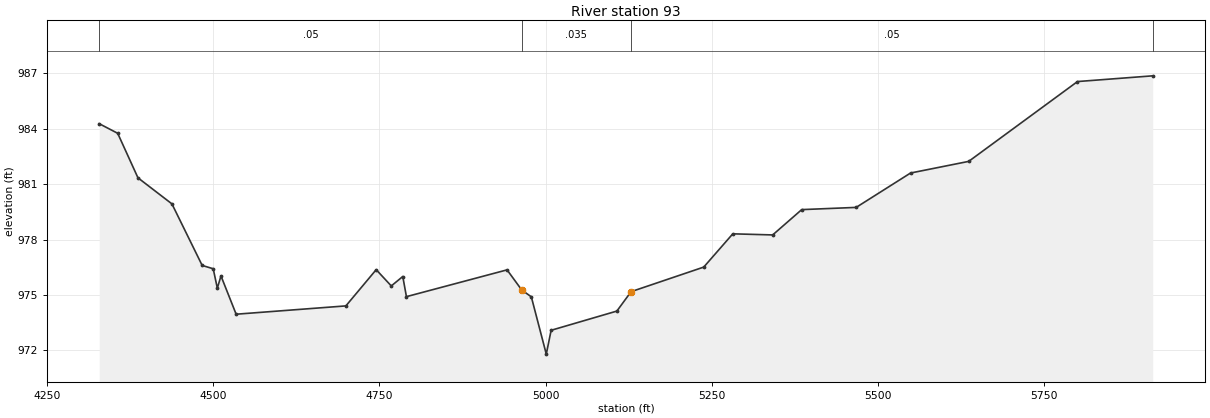
Type RM Length L Ch R = 1 ,93      ,0,0,0
BEGIN DESCRIPTION:
UNT 1061 IN LATR 1.0
END DESCRIPTION:
XS GIS Cut Line= 4
      2946313.57     10093314.78      2945671.39      10093012.3
      2945548.85     10093086.76      2945200.72     10093730.41
#Sta/Elev= 30
  4328.4  984.27  4356.2  983.75  4386.7  981.34  4437.8  979.93  4483.3   976.6
  4499.9  976.42  4506.1  975.37  4511.6  976.03  4534.4  973.96  4699.5  974.41
  4745.1  976.37  4767.8  975.49  4785.1     976  4790.6  974.91    4942  976.36
  4964.1  975.27  4978.5   974.9    5001   971.8  5008.3  973.09  5107.2  974.13
  5128.6  975.18  5237.9  976.51  5281.6  978.31  5341.6  978.25  5385.3  979.62
  5467.2  979.74    5549   981.6  5636.5  982.23  5800.2  986.55  5913.4  986.86
#Mann= 4 ,-1 , 0
  4328.4     .05       0  4964.1    .035       0  5128.6     .05       0
  5913.4      .1       0
Bank Sta=4964.1,5128.6
XS Rating Curve= 0 ,0
Exp/Cntr=0.3,0.1

Chan Stop Cuts=-1
Use User Specified Reach Order=0
Composite Channel Slope=5