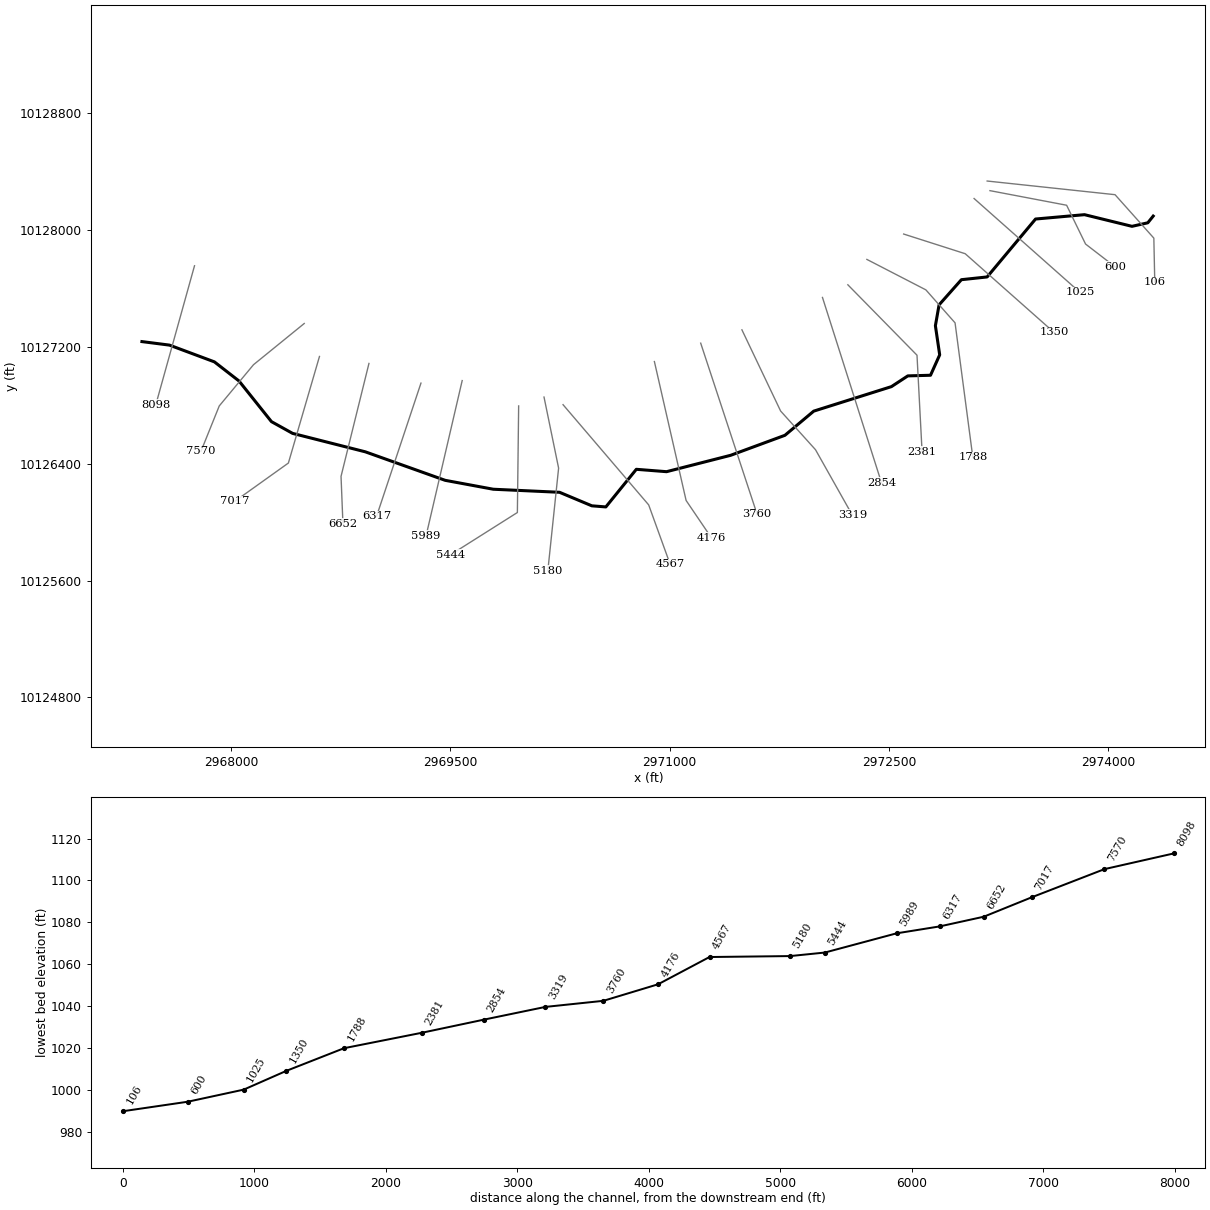
--- UNT 0063 IN LATR.prj (project) ---

Proj Title=UNT 1063 IN LATR Base Level Engineering
Current Plan=p01
Default Exp/Contr=0.3,0.1
English Units
Geom File=g01
Flow File=f01
Plan File=p01
BEGIN DESCRIPTION:
UNT 1063 IN LATR
END DESCRIPTION:

--- UNT 0063 IN LATR.p01 (plan) ---

Plan Title=Multiple Run
Short Identifier=Multiple
Geom File=g01
Flow File=f01
Subcritical Flow
K Sum by GR= 0
Std Step Tol= 0.01
Critical Tol= 0.01
Num of Std Step Trials= 20
Max Error Tol= 0.3
Flow Tol Ratio= 0.001
Split Flow NTrial= 30
Split Flow Tol= 0.02
Split Flow Ratio= 0.02
Log Output Level= 0
Friction Slope Method= 1
Unsteady Friction Slope Method= 2
Unsteady Bridges Friction Slope Method= 1
Parabolic Critical Depth
Global Vel Dist=  1 , 1 , 1
Global Log Level= 0
CheckData=True
Encroach Param= -1, 0, 0, 0
BEGIN DESCRIPTION:
Multiple Run
END DESCRIPTION:

--- UNT 0063 IN LATR.f01 (steady flow) ---

Flow Title=Multiple
Program Version=4.10
Number of Profiles= 7
Profile Names=10-year,25-year,50-year,1pct_min,100-year,1pct_plu,500-year
River Rch & RM=UNT 1063 IN LATR,Reach-1         ,8098
     989    1457    1871    1761    2381    3220    3869
River Rch & RM=UNT 1063 IN LATR,Reach-1         ,7570
    1614    2429    3162    3010    4071    5505    6774
Boundary for River Rch & Prof#=UNT 1063 IN LATR,Reach-1         , 1
Up Type= 0
Dn Type= 3
Dn Slope=0.009
Boundary for River Rch & Prof#=UNT 1063 IN LATR,Reach-1         , 2
Up Type= 0
Dn Type= 3
Dn Slope=0.009
Boundary for River Rch & Prof#=UNT 1063 IN LATR,Reach-1         , 3
Up Type= 0
Dn Type= 3
Dn Slope=0.009
Boundary for River Rch & Prof#=UNT 1063 IN LATR,Reach-1         , 4
Up Type= 0
Dn Type= 3
Dn Slope=0.009
Boundary for River Rch & Prof#=UNT 1063 IN LATR,Reach-1         , 5
Up Type= 0
Dn Type= 3
Dn Slope=0.009
Boundary for River Rch & Prof#=UNT 1063 IN LATR,Reach-1         , 6
Up Type= 0
Dn Type= 3
Dn Slope=0.009
Boundary for River Rch & Prof#=UNT 1063 IN LATR,Reach-1         , 7
Up Type= 0
Dn Type= 3
Dn Slope=0.009
DSS Import GetInterval= 0
DSS Import GetPeak= 0
DSS Import FillOption= 0

--- UNT 0063 IN LATR.g01 (geometry) ---

Geom Title=Existing Conditions
Program Version=4.10

River Reach=UNT 1063 IN LATR,Reach-1
Reach XY= 30
      2967388.88     10127234.96      2967577.28     10127210.87
      2967884.77     10127096.19      2968053.29     10126965.26
      2968275.17     10126687.24      2968419.78      10126606.9
      2968917.24     10126480.77      2969463.73     10126285.71
      2969793.16     10126224.71      2970246.28     10126203.85
      2970467.43     10126111.22       2970563.2     10126103.69
      2970771.65     10126361.07      2970978.57     10126344.83
      2971417.15      10126456.9      2971788.47     10126593.73
      2971985.66     10126759.15      2972517.23     10126926.82
      2972629.49     10127000.32      2972784.75     10127004.62
       2972847.5     10127144.16       2972818.1     10127343.64
      2972843.34     10127486.43      2972995.97     10127658.51
      2973172.16     10127677.34      2973503.48     10128073.63
      2973838.34     10128103.43      2974163.35     10128023.64
      2974271.54     10128047.86      2974308.47     10128093.73

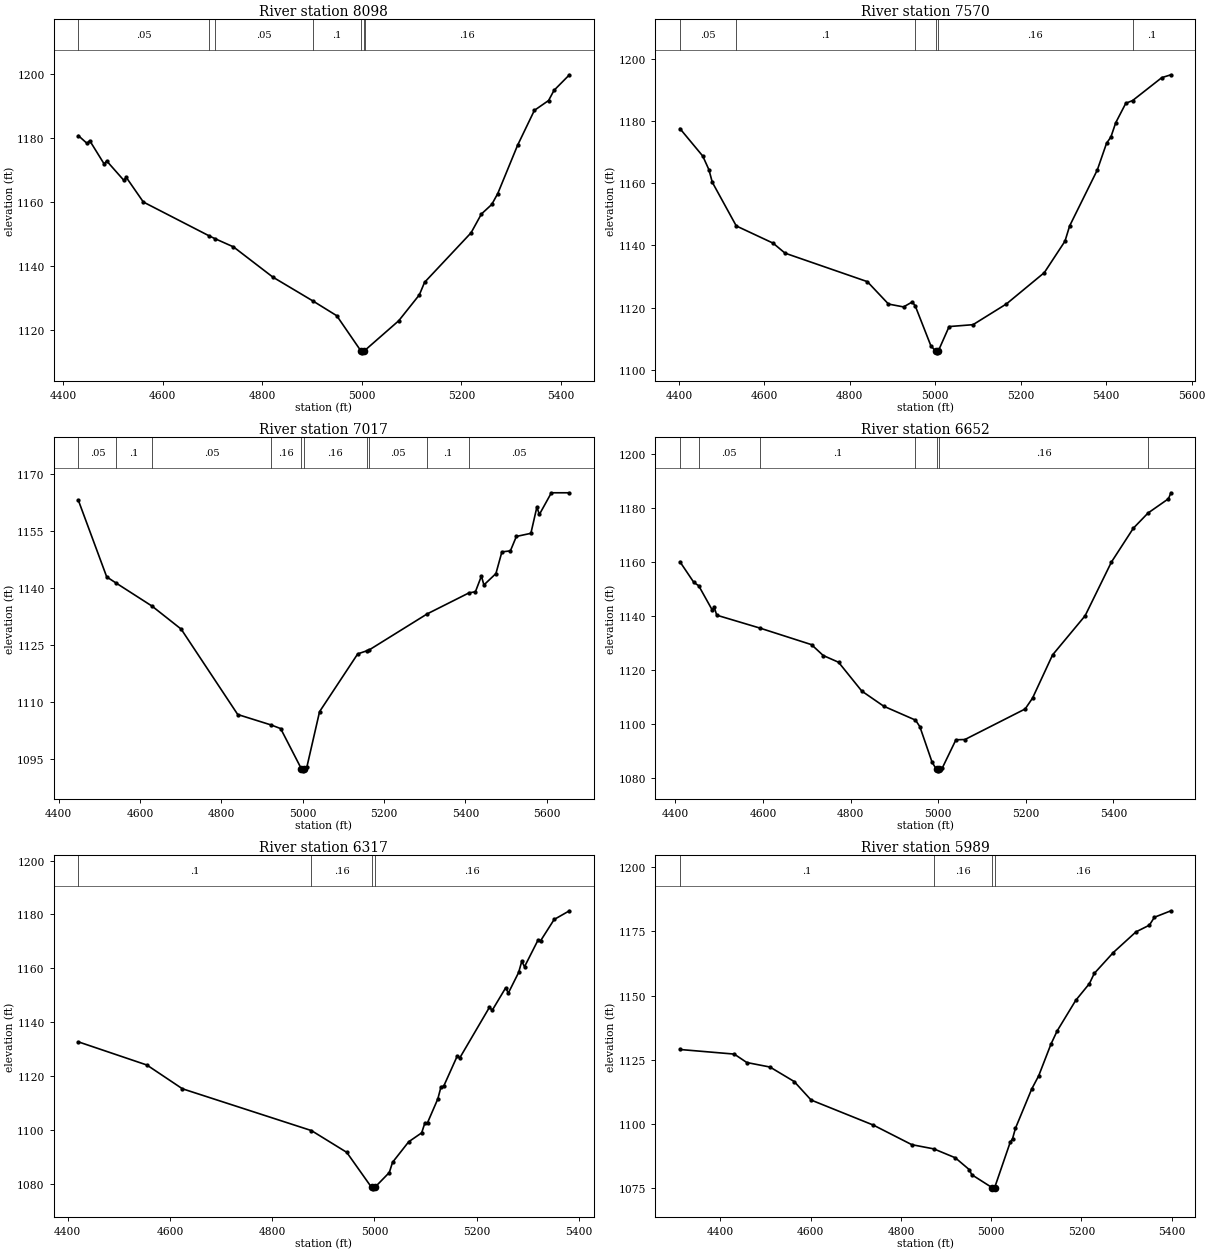
Type RM Length L Ch R = 1 ,8098    ,528,528,528
BEGIN DESCRIPTION:
UNT 1063 IN LATR 18.0
END DESCRIPTION:
XS GIS Cut Line= 2
      2967748.64     10127753.84      2967483.88     10126803.32
#Sta/Elev= 30
  4430.3 1180.62  4447.8 1178.19    4453 1179.08    4482  1171.8  4487.2 1172.73
  4521.4 1166.73  4526.6 1167.59  4560.8 1159.93  4693.6 1149.33  4705.1 1148.48
  4741.8 1145.95    4821 1136.52    4902 1129.03  4949.4 1124.48  4998.4  1113.4
  5001.1  1112.9  5004.4  1113.4  5005.2 1113.57    5074 1122.91  5115.4 1130.98
  5125.9 1134.89  5219.3 1150.33  5240.1 1156.19  5260.9 1159.17    5273 1162.58
  5312.8 1177.62  5346.6 1188.52  5375.1 1191.58    5386 1194.75    5417 1199.61
#Mann= 7 ,-1 , 0
  4430.3     .05       0  4693.6      .1       0  4705.1     .05       0
    4902      .1       0  4998.4     .07       0  5004.4      .1       0
  5005.2     .16       0
Bank Sta=4998.4,5004.4
XS Rating Curve= 0 ,0
Exp/Cntr=0.3,0.1

Type RM Length L Ch R = 1 ,7570    ,553,553,553
BEGIN DESCRIPTION:
UNT 1063 IN LATR 17.0
END DESCRIPTION:
XS GIS Cut Line= 4
      2968499.47     10127358.84      2968152.28     10127076.75
      2967917.91     10126794.63      2967792.75     10126483.91
#Sta/Elev= 30
  4402.4 1177.64  4455.9 1168.78  4470.3 1164.39  4478.2 1160.35  4534.3 1146.28
  4620.4 1140.74  4648.5 1137.51    4841 1128.34  4890.5 1121.12  4925.7  1120.2
  4946.5 1121.82  4953.5  1120.4  4989.5 1107.76  5000.8 1105.91  5003.5 1105.41
  5006.8 1105.91  5032.4 1113.87  5088.4 1114.48  5166.5 1121.16  5255.2 1131.24
  5303.5 1141.36  5314.5  1146.3  5379.2  1164.3  5400.8  1172.9    5411 1174.92
  5422.3 1179.52  5445.9 1185.79  5461.7 1186.65  5530.1 1194.04  5551.5 1194.96
#Mann= 6 ,-1 , 0
  4402.4     .05       0  4534.3      .1       0  4953.5     .16       0
  5000.8     .07       0  5006.8     .16       0  5461.7      .1       0
Bank Sta=5000.8,5006.8
XS Rating Curve= 0 ,0
Exp/Cntr=0.3,0.1

Type RM Length L Ch R = 1 ,7017    ,365,365,365
BEGIN DESCRIPTION:
UNT 1063 IN LATR 16.0
END DESCRIPTION:
XS GIS Cut Line= 3
      2968603.66     10127133.15        2968391.     10126404.01
      2968026.38     10126143.57
#Sta/Elev= 30
  4448.3 1163.08  4517.9 1142.98  4541.7 1141.31  4629.2 1135.31    4701 1129.25
  4840.1  1106.8  4922.8 1104.03  4945.7  1103.1  4996.8 1092.49  4999.5 1091.99
  5002.8 1092.49  5010.2    1093  5041.4 1107.55  5135.2 1122.73  5157.1 1123.53
  5162.3  1123.7  5306.1 1133.25    5409 1138.78  5424.7 1139.07  5439.4 1143.19
  5445.6 1140.86  5475.1 1143.85  5489.8 1149.55  5510.7 1149.82  5525.4 1153.61
  5561.1 1154.43  5575.8 1161.31    5582 1159.39  5611.5 1165.09  5655.9 1165.09
#Mann= 10 ,-1 , 0
  4448.3     .05       0  4541.7      .1       0  4629.2     .05       0
  4922.8     .16       0  4996.8     .07       0  5002.8     .16       0
  5157.1      .1       0  5162.3     .05       0  5306.1      .1       0
    5409     .05       0
Bank Sta=4996.8,5002.8
XS Rating Curve= 0 ,0
Exp/Cntr=0.3,0.1

Type RM Length L Ch R = 1 ,6652    ,335,335,335
BEGIN DESCRIPTION:
UNT 1063 IN LATR 15.0
END DESCRIPTION:
XS GIS Cut Line= 3
       2968942.2     10127085.39      2968751.24     10126312.86
      2968764.23       10125988.
#Sta/Elev= 30
  4410.4 1160.04  4442.3 1152.37  4453.3 1151.16  4483.8  1142.3  4488.9 1143.12
  4494.5 1140.27  4592.5 1135.53  4710.8 1129.38  4737.6 1125.36  4772.6 1122.87
  4825.6 1112.22  4875.7 1106.62  4948.2 1101.48  4958.1 1099.08  4986.2 1085.86
  4996.3 1083.23    4999 1082.73  5002.3 1083.23  5009.6 1083.86  5040.5 1094.21
  5061.1 1094.31  5198.5  1105.6  5215.3 1109.59  5261.1 1125.58  5335.4 1140.06
  5395.5 1159.92  5445.5 1172.42    5479 1178.03  5525.6  1183.3  5531.3 1185.52
#Mann= 7 ,-1 , 0
  4410.4      .1       0  4453.3     .05       0  4592.5      .1       0
  4948.2     .16       0  4996.3     .07       0  5002.3     .16       0
    5479      .1       0
Bank Sta=4996.3,5002.3
XS Rating Curve= 0 ,0
Exp/Cntr=0.3,0.1

Type RM Length L Ch R = 1 ,6317    ,328,328,328
BEGIN DESCRIPTION:
UNT 1063 IN LATR 14.0
END DESCRIPTION:
XS GIS Cut Line= 2
      2969298.11     10126950.86      2968994.31     10126039.46
#Sta/Elev= 30
  4420.8 1132.69  4554.8 1124.09  4624.3 1115.27  4876.7 1099.75  4945.8 1091.67
  4994.5 1078.62  4997.3 1078.12  5000.5 1078.62  5029.1 1084.18  5035.4 1087.96
    5067 1095.59  5092.4 1098.91  5098.6 1102.54  5103.9  1102.7    5124 1111.51
  5130.2 1115.99  5135.5 1116.23  5161.9 1127.39  5167.1 1126.78  5225.1 1145.56
  5230.4 1144.39  5256.7 1152.74    5262 1150.83  5282.1 1158.45  5288.3 1162.63
  5293.6 1160.57    5320 1170.46  5325.2 1170.26  5351.6 1178.13  5381.5 1181.36
#Mann= 4 ,-1 , 0
  4420.8      .1       0  4876.7     .16       0  4994.5     .07       0
  5000.5     .16       0
Bank Sta=4994.5,5000.5
XS Rating Curve= 0 ,0
Exp/Cntr=0.3,0.1

Type RM Length L Ch R = 1 ,5989    ,545,545,545
BEGIN DESCRIPTION:
UNT 1063 IN LATR 13.0
END DESCRIPTION:
XS GIS Cut Line= 2
      2969580.22     10126968.21      2969333.59     10125908.12
#Sta/Elev= 30
  4310.2 1129.02  4430.6 1127.23  4458.5 1123.95  4509.9 1122.19  4563.5 1116.56
    4601 1109.36    4739 1099.61  4824.2    1092  4873.2 1090.35  4920.6  1086.9
  4951.4 1082.32  4957.2 1080.31  5001.9 1075.32  5004.7 1074.82  5007.9 1075.32
  5042.4 1092.97  5047.5 1094.31    5054 1098.39  5090.1 1113.68  5105.4 1118.76
  5132.7 1131.12  5146.4 1136.24  5187.5 1148.11  5217.9 1154.64  5228.6 1158.59
  5270.8 1166.72    5321 1174.75  5350.8 1177.37    5362 1180.45  5398.6 1182.97
#Mann= 4 ,-1 , 0
  4310.2      .1       0  4873.2     .16       0  5001.9     .07       0
  5007.9     .16       0
Bank Sta=5001.9,5007.9
XS Rating Curve= 0 ,0
Exp/Cntr=0.3,0.1

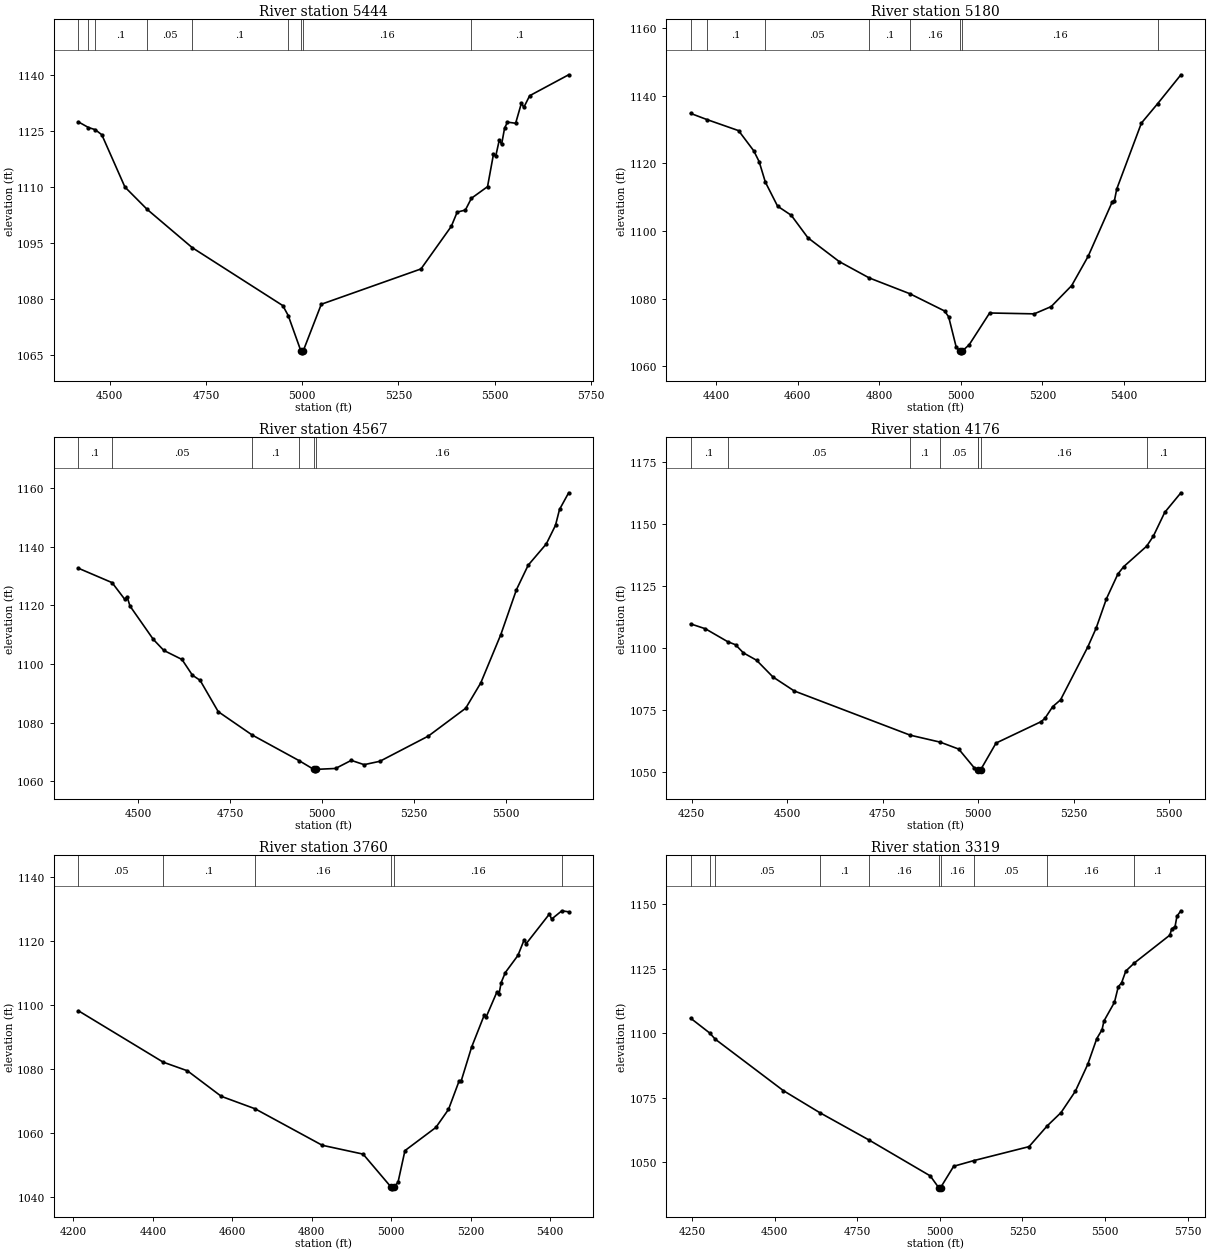
Type RM Length L Ch R = 1 ,5444    ,264,264,264
BEGIN DESCRIPTION:
UNT 1063 IN LATR 12.0
END DESCRIPTION:
XS GIS Cut Line= 3
      2969966.52     10126794.65      2969957.84     10126065.46
      2969497.77     10125774.67
#Sta/Elev= 30
  4418.5 1127.42  4444.7 1125.91  4462.2 1125.34  4479.4 1123.97  4539.4    1110
  4597.2 1104.02  4714.4 1093.78  4949.5  1078.3  4963.6 1075.64  4996.5 1066.17
  4999.2 1065.67  5002.5 1066.17  5049.5 1078.66  5308.4  1088.1  5387.2 1099.49
  5402.5  1103.3  5423.7 1103.84  5439.4 1106.99  5481.3  1110.1  5496.6  1118.7
  5502.5 1118.22  5511.9 1122.59  5517.8 1121.39  5525.6 1125.76  5533.1 1127.35
  5554.3 1127.05  5569.5 1132.51  5575.4 1131.27  5590.7 1134.41    5692 1140.01
#Mann= 9 ,-1 , 0
  4418.5      .1       0  4444.7     .05       0  4462.2      .1       0
  4597.2     .05       0  4714.4      .1       0  4963.6     .16       0
  4996.5     .07       0  5002.5     .16       0  5439.4      .1       0
Bank Sta=4996.5,5002.5
XS Rating Curve= 0 ,0
Exp/Cntr=0.3,0.1

Type RM Length L Ch R = 1 ,5180    ,613,613,613
BEGIN DESCRIPTION:
UNT 1063 IN LATR 11.0
END DESCRIPTION:
XS GIS Cut Line= 3
      2970140.12     10126855.43      2970239.96     10126369.28
       2970166.3     10125667.42
#Sta/Elev= 30
  4337.4 1134.76  4377.3 1132.94    4455 1129.66  4492.3 1123.68  4505.4  1120.5
  4520.6 1114.46  4550.6 1107.34  4584.1 1104.65    4625 1097.99  4701.8 1090.96
  4775.3 1086.13  4874.7 1081.47  4959.9 1076.37    4970 1074.64  4988.4 1065.75
  4997.1 1064.49  4999.9 1063.99  5003.1 1064.49  5020.3 1066.37  5070.5 1075.77
  5179.7 1075.51  5221.4 1077.66  5271.6 1083.86  5311.8 1092.47  5371.1 1108.61
  5376.1  1108.8  5382.2 1112.44  5442.6  1131.9  5482.3 1137.62  5539.4 1146.17
#Mann= 8 ,-1 , 0
  4337.4     .05       0  4377.3      .1       0  4520.6     .05       0
  4775.3      .1       0  4874.7     .16       0  4997.1     .07       0
  5003.1     .16       0  5482.3      .1       0
Bank Sta=4997.1,5003.1
XS Rating Curve= 0 ,0
Exp/Cntr=0.3,0.1

Type RM Length L Ch R = 1 ,4567    ,391,391,391
BEGIN DESCRIPTION:
UNT 1063 IN LATR 10.0
END DESCRIPTION:
XS GIS Cut Line= 3
      2970270.33     10126803.32      2970856.27     10126117.55
      2971003.65     10125710.09
#Sta/Elev= 30
  4336.3  1132.7  4428.1 1127.78  4462.5 1122.11  4469.1 1122.93  4476.8 1119.81
  4540.4 1108.41    4569 1104.64  4618.4 1101.56  4646.9 1096.19  4667.8 1094.44
  4717.2 1083.74  4809.3  1075.8  4937.2 1067.04  4977.3 1064.04    4980 1063.54
  4983.3 1064.04  5036.7 1064.35  5079.5 1067.11  5114.6 1065.65  5157.4  1066.8
  5289.5 1075.41  5391.2 1084.91  5432.2 1093.54  5486.9 1110.06  5529.5  1125.4
  5561.4 1133.74  5610.7 1140.99  5635.8 1147.36  5646.7 1152.75  5671.6 1158.45
#Mann= 6 ,-1 , 0
  4336.3      .1       0  4428.1     .05       0  4809.3      .1       0
  4937.2     .16       0  4977.3     .07       0  4983.3     .16       0
Bank Sta=4977.3,4983.3
XS Rating Curve= 0 ,0
Exp/Cntr=0.3,0.1

Type RM Length L Ch R = 1 ,4176    ,416,416,416
BEGIN DESCRIPTION:
UNT 1063 IN LATR 9.0
END DESCRIPTION:
XS GIS Cut Line= 3
      2970895.34     10127098.43      2971112.35     10126147.93
      2971285.94     10125891.88
#Sta/Elev= 30
    4247  1109.8  4285.6 1107.83    4344 1102.63  4364.6 1101.39  4385.2 1098.12
  4419.7 1095.14  4462.6  1088.4  4518.5 1082.75  4822.2 1064.93    4901 1062.11
  4949.3 1059.32  4990.3  1051.7  5000.9 1051.05    5001 1051.05  5003.8 1050.55
    5007 1051.05    5047 1061.74  5164.7 1070.35    5175 1071.68  5195.5 1076.44
    5216 1079.16  5287.4  1100.5  5309.3 1108.09  5336.3 1119.95  5366.2 1129.89
  5381.2 1132.83  5441.6 1141.12  5459.1 1145.16    5489 1154.76  5531.3 1162.65
#Mann= 8 ,-1 , 0
    4247      .1       0    4344     .05       0  4822.2      .1       0
    4901     .05       0  5000.9     .16       0    5001    .035       0
    5007     .16       0  5441.6      .1       0
Bank Sta=5001,5007
XS Rating Curve= 0 ,0
Exp/Cntr=0.3,0.1

Type RM Length L Ch R = 1 ,3760    ,441,441,441
BEGIN DESCRIPTION:
UNT 1063 IN LATR 8.0
END DESCRIPTION:
XS GIS Cut Line= 2
      2971212.18     10127224.33      2971598.46     10126052.45
#Sta/Elev= 30
  4212.6 1098.23  4426.1 1082.19    4487  1079.5  4572.3 1071.53  4657.1 1067.66
  4826.4 1056.26  4929.2  1053.5  4999.9 1043.17  5002.7 1042.67  5005.9 1043.17
    5017 1044.68  5034.5 1054.59  5112.3 1061.82  5144.1 1067.44  5170.6 1076.25
  5175.8 1076.23  5202.3 1086.89  5234.1 1096.88  5239.4 1096.43  5265.9 1104.06
  5271.1 1103.33  5276.7 1107.04  5287.2 1110.16  5318.8 1115.48  5334.7  1120.4
  5339.9 1119.19  5398.2 1128.43  5403.5 1126.81  5429.4 1129.42  5446.5 1129.08
#Mann= 6 ,-1 , 0
  4212.6     .05       0  4426.1      .1       0  4657.1     .16       0
  4999.9     .07       0  5005.9     .16       0  5429.4      .1       0
Bank Sta=4999.9,5005.9
XS Rating Curve= 0 ,0
Exp/Cntr=0.3,0.1

Type RM Length L Ch R = 1 ,3319    ,465,465,465
BEGIN DESCRIPTION:
UNT 1063 IN LATR 7.0
END DESCRIPTION:
XS GIS Cut Line= 4
       2971494.3     10127315.45      2971759.05     10126759.91
      2971997.77     10126495.15      2972249.34      10126048.4
#Sta/Elev= 30
  4245.4 1105.92  4303.2 1100.17  4319.9 1097.79  4526.1 1077.85  4635.7 1069.36
  4786.3 1058.65    4971 1044.79  4996.4 1040.27  4999.2 1039.77  5002.4 1040.27
    5042 1048.52  5102.7 1050.71  5270.1 1056.13  5325.4 1064.21    5367 1069.33
  5410.3 1077.59  5447.9 1088.02  5475.3 1098.02  5491.2 1101.45    5497 1104.84
  5528.8 1112.08  5540.3 1118.08  5550.5 1119.67  5563.2  1124.2  5588.6 1127.28
  5696.4 1138.11  5702.2 1140.55  5712.3 1141.45  5718.1 1145.48    5730 1147.56
#Mann= 10 ,-1 , 0
  4245.4     .05       0  4303.2      .1       0  4319.9     .05       0
  4635.7      .1       0  4786.3     .16       0  4996.4     .07       0
  5002.4     .16       0  5102.7     .05       0  5325.4     .16       0
  5588.6      .1       0
Bank Sta=4996.4,5002.4
XS Rating Curve= 0 ,0
Exp/Cntr=0.3,0.1

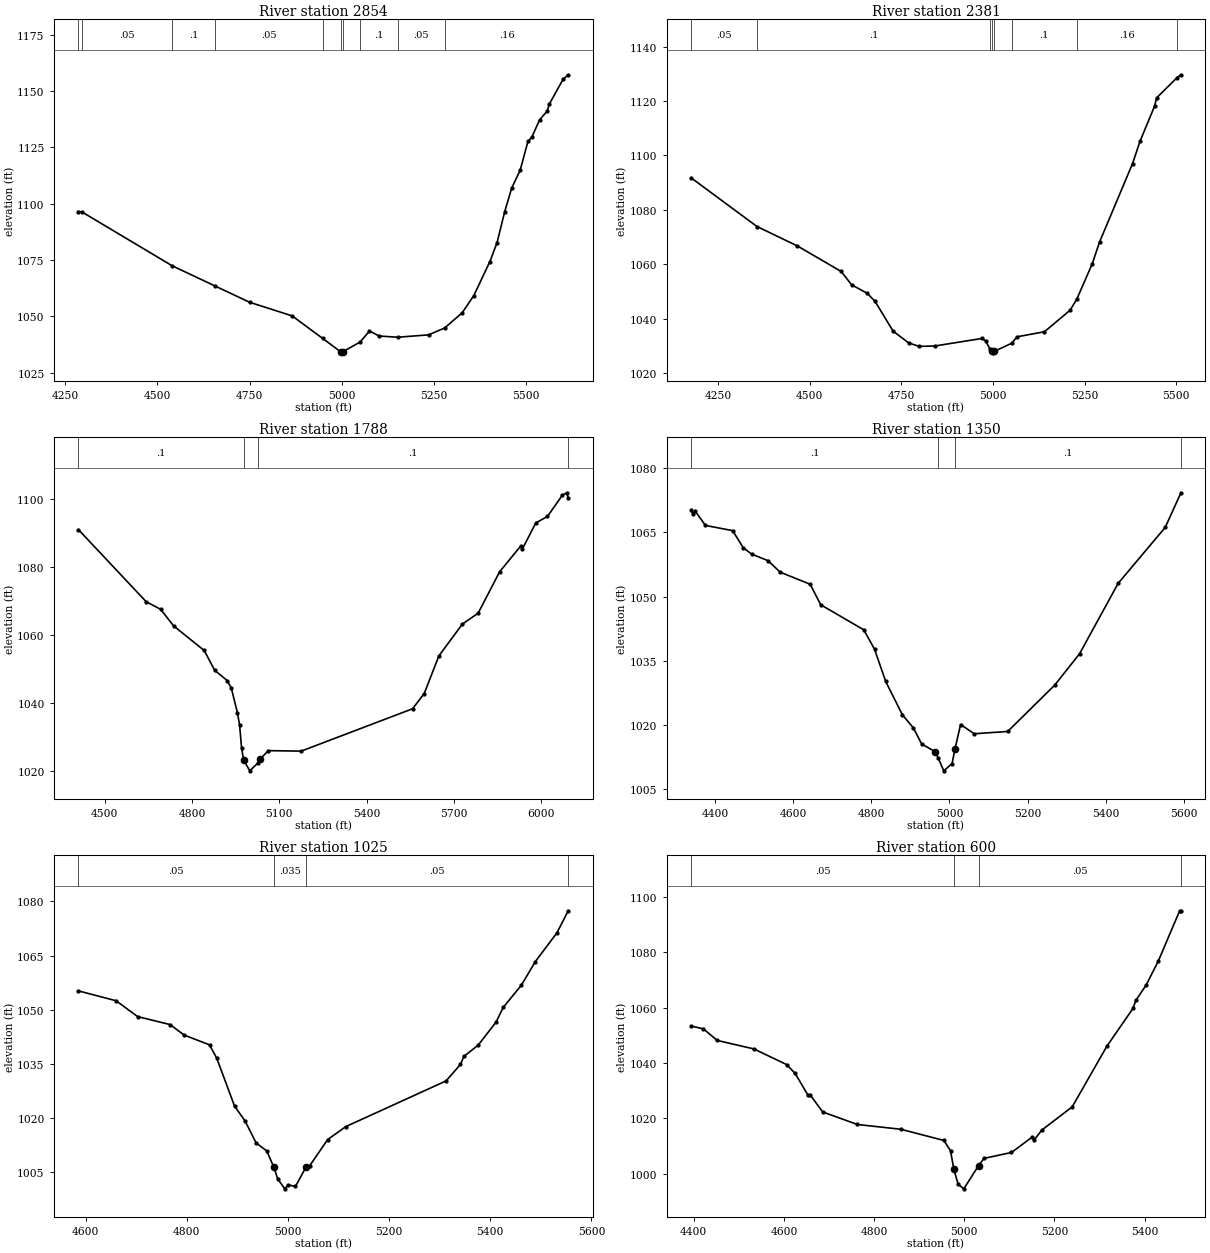
Type RM Length L Ch R = 1 ,2854    ,473,473,473
BEGIN DESCRIPTION:
UNT 1063 IN LATR 6.0
END DESCRIPTION:
XS GIS Cut Line= 2
       2972045.5     10127536.85      2972449.15     10126269.48
#Sta/Elev= 30
  4285.2 1096.45  4295.1 1096.29  4539.7 1072.42  4656.8 1063.38  4750.3 1056.19
  4865.7 1050.15  4948.3 1040.17  4997.2 1034.24  4999.9 1033.74  5003.2 1034.24
  5050.1 1038.52  5075.6 1043.43  5102.1 1041.21  5151.9 1040.67  5236.2 1041.72
  5279.9 1044.79  5327.5 1051.56    5359  1059.2  5402.5 1074.25  5421.9 1082.62
  5442.9  1096.5  5461.7 1106.88  5484.9 1114.87  5505.9 1127.64  5516.4 1129.47
  5537.4 1137.18  5558.4 1141.14  5563.6 1144.08  5601.1 1155.18  5615.3 1157.21
#Mann= 10 ,-1 , 0
  4285.2      .1       0  4295.1     .05       0  4539.7      .1       0
  4656.8     .05       0  4948.3     .16       0  4997.2     .07       0
  5003.2     .16       0  5050.1      .1       0  5151.9     .05       0
  5279.9     .16       0
Bank Sta=4997.2,5003.2
XS Rating Curve= 0 ,0
Exp/Cntr=0.3,0.1

Type RM Length L Ch R = 1 ,2381    ,593,593,593
BEGIN DESCRIPTION:
UNT 1063 IN LATR 5.0
END DESCRIPTION:
XS GIS Cut Line= 3
      2972219.15      10127623.6      2972692.21     10127141.85
      2972726.93     10126482.14
#Sta/Elev= 30
  4176.7 1091.79  4356.5 1073.88  4466.1 1066.78  4586.2 1057.36  4614.5 1052.48
  4656.9 1049.36  4678.2 1046.45  4727.7 1035.44  4770.1 1031.13  4798.4 1029.85
  4840.8 1029.97  4970.2 1032.76  4980.2 1031.81    4992 1028.81  4997.2 1027.97
    5000 1027.47  5003.2 1027.97    5051    1031  5065.6 1033.36  5140.4 1035.22
  5210.5 1043.15  5228.5 1047.17  5270.6 1060.15  5290.6 1068.18  5380.7 1097.02
  5400.8 1105.13  5440.8 1118.13  5446.2 1121.14  5502.2  1128.6  5512.5 1129.62
#Mann= 8 ,-1 , 0
  4176.7     .05       0  4356.5      .1       0    4992     .05       0
  4997.2    .035       0  5003.2     .05       0    5051      .1       0
  5228.5     .16       0  5502.2     .05       0
Bank Sta=4997.2,5003.2
XS Rating Curve= 0 ,0
Exp/Cntr=0.3,0.1

Type RM Length L Ch R = 1 ,1788    ,438,438,438
BEGIN DESCRIPTION:
UNT 1063 IN LATR 4.0
END DESCRIPTION:
XS GIS Cut Line= 4
      2972349.36     10127797.22      2972752.98      10127588.9
      2972952.63     10127363.21      2973074.16     10126443.03
#Sta/Elev= 30
  4409.2 1091.08  4642.3 1069.85  4692.2  1067.6  4736.6 1062.73  4841.7  1055.5
  4878.1 1049.63  4920.8 1046.67    4935 1044.41  4955.9 1037.19  4963.4 1033.58
  4970.1 1026.91  4977.1 1023.33  4998.3  1020.1    5027 1022.47  5033.7 1023.55
  5062.1 1026.04  5175.2  1025.9  5557.8 1038.36  5597.9 1042.84  5648.4 1053.92
  5729.1 1063.27  5783.3 1066.48  5856.8 1078.62  5930.3  1086.3  5935.3 1085.35
  5981.2 1093.01  6021.6 1094.94    6072 1101.11  6087.4 1101.89  6092.9 1100.38
#Mann= 4 ,-1 , 0
  4409.2      .1       0  4977.1     .05       0    5027      .1       0
  6092.9      .1       0
Bank Sta=4977.1,5033.7
XS Rating Curve= 0 ,0
Exp/Cntr=0.3,0.1

Type RM Length L Ch R = 1 ,1350    ,325,325,325
BEGIN DESCRIPTION:
UNT 1063 IN LATR 3.0
END DESCRIPTION:
XS GIS Cut Line= 3
      2972601.06     10127970.85      2973022.07      10127836.3
      2973629.33     10127298.44
#Sta/Elev= 30
  4339.1 1070.29  4343.8 1069.26  4349.1 1070.03    4376 1066.62  4445.6  1065.4
  4472.5 1061.43  4493.9 1059.93  4535.8  1058.4  4567.3  1055.7  4643.9 1052.88
  4670.8  1048.1  4781.1 1042.24  4808.6 1037.69  4837.1 1030.19  4879.7 1022.42
  4908.2  1019.3  4929.1 1015.59  4964.2 1013.77  4971.7 1012.25  4985.7 1009.32
  5006.9 1011.03  5014.4 1014.44  5028.6 1020.13  5063.7 1017.98  5149.1 1018.51
  5269.5 1029.33  5333.1 1036.67  5431.7 1053.09  5552.2 1066.17  5592.3 1074.24
#Mann= 4 ,-1 , 0
  4339.1      .1       0  4971.7     .05       0  5014.4      .1       0
  5592.3      .1       0
Bank Sta=4964.2,5014.4
XS Rating Curve= 0 ,0
Exp/Cntr=0.3,0.1

Type RM Length L Ch R = 1 ,1025    ,425,425,425
BEGIN DESCRIPTION:
UNT 1063 IN LATR 2.0
END DESCRIPTION:
XS GIS Cut Line= 2
      2973082.82     10128213.92      2973807.64     10127571.56
#Sta/Elev= 30
  4585.7 1055.22  4660.3 1052.48  4702.9 1048.09    4767 1045.88  4794.9 1042.97
  4845.1 1040.25  4859.4 1036.53  4894.5 1023.28  4915.4 1019.14  4937.1 1013.09
    4958 1010.88  4972.3 1006.35  4979.8 1003.13  4993.8 1000.36  5000.7 1001.47
  5014.9 1001.01  5035.8  1006.4  5043.4 1006.82  5078.5 1014.01  5114.4  1017.6
  5312.7 1030.27  5341.1 1034.82  5347.8 1037.04  5376.2 1040.19  5411.4 1046.54
  5425.6 1050.63  5461.5 1056.77  5489.1 1063.33  5531.8 1071.29  5554.2 1077.41
#Mann= 4 ,-1 , 0
  4585.7     .05       0  4972.3    .035       0  5035.8     .05       0
  5554.2      .1       0
Bank Sta=4972.3,5035.8
XS Rating Curve= 0 ,0
Exp/Cntr=0.3,0.1

Type RM Length L Ch R = 1 ,600     ,494,494,494
BEGIN DESCRIPTION:
Mapping XS d77dee24
END DESCRIPTION:
XS GIS Cut Line= 4
       2973191.4     10128267.78      2973716.01     10128167.96
      2973845.57     10127902.47      2974049.48     10127745.29
#Sta/Elev= 30
  4393.9 1053.35  4421.4 1052.32    4452 1048.15  4533.4 1045.08  4606.3 1039.41
    4625 1036.22  4653.4 1028.39  4658.5 1028.44  4686.1 1022.34  4762.9 1017.82
  4859.2  1016.1  4954.9 1012.06  4969.6 1008.35  4977.1 1001.59  4986.6  996.26
  4999.1   994.6  5031.7 1002.94  5043.9 1005.59  5104.8 1007.72  5149.9 1013.16
  5155.4 1012.29  5172.4 1015.83  5239.6 1024.18  5316.5 1046.06  5374.5 1059.71
  5380.8  1062.6  5403.5 1068.08  5430.7 1076.81    5478 1094.93  5480.8 1094.93
#Mann= 4 ,-1 , 0
  4393.9     .05       0  4977.1    .035       0  5031.7     .05       0
  5480.8      .1       0
Bank Sta=4977.1,5031.7
XS Rating Curve= 0 ,0
Exp/Cntr=0.3,0.1

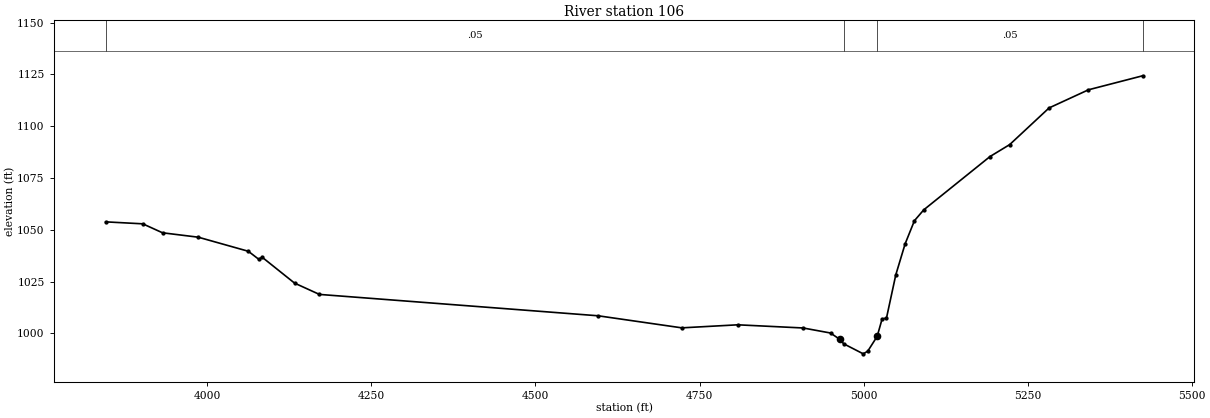
Type RM Length L Ch R = 1 ,106     ,0,0,0
BEGIN DESCRIPTION:
UNT 1063 IN LATR 1.0
END DESCRIPTION:
XS GIS Cut Line= 4
      2973172.33     10128333.62      2974047.34     10128240.17
      2974312.83     10127942.83       2974319.2      10127641.2
#Sta/Elev= 30
    3845 1053.81  3901.5 1052.86  3931.6 1048.53  3986.1  1046.4  4062.4  1039.6
  4078.4  1035.7  4083.4 1036.74  4132.8 1024.23  4170.7 1018.77  4595.4 1008.45
    4723 1002.62  4808.3 1004.09  4907.8 1002.56  4949.6 1000.13  4963.8  997.05
  4969.7  994.92  4999.5  990.07  5006.4  991.38  5020.7  998.49  5028.2 1006.88
  5034.9 1007.35  5049.1 1028.23  5063.3 1043.18  5077.5 1054.37  5091.7 1059.61
  5192.7 1085.36  5222.7 1091.13  5282.7 1108.83  5342.7 1117.59  5425.3 1124.36
#Mann= 4 ,-1 , 0
    3845     .05       0  4969.7    .035       0  5020.7     .05       0
  5425.3      .1       0
Bank Sta=4963.8,5020.7
XS Rating Curve= 0 ,0
Exp/Cntr=0.3,0.1

Chan Stop Cuts=-1
Use User Specified Reach Order=0
Composite Channel Slope=5