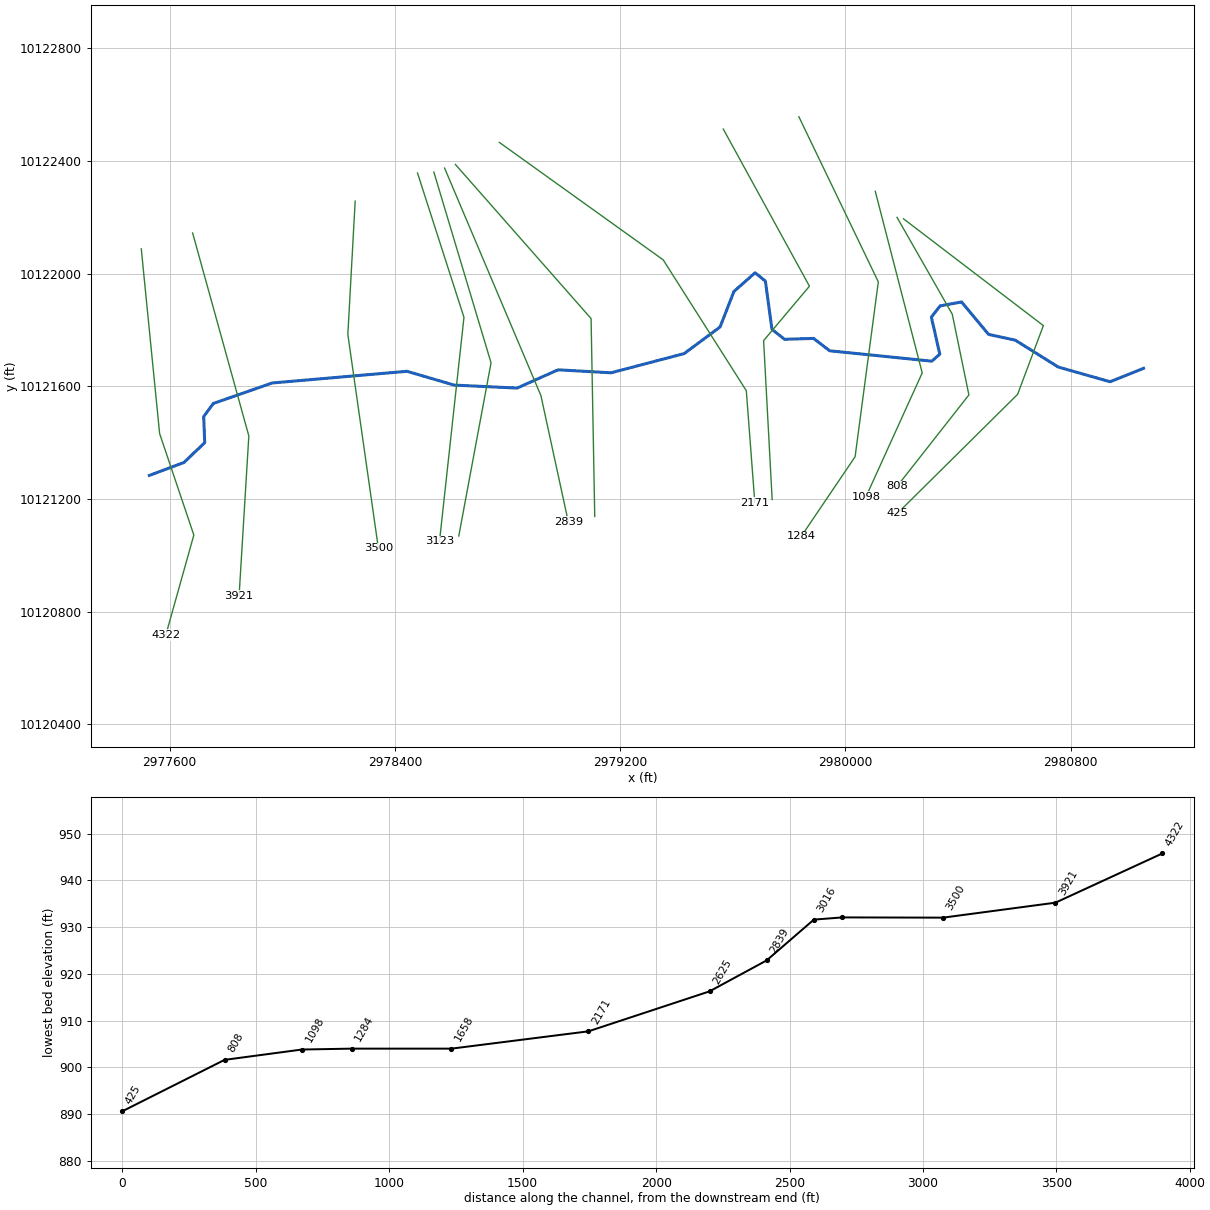
--- UNT 0064 IN LATR.prj (project) ---

Proj Title=UNT 1064 IN LATR Base Level Engineering
Current Plan=p01
Default Exp/Contr=0.3,0.1
English Units
Geom File=g01
Flow File=f01
Plan File=p01
BEGIN DESCRIPTION:
UNT 1064 IN LATR
END DESCRIPTION:

--- UNT 0064 IN LATR.p01 (plan) ---

Plan Title=Multiple Run
Short Identifier=Multiple
Geom File=g01
Flow File=f01
Subcritical Flow
K Sum by GR= 0
Std Step Tol= 0.01
Critical Tol= 0.01
Num of Std Step Trials= 20
Max Error Tol= 0.3
Flow Tol Ratio= 0.001
Split Flow NTrial= 30
Split Flow Tol= 0.02
Split Flow Ratio= 0.02
Log Output Level= 0
Friction Slope Method= 1
Unsteady Friction Slope Method= 2
Unsteady Bridges Friction Slope Method= 1
Parabolic Critical Depth
Global Vel Dist=  1 , 1 , 1
Global Log Level= 0
CheckData=True
Encroach Param= -1, 0, 0, 0
BEGIN DESCRIPTION:
Multiple Run
END DESCRIPTION:

--- UNT 0064 IN LATR.f01 (steady flow) ---

Flow Title=Multiple
Number of Profiles=7
Profile Names=10-year,25-year,50-year,1pct_min,100-year,1pct_plu,500-year
River Rch & RM= UNT 1064 IN LATR,Reach-1,4322
     917    1338    1707    1594    2156    2916    3453
River Rch & RM= UNT 1064 IN LATR,Reach-1,3500
    1067    1567    2007    1882    2545    3441    4105
Boundary for River Rch & Prof#=UNT 1064 IN LATR,Reach-1,1
Up Type=0
Dn Type=3
Dn Slope=0.005
Boundary for River Rch & Prof#=UNT 1064 IN LATR,Reach-1,2
Up Type=0
Dn Type=3
Dn Slope=0.005
Boundary for River Rch & Prof#=UNT 1064 IN LATR,Reach-1,3
Up Type=0
Dn Type=3
Dn Slope=0.005
Boundary for River Rch & Prof#=UNT 1064 IN LATR,Reach-1,4
Up Type=0
Dn Type=3
Dn Slope=0.005
Boundary for River Rch & Prof#=UNT 1064 IN LATR,Reach-1,5
Up Type=0
Dn Type=3
Dn Slope=0.005
Boundary for River Rch & Prof#=UNT 1064 IN LATR,Reach-1,6
Up Type=0
Dn Type=3
Dn Slope=0.005
Boundary for River Rch & Prof#=UNT 1064 IN LATR,Reach-1,7
Up Type=0
Dn Type=3
Dn Slope=0.005

--- UNT 0064 IN LATR.g01 (geometry) ---

Geom Title=Existing Conditions

River Reach=UNT 1064 IN LATR,Reach-1
Reach XY= 30
      2977528.47     10121283.73      2977651.00     10121329.51
      2977724.86     10121399.96      2977721.26     10121492.64
      2977755.33     10121538.99      2977964.29     10121611.75
      2978443.28     10121653.19      2978610.33     10121604.26
      2978834.07     10121593.71      2978979.57     10121658.48
      2979167.73     10121647.90      2979427.50     10121716.10
      2979554.84     10121810.45      2979604.01     10121936.51
      2979679.24     10122002.89      2979715.76     10121973.34
      2979739.12     10121801.86      2979783.90     10121766.76
      2979886.79     10121769.97      2979944.23     10121725.98
      2980306.46     10121689.14      2980335.11     10121713.88
      2980305.16     10121845.39      2980335.98     10121885.32
      2980412.36     10121899.21      2980508.28     10121784.19
      2980603.42     10121763.56      2980755.58     10121668.37
      2980939.75     10121616.21      2981058.47     10121663.73

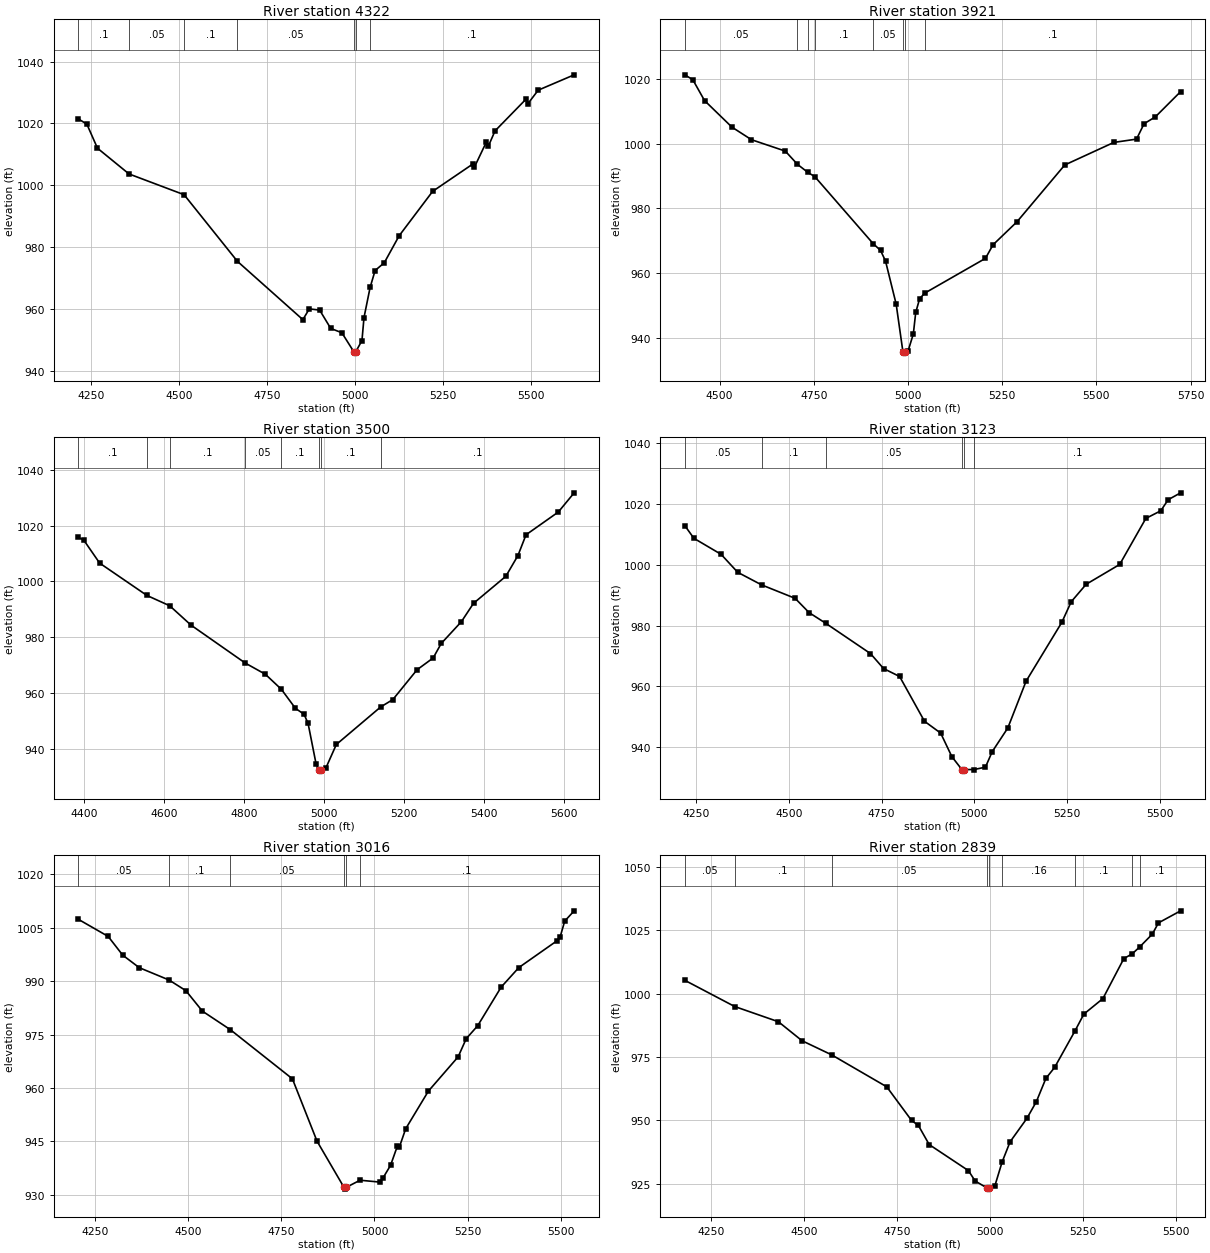
Type RM Length L Ch R = 1,4322,401,401,401
BEGIN DESCRIPTION:
UNT 1064 IN LATR 9.0
END DESCRIPTION:
XS GIS Cut Line= 4
      2977499.59     10122087.77      2977564.69     10121432.39
      2977686.22     10121072.15      2977586.76     10120717.53
#Sta/Elev= 30
  4215.1 1021.48  4239.3 1019.79  4269.4 1012.01  4358.9 1003.69  4515.2  996.98
  4666.6  975.44  4852.3  956.59  4870.5  960.07  4899.9  959.69  4931.4  953.75
  4962.9  952.36  4996.6  946.27  4999.4  945.77  5002.6  946.27  5020.0  949.82
  5025.8  957.28  5043.1  966.99  5057.3  972.47  5083.4  974.99  5125.6  983.72
  5220.6  998.06  5334.1 1006.86  5339.3 1005.93  5373.4 1014.09  5378.6 1012.63
  5397.6 1017.60  5486.1 1027.93  5491.3 1026.46  5520.2 1030.77  5622.2 1035.73
#Mann=7,-1,0
  4215.1     0.1       0  4358.9    0.05       0  4515.2     0.1       0
  4666.6    0.05       0  4996.6   0.035       0  5002.6    0.05       0
  5043.1     0.1       0
Bank Sta=4996.6,5002.6
Exp/Cntr=0.3,0.1

Type RM Length L Ch R = 1,3921,421,421,421
BEGIN DESCRIPTION:
UNT 1064 IN LATR 8.0
END DESCRIPTION:
XS GIS Cut Line= 3
      2977681.88     10122144.20      2977881.53     10121423.71
      2977846.92     10120856.90
#Sta/Elev= 30
  4407.9 1021.24  4429.1 1019.74  4460.3 1013.28  4532.9 1005.08  4584.8 1001.19
  4674.5  997.67  4706.9  993.57  4734.7  991.06  4752.8  989.78  4907.3  969.11
  4927.2  966.97  4940.4  963.71  4968.7  950.37  4986.5  935.73  4989.2  935.23
  4992.5  935.73  4999.9  935.76  5014.2  941.13  5020.6  947.82  5031.0  952.06
  5044.5  953.77  5205.6  964.52  5225.6  968.70  5289.3  975.83  5416.0  993.38
  5546.2 1000.35  5606.4 1001.37  5626.4 1006.12  5656.4 1008.25  5723.4 1016.05
#Mann=8,-1,0
  4407.9    0.05       0  4706.9     0.1       0  4734.7    0.05       0
  4752.8     0.1       0  4907.3    0.05       0  4986.5   0.035       0
  4992.5    0.05       0  5044.5     0.1       0
Bank Sta=4986.5,4992.5
Exp/Cntr=0.3,0.1

Type RM Length L Ch R = 1,3500,377,377,377
BEGIN DESCRIPTION:
UNT 1064 IN LATR 7.0
END DESCRIPTION:
XS GIS Cut Line= 3
      2978259.14     10122257.08      2978233.10     10121783.95
      2978341.60     10121024.41
#Sta/Elev= 30
  4384.8 1015.73  4398.2 1014.82  4438.2 1006.53  4556.5  994.95  4613.5  991.26
  4666.8  984.33  4802.6  970.74  4852.9  966.73  4893.0  961.34  4928.2  954.52
  4949.8  952.40  4959.9  949.11  4980.1  934.46  4987.2  932.53  4989.9  932.03
  4993.2  932.53  5004.0  933.01  5030.6  941.57  5141.7  955.03  5172.0  957.65
  5232.6  968.33  5273.0  972.57  5293.2  977.76  5343.7  985.57  5374.0  992.14
  5454.9 1001.82  5485.2 1009.25  5505.4 1016.68  5586.2 1024.83  5625.9 1031.71
#Mann=8,-1,0
  4384.8     0.1       0  4556.5    0.05       0  4613.5     0.1       0
  4802.6    0.05       0  4893.0     0.1       0  4987.2   0.035       0
  4993.2     0.1       0  5141.7     0.1       0
Bank Sta=4987.2,4993.2
Exp/Cntr=0.3,0.1

Type RM Length L Ch R = 1,3123,107,107,107
BEGIN DESCRIPTION:
UNT 1064 IN LATR 6.0
END DESCRIPTION:
XS GIS Cut Line= 3
      2978480.48     10122356.91      2978645.42     10121844.72
      2978558.62     10121050.44
#Sta/Elev= 30
  4219.4 1012.96  4243.8 1008.78  4317.3 1003.49  4362.1  997.57  4426.5  993.43
  4516.9  989.00  4554.5  984.30  4599.6  980.77  4720.1  970.80  4755.4  965.87
  4798.7  963.25  4865.8  948.50  4909.4  944.60  4939.6  936.85  4966.7  932.58
  4969.5  932.08  4972.7  932.58  4999.6  932.61  5030.1  933.38  5048.4  938.49
  5090.5  946.30  5139.7  961.70  5236.0  981.06  5261.5  987.88  5301.7  993.62
  5392.2 1000.16  5462.7 1015.32  5502.9 1017.83  5523.0 1021.49  5556.5 1023.75
#Mann=6,-1,0
  4219.4    0.05       0  4426.5     0.1       0  4599.6    0.05       0
  4966.7    0.07       0  4972.7    0.05       0  4999.6     0.1       0
Bank Sta=4966.7,4972.7
Exp/Cntr=0.3,0.1

Type RM Length L Ch R = 1,3016,177,177,177
BEGIN DESCRIPTION:
Mapping XS 5f7bfc77
END DESCRIPTION:
XS GIS Cut Line= 3
      2978538.46     10122360.48      2978741.58     10121683.40
      2978627.00     10121068.79
#Sta/Elev= 30
  4204.4 1007.36  4284.5 1002.56  4323.7  997.29  4368.1  993.78  4448.1  990.32
  4493.3  987.33  4537.7  981.58  4612.7  976.38  4779.5  962.58  4845.7  945.07
  4918.1  932.11  4920.9  931.61  4924.1  932.11  4961.3  934.11  5014.0  933.59
  5022.9  934.74  5043.2  938.28  5061.6  943.71  5066.7  943.35  5083.9  948.56
  5144.9  959.13  5224.8  968.75  5246.6  973.86  5277.2  977.46  5340.4  988.33
  5388.0  993.82  5490.8 1001.36  5498.5 1002.28  5511.1 1006.85  5536.5 1009.74
#Mann=6,-1,0
  4204.4    0.05       0  4448.1     0.1       0  4612.7    0.05       0
  4918.1    0.07       0  4924.1    0.05       0  4961.3     0.1       0
Bank Sta=4918.1,4924.1
Exp/Cntr=0.3,0.1

Type RM Length L Ch R = 1,2839,214,214,214
BEGIN DESCRIPTION:
Mapping XS aa717e7b
END DESCRIPTION:
XS GIS Cut Line= 3
      2978576.64     10122374.41      2978918.67     10121567.08
      2979015.88     10121119.20
#Sta/Elev= 30
  4178.7 1005.25  4313.0  994.91  4430.8  988.90  4494.4  981.41  4574.2  975.84
  4722.5  963.23  4789.4  949.96  4807.7  947.99  4836.8  940.45  4942.4  930.18
  4960.6  926.07  4992.1  923.38  4994.9  922.88  4998.1  923.38  5013.4  924.08
  5033.1  933.57  5054.6  941.54  5099.8  950.77  5125.3  957.37  5151.0  966.55
  5174.5  970.88  5229.1  985.22  5253.3  991.93  5304.5  998.03  5360.9 1013.81
  5383.7 1015.72  5403.6 1018.41  5437.5 1023.45  5454.1 1027.90  5513.8 1032.65
#Mann=9,-1,0
  4178.7    0.05       0  4313.0     0.1       0  4574.2    0.05       0
  4992.1   0.035       0  4998.1    0.05       0  5033.1    0.16       0
  5229.1     0.1       0  5383.7    0.05       0  5403.6     0.1       0
Bank Sta=4992.1,4998.1
Exp/Cntr=0.3,0.1

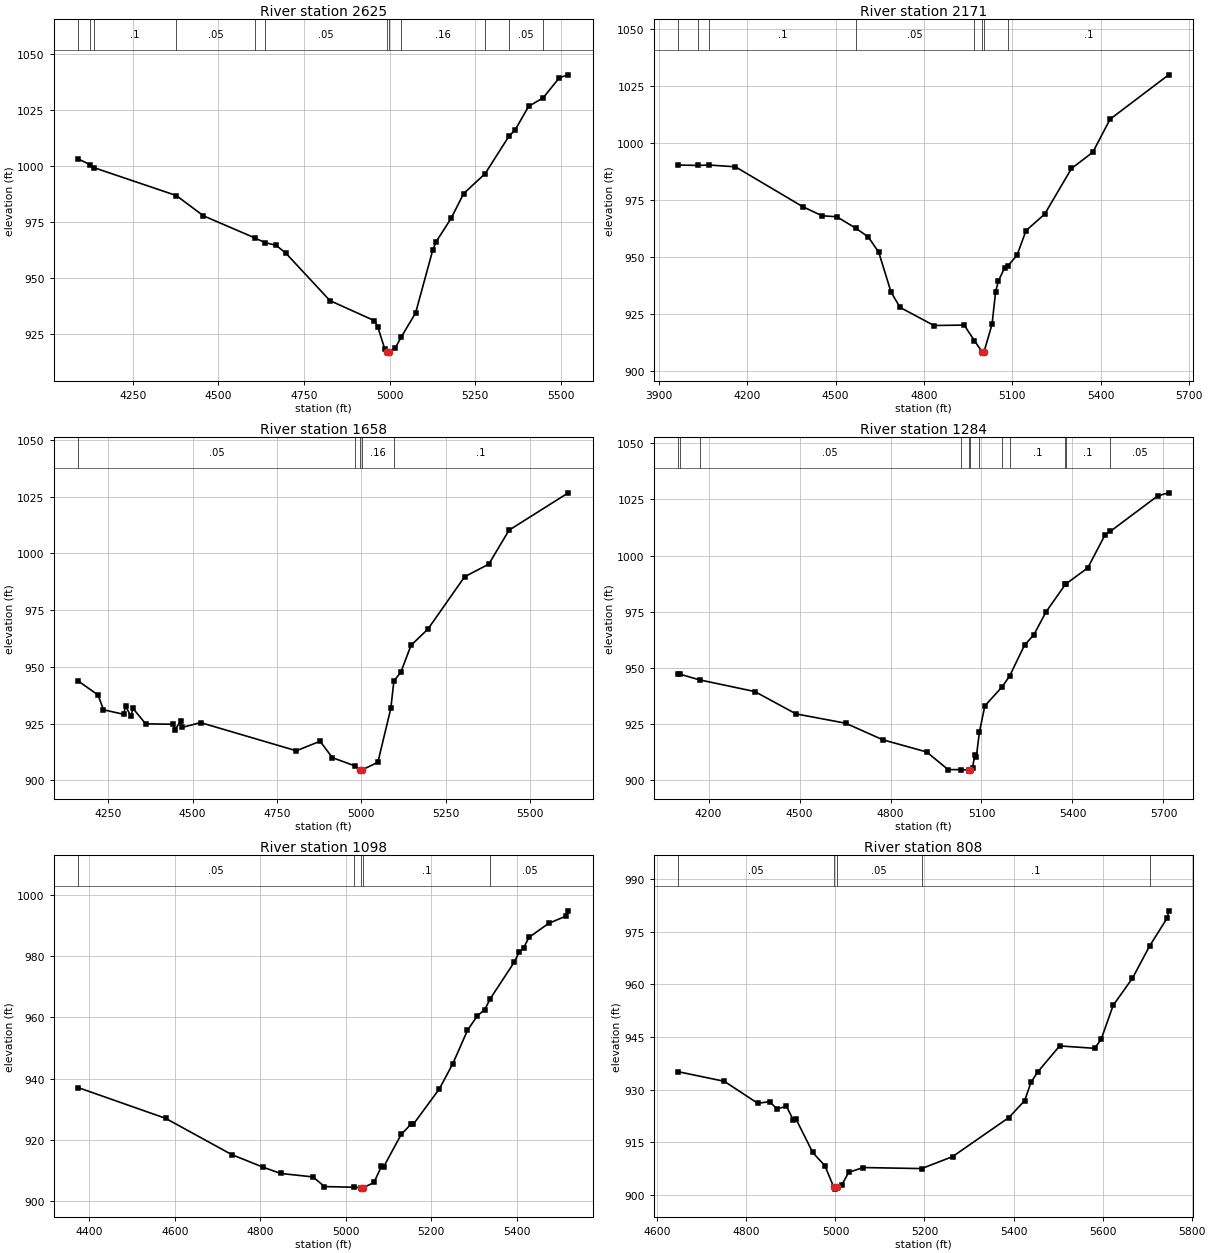
Type RM Length L Ch R = 1,2625,454,454,454
BEGIN DESCRIPTION:
UNT 1064 IN LATR 5.0
END DESCRIPTION:
XS GIS Cut Line= 3
      2978615.07     10122387.22      2979096.81     10121840.38
      2979109.82     10121137.97
#Sta/Elev= 30
  4090.6 1003.10  4124.8 1000.56  4136.3  999.19  4377.4  986.70  4456.5  977.65
  4608.5  967.63  4635.4  965.70  4669.0  964.45  4697.5  960.89  4826.0  939.73
  4956.0  930.75  4966.0  927.82  4986.0  918.10  4993.1  916.76  4995.8  916.26
  4999.1  916.76  5016.1  918.35  5033.8  923.38  5076.1  934.23  5126.1  962.30
  5136.1  966.08  5179.9  976.52  5216.1  987.53  5279.3  996.52  5349.2 1013.36
  5366.1 1015.87  5406.1 1026.57  5448.3 1030.35  5496.1 1039.39  5521.9 1040.65
#Mann=12,-1,0
  4090.6     0.1       0  4124.8    0.05       0  4136.3     0.1       0
  4377.4    0.05       0  4608.5     0.1       0  4635.4    0.05       0
  4993.1   0.035       0  4999.1    0.05       0  5033.8    0.16       0
  5279.3     0.1       0  5349.2    0.05       0  5448.3     0.1       0
Bank Sta=4993.1,4999.1
Exp/Cntr=0.3,0.1

Type RM Length L Ch R = 1,2171,513,513,513
BEGIN DESCRIPTION:
UNT 1064 IN LATR 4.0
END DESCRIPTION:
XS GIS Cut Line= 4
      2978771.27     10122465.39      2979352.89     10122048.71
      2979648.03     10121584.30      2979678.27     10121186.88
#Sta/Elev= 30
  3966.2  990.27  4032.3  990.13  4071.5  990.28  4159.6  989.53  4388.4  972.01
  4453.5  968.03  4503.9  967.57  4569.2  962.51  4610.8  958.71  4646.4  951.98
  4688.1  934.51  4718.6  927.79  4833.8  919.84  4936.4  920.02  4971.2  913.19
  4997.6  908.21  5000.4  907.71  5003.6  908.21  5031.1  920.43  5043.0  934.59
  5052.3  939.28  5073.5  945.16  5084.7  946.01  5115.8  950.69  5146.3  961.49
  5209.8  968.76  5300.7  988.78  5372.9  995.89  5431.7 1010.42  5630.5 1029.90
#Mann=8,-1,0
  3966.2     0.1       0  4032.3    0.05       0  4071.5     0.1       0
  4569.2    0.05       0  4971.2    0.16       0  4997.6    0.07       0
  5003.6    0.16       0  5084.7     0.1       0
Bank Sta=4997.6,5003.6
Exp/Cntr=0.3,0.1

Type RM Length L Ch R = 1,1658,374,374,374
BEGIN DESCRIPTION:
Mapping XS 8faecee5
END DESCRIPTION:
XS GIS Cut Line= 4
      2979566.21     10122512.96      2979872.21     10121955.20
      2979709.45     10121762.06      2979739.81     10121198.24
#Sta/Elev= 30
  4160.6  943.79  4219.9  937.56  4236.0  931.05  4295.7  929.07  4301.4  932.65
  4317.5  928.15  4323.2  931.71  4361.1  924.85  4442.6  924.68  4448.3  922.36
  4464.4  925.89  4470.1  923.32  4524.1  925.39  4807.8  912.98  4878.1  917.20
  4914.4  909.96  4980.5  906.35  4996.0  904.51  4998.7  904.01  5002.0  904.51
  5049.4  907.92  5087.8  931.64  5096.9  943.73  5117.8  947.72  5147.8  959.50
  5197.9  966.64  5306.5  989.68  5378.2  995.25  5438.3 1010.24  5614.0 1026.70
#Mann=5,-1,0
  4160.6    0.05       0  4980.5    0.16       0  4996.0    0.07       0
  5002.0    0.16       0  5096.9     0.1       0
Bank Sta=4996,5002
Exp/Cntr=0.3,0.1

Type RM Length L Ch R = 1,1284,186,186,186
BEGIN DESCRIPTION:
UNT 1064 IN LATR 2.0
END DESCRIPTION:
XS GIS Cut Line= 4
      2979834.64     10122556.56      2980116.78     10121970.59
      2980034.31     10121349.93      2979843.71     10121068.35
#Sta/Elev= 30
  4100.6  947.20  4107.3  947.12  4171.3  944.63  4352.5  939.46  4488.2  929.51
  4652.1  925.35  4774.6  917.97  4919.3  912.54  4989.9  904.69  5031.4  904.67
  5057.5  904.51  5060.3  904.01  5063.5  904.51  5070.6  905.53  5077.7  911.15
  5082.8  910.21  5093.1  921.36  5111.0  933.05  5168.5  941.62  5192.8  946.39
  5242.1  960.18  5272.4  964.68  5312.7  974.91  5376.7  987.20  5377.9  987.34
  5450.5  994.55  5507.4 1009.24  5524.2 1010.75  5681.1 1026.61  5717.1 1027.97
#Mann=12,-1,0
  4100.6    0.05       0  4107.3     0.1       0  4171.3    0.05       0
  5031.4     0.1       0  5057.5   0.035       0  5063.5     0.1       0
  5093.1    0.05       0  5168.5    0.16       0  5192.8     0.1       0
  5376.7    0.05       0  5377.9     0.1       0  5524.2    0.05       0
Bank Sta=5057.5,5063.5
Exp/Cntr=0.3,0.1

Type RM Length L Ch R = 1,1098,290,290,290
BEGIN DESCRIPTION:
Mapping XS d1eaa2f4
END DESCRIPTION:
XS GIS Cut Line= 3
      2980105.93     10122292.05      2980272.61     10121647.48
      2980073.37     10121208.89
#Sta/Elev= 30
  4373.6  937.05  4578.4  926.99  4733.4  915.11  4807.0  910.98  4847.6  908.95
  4923.7  907.81  4950.3  904.65  5019.1  904.45  5035.7  904.32  5038.5  903.82
  5041.7  904.32  5066.2  905.99  5083.8  911.31  5089.3  911.21  5129.9  921.70
  5153.0  925.09  5158.5  925.07  5219.2  936.60  5250.8  944.86  5285.1  955.77
  5307.9  960.48  5325.5  962.56  5338.7  966.18  5394.7  978.10  5405.9  981.33
  5416.9  982.83  5428.8  986.16  5474.9  990.74  5515.6  993.15  5521.1  994.87
#Mann=5,-1,0
  4373.6    0.05       0  5019.1     0.1       0  5035.7   0.035       0
  5041.7     0.1       0  5338.7    0.05       0
Bank Sta=5035.7,5041.7
Exp/Cntr=0.3,0.1

Type RM Length L Ch R = 1,808,383,383,383
BEGIN DESCRIPTION:
Mapping XS ccb94553
END DESCRIPTION:
XS GIS Cut Line= 4
      2980183.22     10122199.53      2980379.38     10121855.81
      2980438.41     10121569.35      2980183.31     10121244.84
#Sta/Elev= 30
  4647.3  935.10  4750.3  932.38  4825.2  926.13  4852.5  926.54  4868.4  924.52
  4890.0  925.22  4905.8  921.26  4911.6  921.56  4949.0  912.07  4976.4  908.26
  4996.4  902.11  4999.1  901.61  5002.4  902.11  5013.8  902.72  5029.7  906.37
  5061.9  907.77  5193.6  907.47  5263.1  910.89  5389.6  922.04  5424.9  926.86
  5439.3  932.09  5453.8  934.97  5503.5  942.47  5582.1  941.79  5596.6  944.31
  5623.7  954.05  5667.1  961.80  5705.7  971.01  5745.7  979.10  5748.3  981.02
#Mann=5,-1,0
  4647.3    0.05       0  4996.4   0.035       0  5002.4    0.05       0
  5193.6     0.1       0  5705.7    0.05       0
Bank Sta=4996.4,5002.4
Exp/Cntr=0.3,0.1

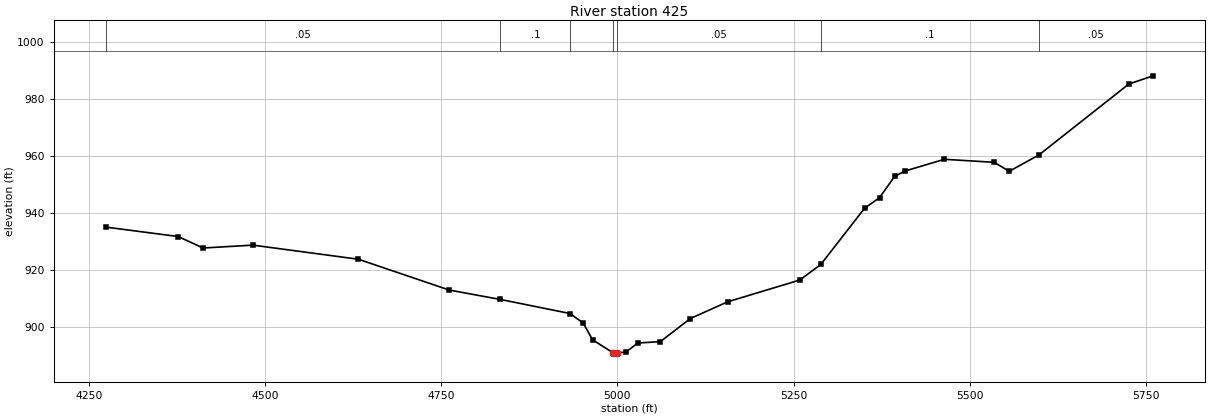
Type RM Length L Ch R = 1,425,0,0,0
BEGIN DESCRIPTION:
UNT 1064 IN LATR 1.0
END DESCRIPTION:
XS GIS Cut Line= 4
      2980206.35     10122194.28      2980702.85     10121815.37
      2980611.39     10121571.48      2980184.55     10121149.00
#Sta/Elev= 30
  4274.3  935.18  4376.8  931.88  4412.2  927.85  4482.9  928.86  4632.5  923.91
  4761.4  913.10  4834.1  909.79  4932.8  904.87  4951.4  901.52  4964.7  895.64
  4993.7  891.12  4996.5  890.62  4999.7  891.12  5011.9  891.29  5028.8  894.52
  5060.8  894.99  5103.5  903.11  5156.4  908.98  5258.8  916.62  5288.6  922.09
  5350.7  941.82  5372.0  945.54  5393.1  952.94  5407.3  954.81  5463.9  958.98
  5534.6  957.91  5555.8  954.76  5597.9  960.48  5725.5  985.38  5759.9  988.26
#Mann=7,-1,0
  4274.3    0.05       0  4834.1     0.1       0  4932.8    0.05       0
  4993.7   0.035       0  4999.7    0.05       0  5288.6     0.1       0
  5597.9    0.05       0
Bank Sta=4993.7,4999.7
Exp/Cntr=0.3,0.1

Chan Stop Cuts=-1