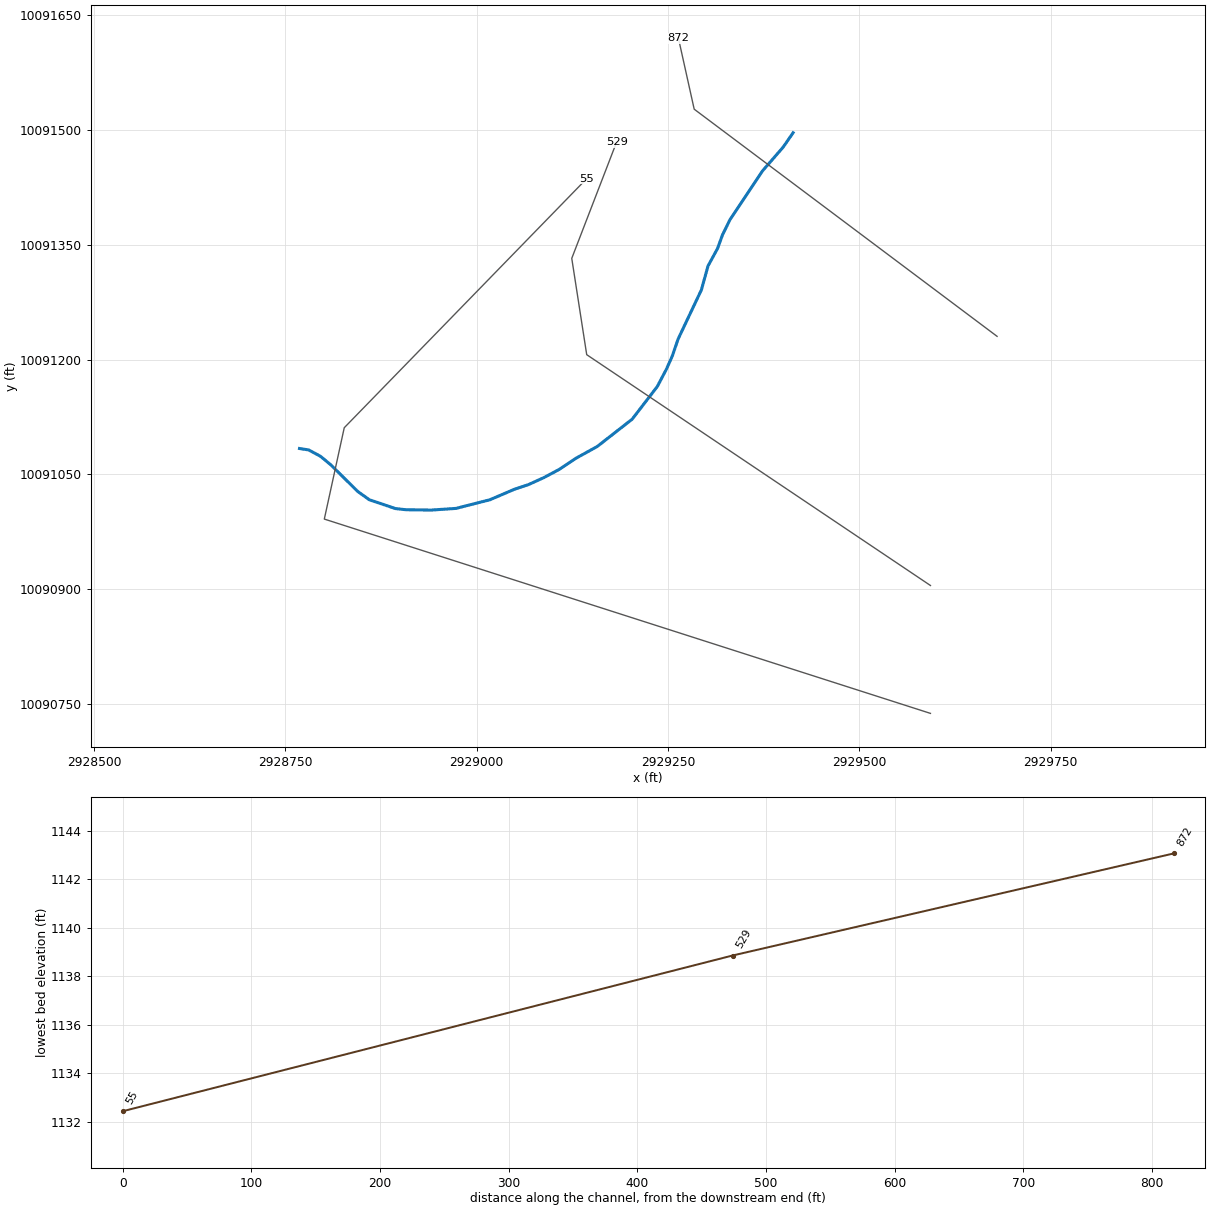
--- UNT 0065 IN LATR.prj (project) ---

Proj Title=UNT 1065 IN LATR Base Level Engineering
Current Plan=p01
Default Exp/Contr=0.3,0.1
English Units
Geom File=g01
Flow File=f01
Plan File=p01
Y Axis Title=Elevation
X Axis Title(PF)=Main Channel Distance
X Axis Title(XS)=Station
BEGIN DESCRIPTION:
UNT 1065 IN LATR
END DESCRIPTION:
DSS Export Rating Curves= 0
DSS Export Rating Curve Sorted= 0
DSS Export Volume Flow Curves= 0
DXF OffsetX= 0
DXF OffsetY= 0
DXF ScaleX= 1
DXF ScaleY= 10

--- UNT 0065 IN LATR.p01 (plan) ---

Plan Title=Multiple Run
Short Identifier=Multiple
Geom File=g01
Flow File=f01
Subcritical Flow
K Sum by GR= 0
Std Step Tol= 0.01
Critical Tol= 0.01
Num of Std Step Trials= 20
Max Error Tol= 0.3
Flow Tol Ratio= 0.001
Split Flow NTrial= 30
Split Flow Tol= 0.02
Split Flow Ratio= 0.02
Log Output Level= 0
Friction Slope Method= 1
Unsteady Friction Slope Method= 2
Unsteady Bridges Friction Slope Method= 1
Parabolic Critical Depth
Global Vel Dist=  1 , 1 , 1
Global Log Level= 0
CheckData=True
Encroach Param= -1, 0, 0, 0
BEGIN DESCRIPTION:
Multiple Run
END DESCRIPTION:

--- UNT 0065 IN LATR.f01 (steady flow) ---

Flow Title=Multiple
Program Version=4.10
Number of Profiles= 7
Profile Names=10-year,25-year,50-year,1pct_min,100-year,1pct_plu,500-year
River Rch & RM=UNT 1065 IN LATR,Reach-1         ,872
     753    1080    1360    1255    1698    2296    2653
Boundary for River Rch & Prof#=UNT 1065 IN LATR,Reach-1         , 1
Up Type= 0
Dn Type= 3
Dn Slope=0.014
Boundary for River Rch & Prof#=UNT 1065 IN LATR,Reach-1         , 2
Up Type= 0
Dn Type= 3
Dn Slope=0.014
Boundary for River Rch & Prof#=UNT 1065 IN LATR,Reach-1         , 3
Up Type= 0
Dn Type= 3
Dn Slope=0.014
Boundary for River Rch & Prof#=UNT 1065 IN LATR,Reach-1         , 4
Up Type= 0
Dn Type= 3
Dn Slope=0.014
Boundary for River Rch & Prof#=UNT 1065 IN LATR,Reach-1         , 5
Up Type= 0
Dn Type= 3
Dn Slope=0.014
Boundary for River Rch & Prof#=UNT 1065 IN LATR,Reach-1         , 6
Up Type= 0
Dn Type= 3
Dn Slope=0.014
Boundary for River Rch & Prof#=UNT 1065 IN LATR,Reach-1         , 7
Up Type= 0
Dn Type= 3
Dn Slope=0.014
DSS Import GetInterval= 0
DSS Import GetPeak= 0
DSS Import FillOption= 0

--- UNT 0065 IN LATR.g01 (geometry) ---

Geom Title=Existing Conditions
Program Version=4.10

River Reach=UNT 1065 IN LATR,Reach-1
Reach XY= 30
      2929413.51     10091496.36      2929400.54     10091477.59
      2929373.44     10091446.38      2929330.98     10091382.69
      2929321.12     10091362.63      2929314.82     10091345.24
      2929302.27     10091322.16      2929293.66     10091291.01
      2929263.13     10091226.51      2929255.74     10091204.85
      2929247.91     10091187.26        2929236.     10091164.67
       2929203.2     10091122.02      2929157.48     10091086.31
      2929129.65     10091070.94      2929107.47     10091056.16
      2929087.68     10091045.64      2929067.36     10091036.41
      2929049.75     10091030.63      2929017.22     10091016.72
      2928972.94     10091005.45      2928940.54     10091003.27
      2928907.51      10091003.7      2928893.89     10091005.23
      2928859.73     10091016.75      2928844.46     10091027.69
      2928809.34     10091062.42      2928795.89     10091073.54
      2928780.48     10091081.84      2928768.47     10091083.73

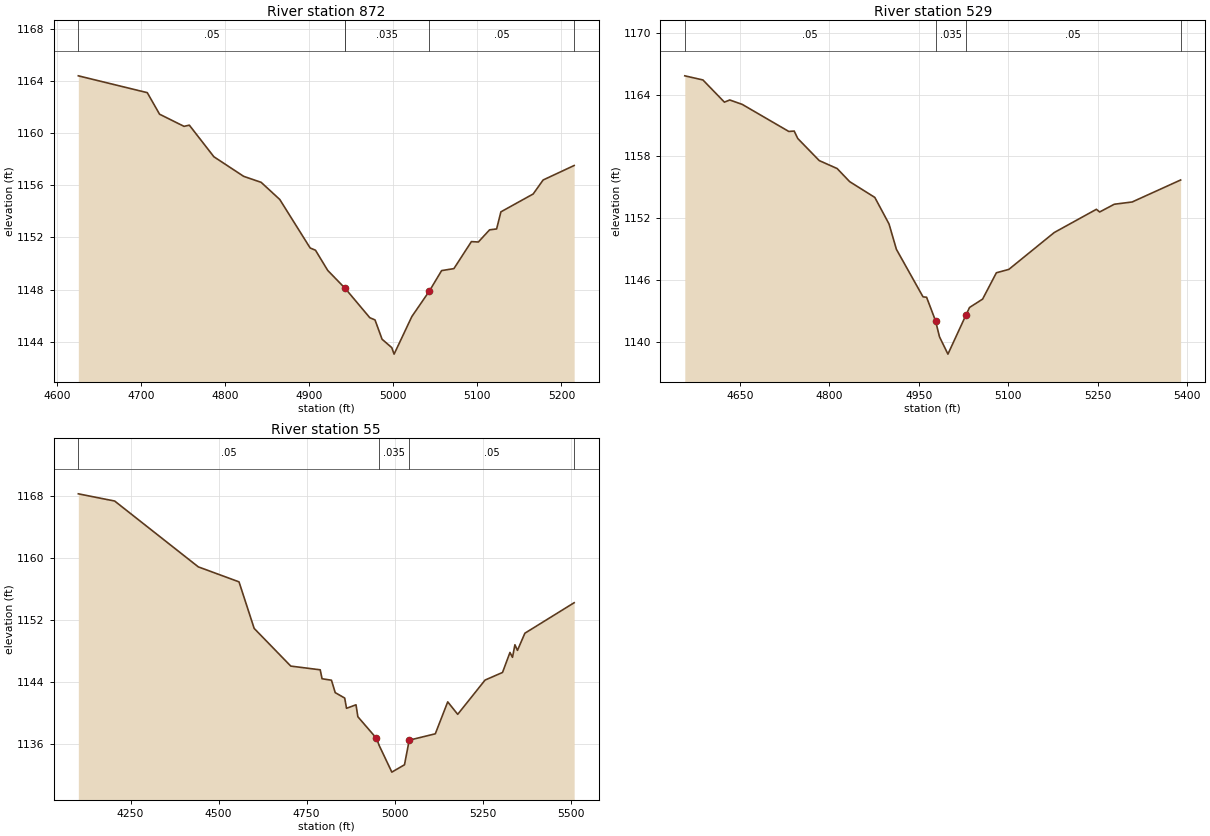
Type RM Length L Ch R = 1 ,872     ,343,343,343
BEGIN DESCRIPTION:
UNT 1065 IN LATR 2.0
END DESCRIPTION:
XS GIS Cut Line= 3
      2929680.05     10091230.28      2929284.24     10091527.14
      2929263.67     10091619.72
#Sta/Elev= 30
  4625.5 1164.38  4707.5 1163.09  4722.1 1161.44  4751.2 1160.51  4757.5  1160.6
  4786.7 1158.18  4822.1 1156.68  4842.9 1156.22    4865 1154.91  4901.2 1151.19
  4907.5 1151.02  4922.1 1149.47  4942.9 1148.09  4972.1 1145.85  4978.3 1145.68
  4986.7  1144.2  4998.2 1143.56    5001 1143.06  5022.1 1145.94  5042.9 1147.89
  5057.5 1149.46  5072.1 1149.61  5092.9 1151.68  5101.2 1151.65  5114.5 1152.58
  5122.9 1152.65    5128 1153.96  5166.4 1155.33  5178.2  1156.4  5215.1 1157.51
#Mann= 5 ,-1 , 0
  4625.5     .05       0  4942.9      .1       0  4942.9    .035       0
  5042.9     .05       0  5215.1     .16       0
Bank Sta=4942.9,5042.9
XS Rating Curve= 0 ,0
Exp/Cntr=0.3,0.1

Type RM Length L Ch R = 1 ,529     ,474,474,474
BEGIN DESCRIPTION:
Mapping XS e361e18c
END DESCRIPTION:
XS GIS Cut Line= 4
        2929593.      10090904.7      2929143.79     10091206.34
      2929124.25     10091332.21      2929182.85     10091484.13
#Sta/Elev= 30
  4557.9 1165.81  4588.3 1165.41  4624.3 1163.26  4633.3 1163.47  4654.3 1163.04
  4732.3 1160.42  4741.3 1160.46  4747.3 1159.74  4783.3  1157.6  4813.3 1156.83
  4834.3 1155.56  4876.5 1154.03  4900.3 1151.46  4912.7    1149  4957.3  1144.4
  4963.3 1144.36  4978.3 1142.08  4984.9 1140.53  4999.1 1138.85  5029.3 1142.64
  5035.3 1143.37  5057.2 1144.18  5080.3 1146.73  5101.2 1147.06  5177.3 1150.63
    5248 1152.88  5253.4 1152.62    5278 1153.37    5308 1153.59  5389.2 1155.72
#Mann= 4 ,-1 , 0
  4557.9     .05       0  4978.3    .035       0  5029.3     .05       0
  5389.2     .16       0
Bank Sta=4978.3,5029.3
XS Rating Curve= 0 ,0
Exp/Cntr=0.3,0.1

Type RM Length L Ch R = 1 ,55      ,0,0,0
BEGIN DESCRIPTION:
UNT 1065 IN LATR 1.0
END DESCRIPTION:
XS GIS Cut Line= 4
      2929592.97      10090737.6       2928800.9      10090991.5
      2928826.94     10091110.85      2929143.66     10091436.24
#Sta/Elev= 30
  4101.6 1168.31  4204.8 1167.38  4442.4 1158.89  4557.9 1156.96  4600.9 1150.96
  4704.9  1146.1  4788.5 1145.62  4793.7 1144.47  4820.4 1144.28  4831.1 1142.68
    4858 1141.98  4863.2 1140.66  4890.1 1141.11  4895.4 1139.57  4948.2 1136.79
  4956.1 1135.85  4991.9 1132.43  5027.8 1133.38  5041.2 1136.55  5115.3 1137.37
  5150.6 1141.49  5178.9 1139.88  5256.6  1144.3  5306.2 1145.28  5327.3 1147.86
  5334.5 1147.23  5341.4 1148.85  5348.6 1148.13  5369.7 1150.34  5509.6 1154.27
#Mann= 4 ,-1 , 0
  4101.6     .05       0  4956.1    .035       0  5041.2     .05       0
  5509.6      .1       0
Bank Sta=4948.2,5041.2
XS Rating Curve= 0 ,0
Exp/Cntr=0.3,0.1

Chan Stop Cuts=-1
Use User Specified Reach Order=0
Composite Channel Slope=5