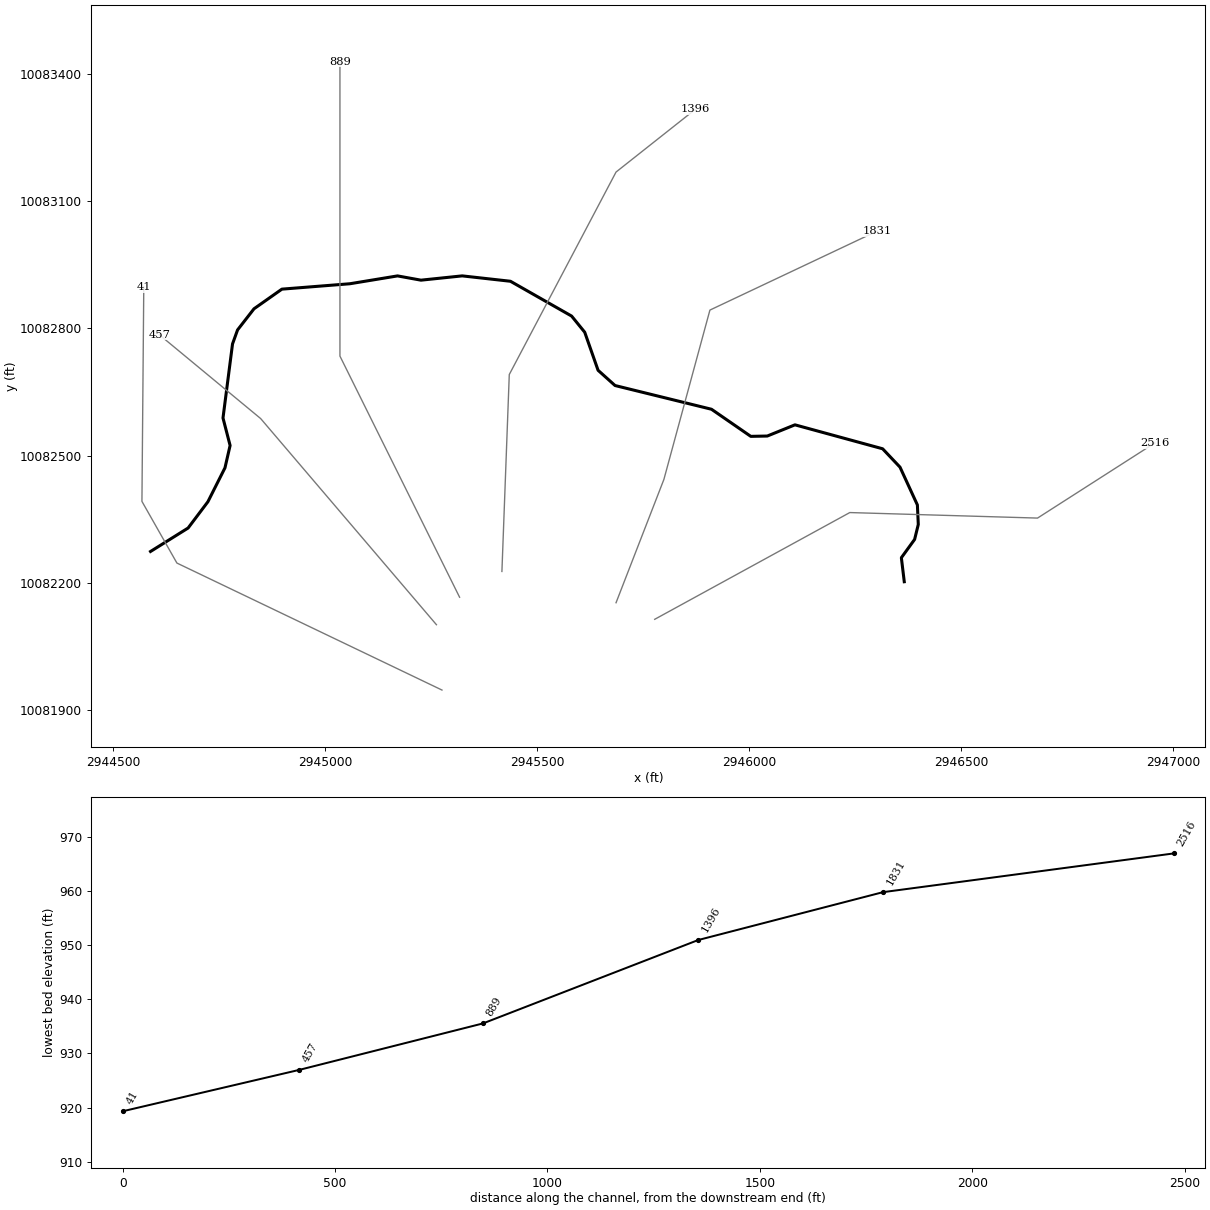
--- UNT 1005 IN LATR.prj (project) ---

Proj Title=UNT 1005 IN LATR Base Level Engineering
Current Plan=p01
Default Exp/Contr=0.3,0.1
English Units
Geom File=g01
Flow File=f01
Plan File=p01
Y Axis Title=Elevation
X Axis Title(PF)=Main Channel Distance
X Axis Title(XS)=Station
BEGIN DESCRIPTION:
UNT 1005 IN LATR
END DESCRIPTION:
DSS Export Rating Curves= 0
DSS Export Rating Curve Sorted= 0
DSS Export Volume Flow Curves= 0
DXF OffsetX= 0
DXF OffsetY= 0
DXF ScaleX= 1
DXF ScaleY= 10

--- UNT 1005 IN LATR.p01 (plan) ---

Plan Title=Multiple Run
Short Identifier=Multiple
Geom File=g01
Flow File=f01
Subcritical Flow
K Sum by GR= 0
Std Step Tol= 0.01
Critical Tol= 0.01
Num of Std Step Trials= 20
Max Error Tol= 0.3
Flow Tol Ratio= 0.001
Split Flow NTrial= 30
Split Flow Tol= 0.02
Split Flow Ratio= 0.02
Log Output Level= 0
Friction Slope Method= 1
Unsteady Friction Slope Method= 2
Unsteady Bridges Friction Slope Method= 1
Parabolic Critical Depth
Global Vel Dist=  1 , 1 , 1
Global Log Level= 0
CheckData=True
Encroach Param= -1, 0, 0, 0
BEGIN DESCRIPTION:
Multiple Run
END DESCRIPTION:

--- UNT 1005 IN LATR.f01 (steady flow) ---

Flow Title=Multiple
Program Version=4.10
Number of Profiles= 7
Profile Names=10-year,25-year,50-year,1pct_min,100-year,1pct_plu,500-year
River Rch & RM=UNT 1005 IN LATR,Reach-1         ,2516
     847    1220    1542    1427    1929    2609    3032
Boundary for River Rch & Prof#=UNT 1005 IN LATR,Reach-1         , 1
Up Type= 0
Dn Type= 3
Dn Slope=0.019
Boundary for River Rch & Prof#=UNT 1005 IN LATR,Reach-1         , 2
Up Type= 0
Dn Type= 3
Dn Slope=0.019
Boundary for River Rch & Prof#=UNT 1005 IN LATR,Reach-1         , 3
Up Type= 0
Dn Type= 3
Dn Slope=0.019
Boundary for River Rch & Prof#=UNT 1005 IN LATR,Reach-1         , 4
Up Type= 0
Dn Type= 3
Dn Slope=0.019
Boundary for River Rch & Prof#=UNT 1005 IN LATR,Reach-1         , 5
Up Type= 0
Dn Type= 3
Dn Slope=0.019
Boundary for River Rch & Prof#=UNT 1005 IN LATR,Reach-1         , 6
Up Type= 0
Dn Type= 3
Dn Slope=0.019
Boundary for River Rch & Prof#=UNT 1005 IN LATR,Reach-1         , 7
Up Type= 0
Dn Type= 3
Dn Slope=0.019
DSS Import GetInterval= 0
DSS Import GetPeak= 0
DSS Import FillOption= 0

--- UNT 1005 IN LATR.g01 (geometry) ---

Geom Title=Existing Conditions

River Reach=UNT 1005 IN LATR,Reach-1
Reach XY= 30
      2946365.81     10082202.38      2946358.95     10082259.04
      2946390.19     10082302.13      2946398.87     10082337.40
      2946396.74     10082383.47      2946355.75     10082472.58
      2946314.76     10082515.90      2946108.06     10082572.37
      2946042.75     10082545.95      2946003.88     10082545.19
      2945911.26     10082609.10      2945683.82     10082665.05
      2945643.80     10082700.98      2945612.30     10082790.75
      2945581.38     10082828.84      2945437.18     10082910.91
      2945323.42     10082923.62      2945226.20     10082913.50
      2945170.89     10082923.56      2945058.36     10082905.03
      2944898.25     10082892.34      2944832.44     10082845.99
      2944793.68     10082796.15      2944781.81     10082763.11
      2944759.34     10082588.47      2944776.10     10082523.66
      2944764.01     10082470.99      2944723.71     10082390.94
      2944677.06     10082329.04      2944588.47     10082273.73

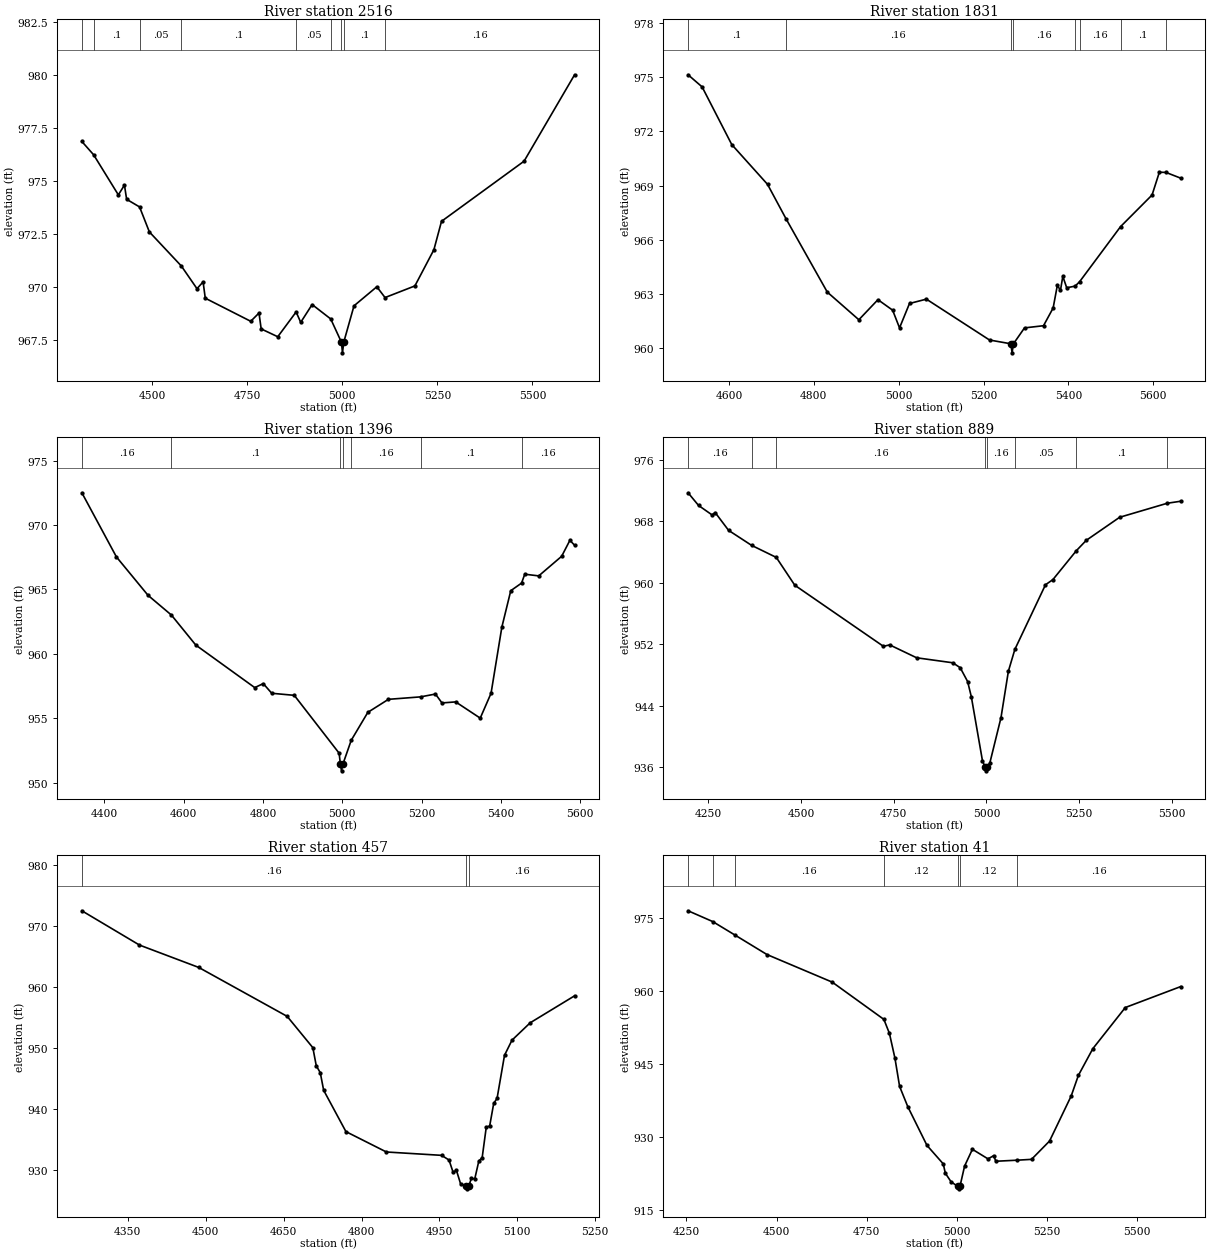
Type RM Length L Ch R = 1,2516,685,685,685
BEGIN DESCRIPTION:
UNT 1005 IN LATR 5.0
END DESCRIPTION:
XS GIS Cut Line= 4
      2945777.33     10082113.78      2946237.37     10082365.50
      2946680.07     10082352.48      2946956.51     10082529.57
#Sta/Elev= 30
  4315.1  976.88  4346.1  976.25  4411.0  974.36  4427.1  974.82  4432.8  974.15
  4466.8  973.79  4492.6  972.61  4576.7  971.00  4617.8  969.93  4633.9  970.25
  4639.6  969.48  4759.1  968.39  4780.9  968.78  4786.6  968.03  4830.2  967.66
  4878.5  968.83  4890.6  968.34  4920.6  969.18  4969.5  968.50  4997.7  967.40
  5000.4  966.90  5003.7  967.40  5030.7  969.12  5090.7  970.02  5112.3  969.51
  5190.8  970.06  5240.8  971.77  5260.8  973.11  5477.9  975.95  5610.7  980.03
#Mann=9,-1,0
  4315.1    0.05       0  4346.1     0.1       0  4466.8    0.05       0
  4576.7     0.1       0  4878.5    0.05       0  4969.5     0.1       0
  4997.7    0.07       0  5003.7     0.1       0  5112.3    0.16       0
Bank Sta=4997.7,5003.7
Exp/Cntr=0.3,0.1

Type RM Length L Ch R = 1,1831,435,435,435
BEGIN DESCRIPTION:
UNT 1005 IN LATR 4.0
END DESCRIPTION:
XS GIS Cut Line= 4
      2945686.17     10082152.87      2945799.00     10082443.63
      2945907.51     10082842.93      2946301.56     10083029.13
#Sta/Elev= 30
  4503.5  975.13  4536.6  974.46  4606.5  971.27  4690.8  969.07  4734.3  967.17
  4831.7  963.11  4906.1  961.58  4951.1  962.69  4985.7  962.11  5002.0  961.13
  5025.5  962.48  5065.3  962.72  5214.1  960.46  5264.5  960.25  5267.3  959.75
  5270.5  960.25  5296.6  961.13  5341.4  961.25  5364.1  962.23  5374.0  963.48
  5381.4  963.21  5386.9  963.98  5396.1  963.35  5416.0  963.44  5426.7  963.69
  5523.0  966.73  5597.3  968.48  5614.5  969.74  5630.0  969.73  5665.0  969.41
#Mann=8,-1,0
  4503.5     0.1       0  4734.3    0.16       0  5264.5    0.07       0
  5270.5    0.16       0  5416.0     0.1       0  5426.7    0.16       0
  5523.0     0.1       0  5630.0    0.16       0
Bank Sta=5264.5,5270.5
Exp/Cntr=0.3,0.1

Type RM Length L Ch R = 1,1396,507,507,507
BEGIN DESCRIPTION:
UNT 1005 IN LATR 3.0
END DESCRIPTION:
XS GIS Cut Line= 4
      2945417.05     10082226.62      2945434.42     10082691.02
      2945686.15     10083168.45      2945872.79     10083316.03
#Sta/Elev= 30
  4343.2  972.50  4430.4  967.52  4510.1  964.54  4569.0  963.01  4630.5  960.68
  4779.1  957.38  4800.6  957.69  4822.0  956.94  4878.8  956.78  4991.9  952.29
  4995.2  951.42  4997.9  950.92  5001.2  951.42  5022.4  953.29  5064.3  955.46
  5116.2  956.47  5197.2  956.66  5234.8  956.88  5251.2  956.19  5285.8  956.27
  5347.7  955.01  5375.0  956.94  5402.2  962.07  5424.7  964.90  5451.9  965.49
  5460.0  966.18  5495.2  966.05  5553.0  967.57  5573.8  968.81  5585.6  968.43
#Mann=7,-1,0
  4343.2    0.16       0  4569.0     0.1       0  4995.2    0.07       0
  5001.2     0.1       0  5022.4    0.16       0  5197.2     0.1       0
  5451.9    0.16       0
Bank Sta=4995.2,5001.2
Exp/Cntr=0.3,0.1

Type RM Length L Ch R = 1,889,432,432,432
BEGIN DESCRIPTION:
UNT 1005 IN LATR 2.0
END DESCRIPTION:
XS GIS Cut Line= 3
      2945317.25     10082165.81      2945035.11     10082734.43
      2945035.11     10083428.77
#Sta/Elev= 30
  4195.2  971.71  4223.5  970.06  4259.9  968.83  4268.3  969.14  4304.5  966.82
  4366.5  964.87  4433.2  963.30  4483.1  959.68  4722.2  951.73  4739.0  951.92
  4811.8  950.24  4909.3  949.59  4929.3  948.95  4949.3  947.15  4959.3  945.17
  4989.3  936.85  4996.3  936.03  4999.0  935.53  5002.3  936.03  5009.3  936.57
  5039.3  942.45  5059.3  948.50  5076.7  951.33  5159.3  959.74  5179.3  960.41
  5242.7  964.18  5269.3  965.52  5359.3  968.52  5488.0  970.35  5524.3  970.61
#Mann=8,-1,0
  4195.2    0.16       0  4366.5     0.1       0  4433.2    0.16       0
  4996.3    0.07       0  5002.3    0.16       0  5076.7    0.05       0
  5242.7     0.1       0  5488.0    0.05       0
Bank Sta=4996.3,5002.3
Exp/Cntr=0.3,0.1

Type RM Length L Ch R = 1,457,416,416,416
BEGIN DESCRIPTION:
Mapping XS d96719ca
END DESCRIPTION:
XS GIS Cut Line= 3
      2945262.62     10082101.08      2944848.15     10082587.16
      2944609.44     10082784.63
#Sta/Elev= 30
  4261.6  972.55  4372.5  966.93  4486.7  963.26  4656.9  955.24  4706.3  950.11
  4712.9  947.14  4720.6  946.01  4727.1  943.13  4770.0  936.35  4847.9  933.01
  4954.2  932.46  4968.5  931.69  4976.3  929.69  4982.8  929.98  4990.7  927.81
  5000.8  927.47  5003.6  926.97  5006.8  927.47  5011.5  928.71  5018.0  928.59
  5025.8  931.51  5032.3  932.08  5040.2  937.10  5046.7  937.26  5054.5  940.97
  5061.0  941.81  5075.3  948.86  5089.7  951.34  5124.8  954.19  5210.2  958.61
#Mann=3,-1,0
  4261.6    0.16       0  5000.8    0.07       0  5006.8    0.16       0
Bank Sta=5000.8,5006.8
Exp/Cntr=0.3,0.1

Type RM Length L Ch R = 1,41,0,0,0
BEGIN DESCRIPTION:
UNT 1005 IN LATR 1.0
END DESCRIPTION:
XS GIS Cut Line= 4
      2945275.70     10081946.95      2944650.67     10082246.44
      2944568.20     10082391.84      2944572.54     10082897.49
#Sta/Elev= 30
  4254.8  976.58  4323.1  974.36  4384.4  971.60  4473.5  967.57  4654.4  961.89
  4797.6  954.22  4813.0  951.34  4828.3  946.23  4841.2  940.42  4863.9  936.25
  4917.1  928.27  4962.2  924.47  4968.0  922.55  4983.9  920.78  5002.5  919.83
  5005.3  919.33  5008.5  919.83  5021.4  924.02  5043.0  927.47  5086.3  925.50
  5102.2  926.17  5107.9  925.01  5167.6  925.23  5206.9  925.40  5256.9  929.17
  5316.9  938.45  5336.9  942.70  5376.9  948.19  5466.9  956.66  5620.7  960.98
#Mann=7,-1,0
  4254.8    0.05       0  4323.1     0.1       0  4384.4    0.16       0
  4797.6    0.12       0  5002.5    0.07       0  5008.5    0.12       0
  5167.6    0.16       0
Bank Sta=5002.5,5008.5
Exp/Cntr=0.3,0.1

Chan Stop Cuts=-1