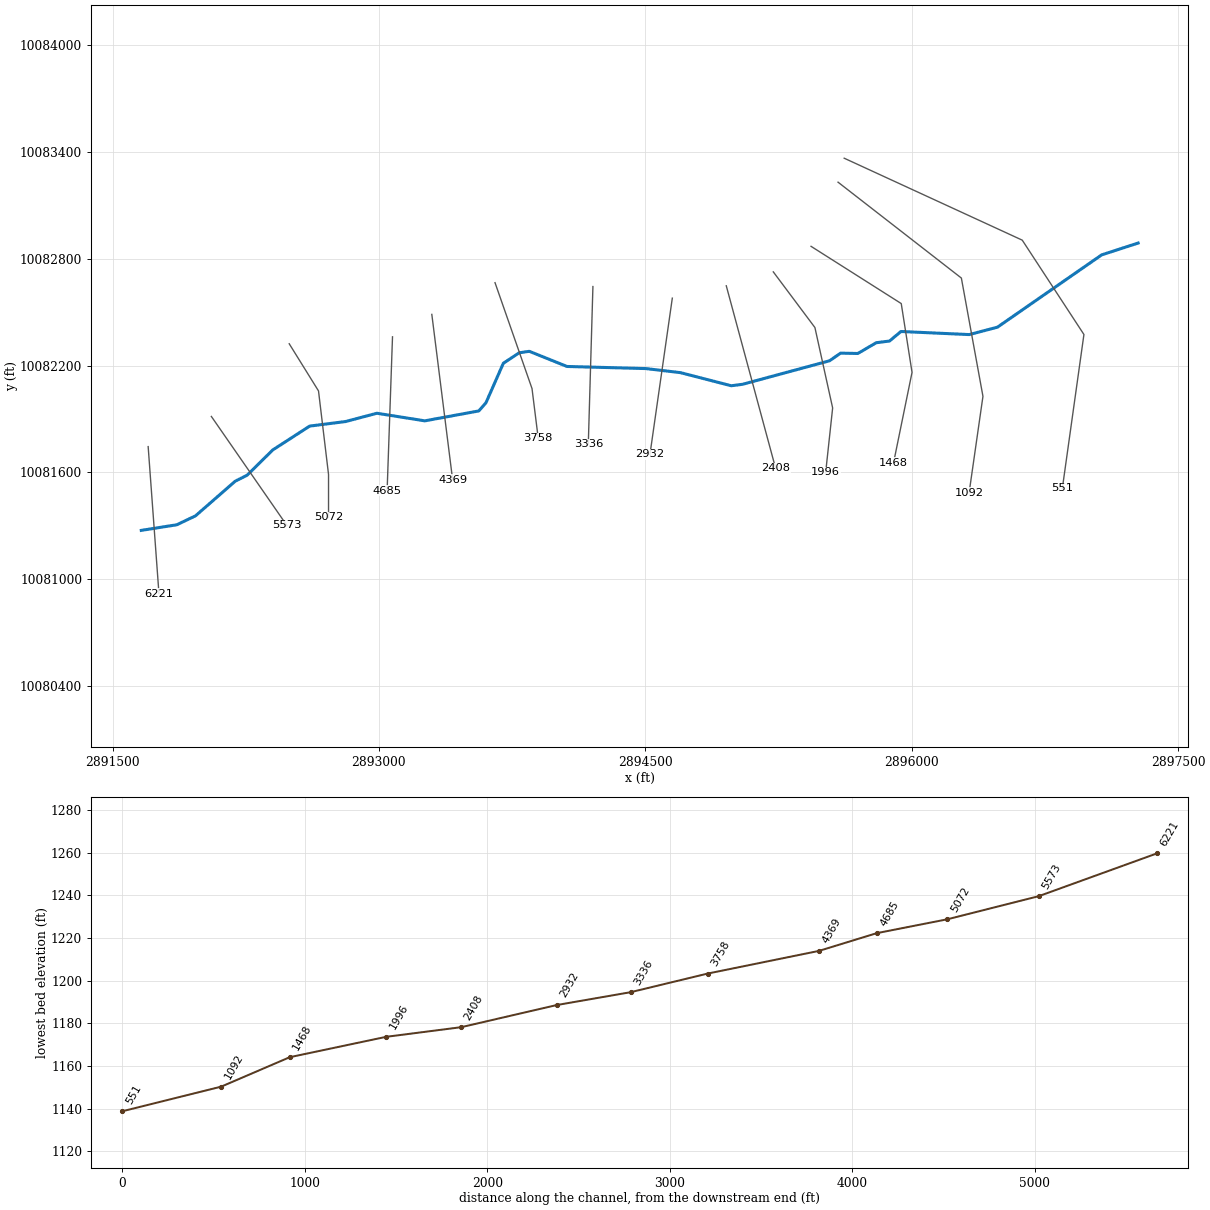
--- UNT 1006 IN LATR.prj (project) ---

Proj Title=UNT 1006 IN LATR Base Level Engineering
Current Plan=p01
Default Exp/Contr=0.3,0.1
English Units
Geom File=g01
Flow File=f01
Plan File=p01
BEGIN DESCRIPTION:
UNT 1006 IN LATR
END DESCRIPTION:

--- UNT 1006 IN LATR.p01 (plan) ---

Plan Title=Multiple Run
Short Identifier=Multiple
Geom File=g01
Flow File=f01
Subcritical Flow
K Sum by GR= 0
Std Step Tol= 0.01
Critical Tol= 0.01
Num of Std Step Trials= 20
Max Error Tol= 0.3
Flow Tol Ratio= 0.001
Split Flow NTrial= 30
Split Flow Tol= 0.02
Split Flow Ratio= 0.02
Log Output Level= 0
Friction Slope Method= 1
Unsteady Friction Slope Method= 2
Unsteady Bridges Friction Slope Method= 1
Parabolic Critical Depth
Global Vel Dist=  1 , 1 , 1
Global Log Level= 0
CheckData=True
Encroach Param= -1, 0, 0, 0
BEGIN DESCRIPTION:
Multiple Run
END DESCRIPTION:

--- UNT 1006 IN LATR.f01 (steady flow) ---

Flow Title=Multiple
Number of Profiles=7
Profile Names=10-year,25-year,50-year,1pct_min,100-year,1pct_plu,500-year
River Rch & RM= UNT 1006 IN LATR,Reach-1,6221
     701     996    1247    1143    1546    2091    2386
River Rch & RM= UNT 1006 IN LATR,Reach-1,5573
     944    1367    1734    1609    2177    2944    3441
Boundary for River Rch & Prof#=UNT 1006 IN LATR,Reach-1,1
Up Type=0
Dn Type=3
Dn Slope=0.005
Boundary for River Rch & Prof#=UNT 1006 IN LATR,Reach-1,2
Up Type=0
Dn Type=3
Dn Slope=0.005
Boundary for River Rch & Prof#=UNT 1006 IN LATR,Reach-1,3
Up Type=0
Dn Type=3
Dn Slope=0.005
Boundary for River Rch & Prof#=UNT 1006 IN LATR,Reach-1,4
Up Type=0
Dn Type=3
Dn Slope=0.005
Boundary for River Rch & Prof#=UNT 1006 IN LATR,Reach-1,5
Up Type=0
Dn Type=3
Dn Slope=0.005
Boundary for River Rch & Prof#=UNT 1006 IN LATR,Reach-1,6
Up Type=0
Dn Type=3
Dn Slope=0.005
Boundary for River Rch & Prof#=UNT 1006 IN LATR,Reach-1,7
Up Type=0
Dn Type=3
Dn Slope=0.005

--- UNT 1006 IN LATR.g01 (geometry) ---

Geom Title=Existing Conditions

River Reach=UNT 1006 IN LATR,Reach-1
Reach XY= 30
      2891661.83     10081274.59      2891862.41     10081306.26
      2891967.43     10081356.34      2892190.71     10081550.54
      2892257.77     10081584.13      2892402.14     10081726.06
      2892609.98     10081859.98      2892812.64     10081885.72
      2892988.74     10081932.19      2893258.44     10081889.54
      2893562.59     10081945.22      2893602.82     10081991.18
      2893700.69     10082212.83      2893789.61     10082271.38
      2893847.03     10082279.78      2894058.94     10082194.80
      2894503.16     10082182.94      2894697.39     10082160.26
      2894984.04     10082086.50      2895048.77     10082094.94
      2895537.42     10082226.71      2895599.53     10082269.54
      2895696.68     10082267.67      2895800.39     10082328.09
      2895875.02     10082337.56      2895939.47     10082391.11
      2896324.23     10082373.79      2896482.88     10082415.34
      2897069.59     10082821.12      2897274.87     10082887.60

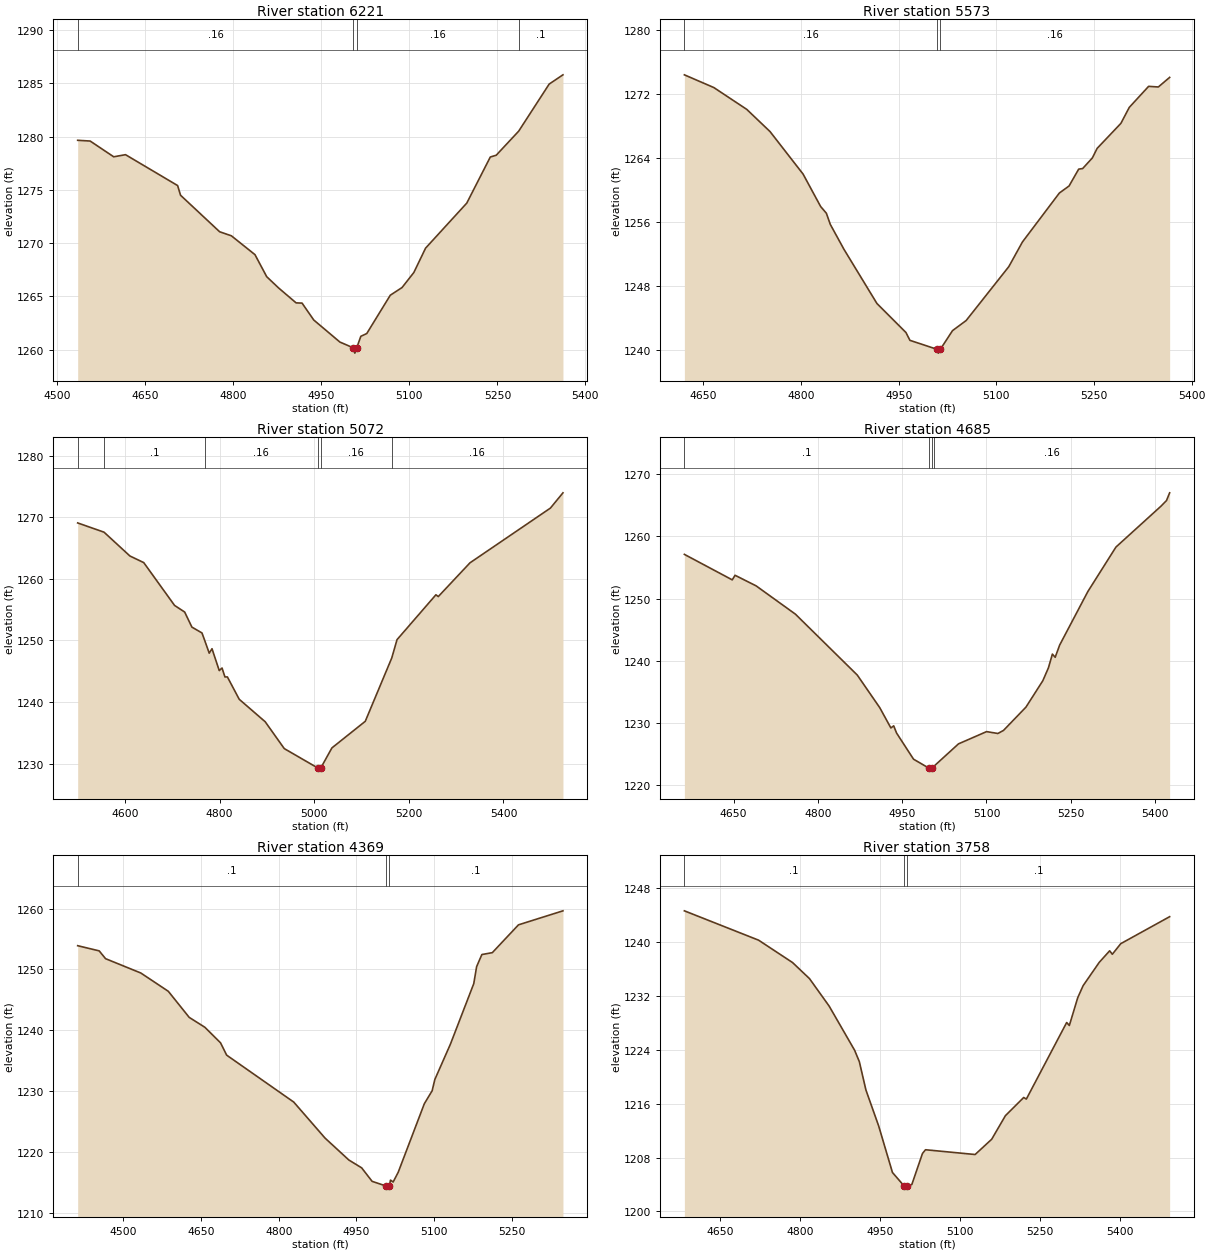
Type RM Length L Ch R = 1,6221,648,648,648
BEGIN DESCRIPTION:
UNT 1006 IN LATR 13.0
END DESCRIPTION:
XS GIS Cut Line= 2
      2891700.69     10081744.97      2891761.45     10080920.30
#Sta/Elev= 30
  4534.8 1279.66  4556.1 1279.59  4596.2 1278.11  4616.3 1278.31  4705.1 1275.41
  4710.1 1274.50  4776.7 1271.07  4796.7 1270.69  4836.9 1268.92  4856.9 1266.85
  4877.0 1265.80  4907.0 1264.39  4917.1 1264.37  4937.1 1262.78  4981.6 1260.71
  5004.3 1260.17  5007.1 1259.67  5010.3 1260.17  5017.3 1261.25  5027.4 1261.51
  5067.5 1265.11  5087.5 1265.83  5107.6 1267.24  5127.6 1269.53  5197.8 1273.76
  5237.9 1278.09  5248.0 1278.26  5286.3 1280.52  5338.2 1284.94  5361.7 1285.81
#Mann=4,-1,0
  4534.8    0.16       0  5004.3    0.07       0  5010.3    0.16       0
  5286.3     0.1       0
Bank Sta=5004.3,5010.3
Exp/Cntr=0.3,0.1

Type RM Length L Ch R = 1,5573,501,501,501
BEGIN DESCRIPTION:
UNT 1006 IN LATR 12.0
END DESCRIPTION:
XS GIS Cut Line= 2
      2892056.57     10081914.26      2892481.93     10081302.26
#Sta/Elev= 30
  4620.9 1274.41  4666.1 1272.82  4716.7 1270.09  4752.5 1267.31  4803.2 1262.00
  4830.2 1257.94  4839.0 1257.10  4845.0 1255.71  4866.0 1252.59  4916.6 1245.82
  4961.2 1242.19  4967.3 1241.21  5008.2 1240.11  5011.0 1239.61  5014.2 1240.11
  5032.7 1242.42  5053.7 1243.69  5119.2 1250.43  5140.1 1253.51  5196.8 1259.63
  5211.7 1260.51  5226.5 1262.62  5232.6 1262.69  5247.5 1264.02  5254.8 1265.21
  5291.3 1268.34  5304.2 1270.34  5333.9 1272.97  5348.8 1272.89  5366.2 1274.09
#Mann=3,-1,0
  4620.9    0.16       0  5008.2    0.07       0  5014.2    0.16       0
Bank Sta=5008.2,5014.2
Exp/Cntr=0.3,0.1

Type RM Length L Ch R = 1,5072,387,387,387
BEGIN DESCRIPTION:
UNT 1006 IN LATR 11.0
END DESCRIPTION:
XS GIS Cut Line= 4
      2892494.94     10082322.24      2892659.89     10082057.46
      2892716.31     10081588.71      2892716.31     10081347.20
#Sta/Elev= 30
  4500.1 1269.09  4555.8 1267.59  4610.5 1263.72  4639.7 1262.65  4704.9 1255.69
  4726.2 1254.62  4741.5 1252.17  4762.8 1251.22  4768.8 1249.96  4778.1 1247.94
  4784.0 1248.66  4799.3 1245.11  4805.2 1245.53  4811.3 1244.08  4816.5 1244.08
  4841.5 1240.45  4896.4 1236.80  4936.7 1232.44  5007.8 1229.28  5010.5 1228.78
  5013.8 1229.28  5037.4 1232.55  5107.9 1236.87  5163.9 1247.16  5175.0 1250.13
  5257.2 1257.42  5262.2 1257.13  5329.2 1262.61  5499.2 1271.50  5525.7 1273.98
#Mann=6,-1,0
  4500.1    0.16       0  4555.8     0.1       0  4768.8    0.16       0
  5007.8    0.07       0  5013.8    0.16       0  5163.9    0.16       0
Bank Sta=5007.8,5013.8
Exp/Cntr=0.3,0.1

Type RM Length L Ch R = 1,4685,316,316,316
BEGIN DESCRIPTION:
UNT 1006 IN LATR 10.0
END DESCRIPTION:
XS GIS Cut Line= 2
      2893076.56     10082361.25      2893046.20     10081498.18
#Sta/Elev= 30
  4562.4 1257.11  4647.6 1253.01  4652.6 1253.75  4690.0 1252.05  4760.0 1247.50
  4870.1 1237.71  4910.1 1232.47  4929.9 1229.21  4934.9 1229.55  4940.1 1228.38
  4970.2 1224.19  4997.2 1222.77  4999.9 1222.27  5003.2 1222.77  5006.2 1223.03
  5050.2 1226.65  5100.2 1228.62  5120.3 1228.32  5130.3 1228.81  5170.3 1232.56
  5200.3 1236.80  5210.3 1238.88  5217.3 1241.08  5222.3 1240.57  5230.3 1242.54
  5280.4 1251.13  5330.4 1258.28  5410.4 1264.84  5420.4 1265.76  5426.0 1267.00
#Mann=4,-1,0
  4562.4     0.1       0  4997.2    0.07       0  5003.2     0.1       0
  5006.2    0.16       0
Bank Sta=4997.2,5003.2
Exp/Cntr=0.3,0.1

Type RM Length L Ch R = 1,4369,611,611,611
BEGIN DESCRIPTION:
UNT 1006 IN LATR 9.0
END DESCRIPTION:
XS GIS Cut Line= 2
      2893297.92     10082487.11      2893415.07     10081558.57
#Sta/Elev= 30
  4412.3 1253.90  4453.8 1253.05  4466.1 1251.77  4534.1 1249.42  4587.1 1246.42
  4627.4 1242.14  4657.6 1240.52  4687.8 1237.97  4699.6 1235.95  4829.0 1228.25
  4889.4 1222.34  4935.4 1218.74  4960.0 1217.46  4980.1 1215.25  5007.4 1214.47
  5010.1 1213.97  5013.4 1214.47  5015.6 1215.45  5020.7 1215.14  5030.5 1216.74
  5080.9 1227.99  5095.9 1230.10  5101.1 1231.95  5131.3 1237.78  5176.2 1247.68
  5181.7 1250.46  5191.8 1252.45  5212.0 1252.76  5262.4 1257.32  5348.2 1259.62
#Mann=3,-1,0
  4412.3     0.1       0  5007.4    0.07       0  5013.4     0.1       0
Bank Sta=5007.4,5013.4
Exp/Cntr=0.3,0.1

Type RM Length L Ch R = 1,3758,422,422,422
BEGIN DESCRIPTION:
UNT 1006 IN LATR 8.0
END DESCRIPTION:
XS GIS Cut Line= 3
      2893653.81     10082665.10      2893862.15     10082070.48
      2893896.87     10081792.70
#Sta/Elev= 30
  4583.3 1244.66  4722.5 1240.30  4786.1 1236.98  4817.9 1234.59  4854.7 1230.52
  4902.6 1223.94  4911.4 1222.25  4923.8 1218.03  4947.7 1212.69  4973.5 1205.79
  4995.0 1203.82  4997.7 1203.32  5001.0 1203.82  5009.8 1204.00  5029.8 1208.62
  5035.5 1209.17  5128.5 1208.46  5159.6 1210.73  5185.3 1214.23  5219.6 1216.93
  5224.6 1216.70  5300.2 1228.07  5305.2 1227.63  5320.9 1231.75  5331.0 1233.54
  5361.3 1237.01  5380.8 1238.72  5385.8 1238.21  5401.6 1239.78  5493.3 1243.79
#Mann=3,-1,0
  4583.3     0.1       0  4995.0    0.07       0  5001.0     0.1       0
Bank Sta=4995,5001
Exp/Cntr=0.3,0.1

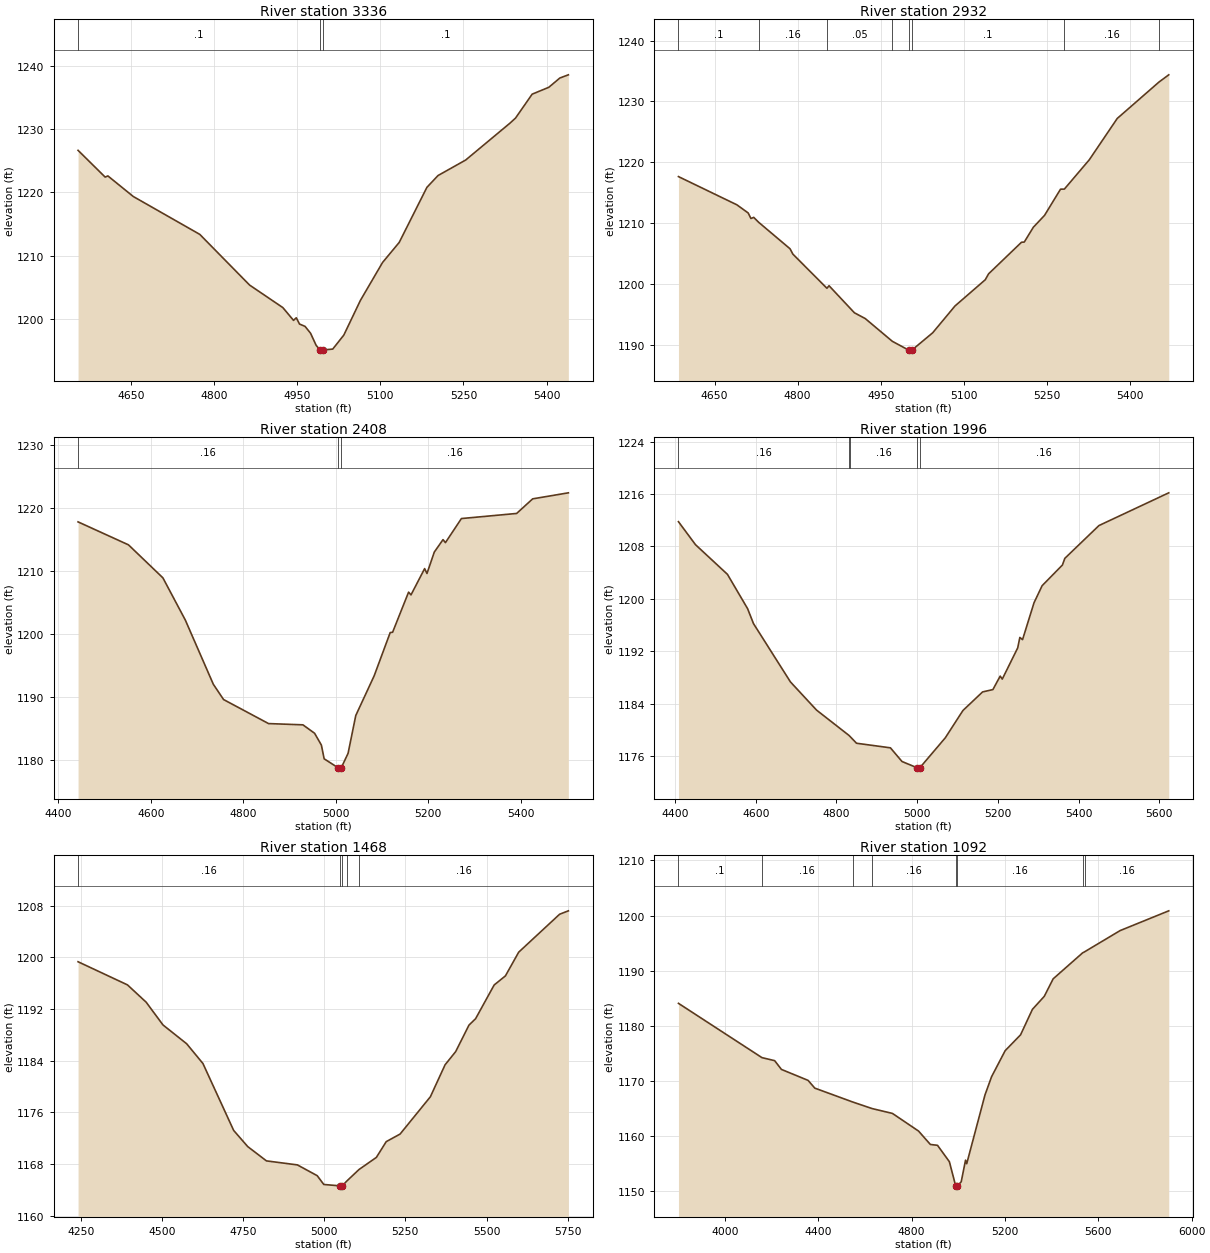
Type RM Length L Ch R = 1,3336,404,404,404
BEGIN DESCRIPTION:
UNT 1006 IN LATR 7.0
END DESCRIPTION:
XS GIS Cut Line= 2
      2894205.03     10082643.42      2894179.00     10081758.40
#Sta/Elev= 30
  4554.0 1226.66  4602.9 1222.43  4607.9 1222.61  4653.7 1219.36  4773.8 1213.37
  4863.8 1205.35  4923.8 1201.79  4943.1 1199.77  4948.1 1200.18  4953.9 1199.19
  4963.9 1198.82  4973.9 1197.73  4983.9 1195.83  4990.9 1195.09  4993.6 1194.59
  4996.9 1195.09  5013.9 1195.23  5033.9 1197.44  5063.9 1202.93  5103.9 1208.93
  5133.9 1212.09  5184.0 1220.81  5204.0 1222.67  5254.0 1225.13  5334.0 1230.96
  5344.0 1231.76  5374.0 1235.54  5404.1 1236.63  5424.1 1238.10  5439.4 1238.60
#Mann=3,-1,0
  4554.0     0.1       0  4990.9    0.07       0  4996.9     0.1       0
Bank Sta=4990.9,4996.9
Exp/Cntr=0.3,0.1

Type RM Length L Ch R = 1,2932,524,524,524
BEGIN DESCRIPTION:
UNT 1006 IN LATR 6.0
END DESCRIPTION:
XS GIS Cut Line= 2
      2894652.08     10082578.31      2894526.22     10081701.60
#Sta/Elev= 30
  4584.8 1217.63  4690.5 1212.98  4710.7 1211.65  4715.7 1210.74  4720.8 1210.92
  4729.6 1210.12  4786.3 1205.76  4791.5 1204.88  4853.0 1199.26  4856.8 1199.68
  4902.6 1195.23  4922.3 1194.27  4971.2 1190.53  5000.6 1189.09  5003.4 1188.59
  5006.6 1189.09  5044.0 1191.93  5084.4 1196.35  5139.0 1200.66  5145.1 1201.64
  5204.5 1206.83  5209.5 1206.86  5225.9 1209.30  5246.1 1211.25  5275.0 1215.56
  5281.9 1215.57  5326.9 1220.39  5377.4 1227.19  5452.8 1233.18  5470.5 1234.37
#Mann=8,-1,0
  4584.8     0.1       0  4729.6    0.16       0  4853.0    0.05       0
  4971.2     0.1       0  5000.6    0.07       0  5006.6     0.1       0
  5281.9    0.16       0  5452.8     0.1       0
Bank Sta=5000.6,5006.6
Exp/Cntr=0.3,0.1

Type RM Length L Ch R = 1,2408,412,412,412
BEGIN DESCRIPTION:
UNT 1006 IN LATR 5.0
END DESCRIPTION:
XS GIS Cut Line= 2
      2894955.91     10082647.69      2895233.58     10081623.78
#Sta/Elev= 30
  4442.5 1217.83  4551.6 1214.18  4626.1 1208.93  4674.6 1202.22  4735.2 1192.01
  4757.4 1189.58  4854.7 1185.76  4929.1 1185.56  4954.3 1184.22  4969.0 1182.34
  4975.0 1180.16  5005.8 1178.70  5008.5 1178.20  5011.8 1178.70  5026.8 1181.04
  5043.4 1187.04  5083.3 1193.37  5117.9 1200.23  5123.1 1200.28  5157.7 1206.66
  5162.9 1206.22  5192.4 1210.40  5197.5 1209.63  5213.3 1213.03  5232.2 1215.01
  5237.4 1214.53  5272.0 1218.36  5391.5 1219.17  5426.1 1221.49  5503.4 1222.45
#Mann=3,-1,0
  4442.5    0.16       0  5005.8    0.07       0  5011.8    0.16       0
Bank Sta=5005.8,5011.8
Exp/Cntr=0.3,0.1

Type RM Length L Ch R = 1,1996,528,528,528
BEGIN DESCRIPTION:
UNT 1006 IN LATR 4.0
END DESCRIPTION:
XS GIS Cut Line= 4
      2895220.66     10082725.85      2895455.03     10082413.36
      2895554.85     10081961.97      2895515.79     10081601.69
#Sta/Elev= 30
  4408.4 1211.78  4450.6 1208.27  4529.8 1203.74  4579.8 1198.49  4594.4 1196.21
  4686.0 1187.30  4750.6 1183.00  4831.2 1179.12  4832.8 1179.02  4849.8 1177.93
  4933.8 1177.23  4962.5 1175.14  5000.5 1174.17  5003.2 1173.67  5006.5 1174.17
  5069.8 1178.76  5113.5 1182.93  5162.2 1185.77  5187.8 1186.13  5205.9 1188.19
  5211.0 1187.73  5249.3 1192.50  5254.6 1194.10  5261.3 1193.76  5289.7 1199.39
  5309.8 1202.00  5360.1 1205.16  5366.1 1206.18  5450.7 1211.19  5623.7 1216.19
#Mann=5,-1,0
  4408.4    0.16       0  4831.2     0.1       0  4832.8    0.16       0
  5000.5    0.07       0  5006.5    0.16       0
Bank Sta=5000.5,5006.5
Exp/Cntr=0.3,0.1

Type RM Length L Ch R = 1,1468,376,376,376
BEGIN DESCRIPTION:
UNT 1006 IN LATR 3.0
END DESCRIPTION:
XS GIS Cut Line= 4
      2895433.30     10082869.11      2895941.14     10082547.91
      2896001.90     10082161.63      2895897.74     10081653.82
#Sta/Elev= 30
  4241.8 1199.31  4394.0 1195.73  4451.6 1193.05  4503.4 1189.53  4576.3 1186.62
  4626.5 1183.56  4721.2 1173.20  4764.5 1170.70  4822.1 1168.49  4917.4 1167.87
  4978.5 1166.20  4998.8 1164.84  5049.6 1164.62  5052.3 1164.12  5055.6 1164.62
  5069.0 1165.34  5107.1 1167.15  5160.7 1169.03  5191.1 1171.47  5233.7 1172.64
  5327.0 1178.41  5372.3 1183.36  5405.1 1185.41  5445.9 1189.50  5466.4 1190.50
  5523.5 1195.71  5558.2 1197.12  5599.1 1200.79  5725.1 1206.66  5752.1 1207.19
#Mann=5,-1,0
  4241.8    0.16       0  5049.6    0.07       0  5055.6    0.16       0
  5069.0    0.05       0  5107.1    0.16       0
Bank Sta=5049.6,5055.6
Exp/Cntr=0.3,0.1

Type RM Length L Ch R = 1,1092,541,541,541
BEGIN DESCRIPTION:
UNT 1006 IN LATR 2.0
END DESCRIPTION:
XS GIS Cut Line= 4
      2895585.26     10083229.31      2896279.68     10082691.14
      2896401.21     10082027.08      2896323.28     10081485.90
#Sta/Elev= 30
  3801.5 1184.05  4159.2 1174.19  4213.6 1173.64  4242.6 1172.05  4356.7 1170.06
  4385.7 1168.65  4548.1 1166.13  4631.0 1164.94  4718.1 1164.06  4829.9 1160.86
  4880.7 1158.42  4911.2 1158.27  4962.1 1155.29  4989.6 1150.81  4992.3 1150.31
  4995.6 1150.81  5012.9 1151.66  5031.3 1155.57  5036.3 1154.92  5114.6 1167.41
  5142.7 1170.71  5201.0 1175.45  5267.0 1178.33  5317.9 1182.96  5368.6 1185.32
  5406.7 1188.50  5532.7 1193.21  5541.0 1193.40  5693.5 1197.26  5901.9 1200.85
#Mann=8,-1,0
  3801.5     0.1       0  4159.2    0.16       0  4548.1     0.1       0
  4631.0    0.16       0  4989.6    0.07       0  4995.6    0.16       0
  5532.7     0.1       0  5541.0    0.16       0
Bank Sta=4989.6,4995.6
Exp/Cntr=0.3,0.1

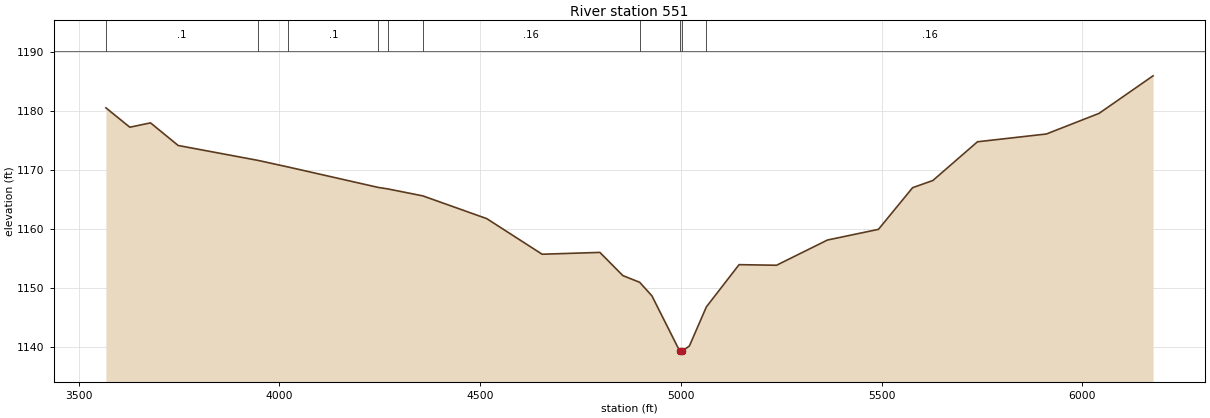
Type RM Length L Ch R = 1,551,0,0,0
BEGIN DESCRIPTION:
UNT 1006 IN LATR 1.0
END DESCRIPTION:
XS GIS Cut Line= 4
      2895619.94     10083363.89      2896622.56     10082903.81
      2896969.79     10082374.30      2896848.25     10081510.55
#Sta/Elev= 30
  3567.6 1180.58  3627.2 1177.29  3678.7 1178.03  3747.7 1174.19  3946.7 1171.66
  4021.6 1170.54  4246.4 1167.07  4269.2 1166.83  4357.1 1165.64  4516.4 1161.78
  4654.3 1155.74  4798.2 1156.05  4855.5 1152.11  4897.3 1150.98  4927.8 1148.68
  4997.2 1139.29  4999.9 1138.79  5003.2 1139.29  5021.2 1140.18  5063.5 1146.81
  5144.9 1153.97  5238.3 1153.87  5365.1 1158.15  5492.1 1159.96  5577.2 1167.03
  5627.7 1168.25  5738.8 1174.82  5910.4 1176.14  6041.7 1179.64  6176.2 1186.01
#Mann=10,-1,0
  3567.6     0.1       0  3946.7    0.16       0  4021.6     0.1       0
  4246.4    0.16       0  4269.2     0.1       0  4357.1    0.16       0
  4897.3     0.1       0  4997.2    0.07       0  5003.2     0.1       0
  5063.5    0.16       0
Bank Sta=4997.2,5003.2
Exp/Cntr=0.3,0.1

Chan Stop Cuts=-1