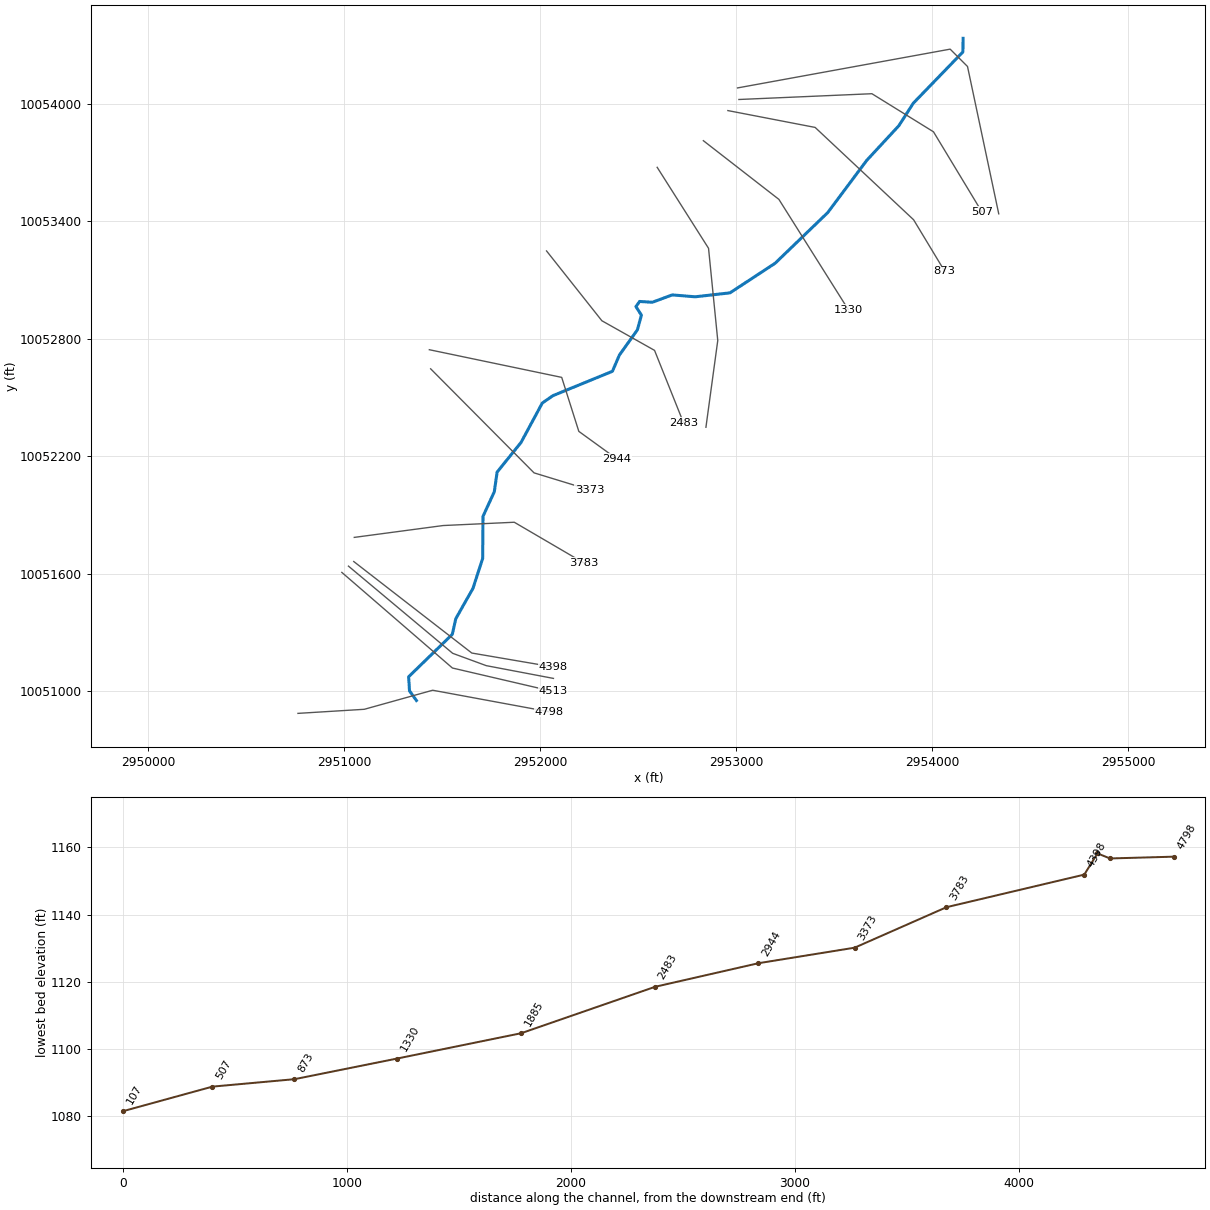
--- UNT 1008 IN LATR.prj (project) ---

Proj Title=UNT 1008 IN LATR Base Level Engineering
Current Plan=p01
Default Exp/Contr=0.3,0.1
English Units
Geom File=g01
Flow File=f01
Plan File=p01
BEGIN DESCRIPTION:
UNT 1008 IN LATR
END DESCRIPTION:

--- UNT 1008 IN LATR.p01 (plan) ---

Plan Title=Multiple Run
Short Identifier=Multiple
Geom File=g01
Flow File=f01
Subcritical Flow
K Sum by GR= 0
Std Step Tol= 0.01
Critical Tol= 0.01
Num of Std Step Trials= 20
Max Error Tol= 0.3
Flow Tol Ratio= 0.001
Split Flow NTrial= 30
Split Flow Tol= 0.02
Split Flow Ratio= 0.02
Log Output Level= 0
Friction Slope Method= 1
Unsteady Friction Slope Method= 2
Unsteady Bridges Friction Slope Method= 1
Parabolic Critical Depth
Global Vel Dist=  1 , 1 , 1
Global Log Level= 0
CheckData=True
Encroach Param= -1, 0, 0, 0
BEGIN DESCRIPTION:
Multiple Run
END DESCRIPTION:

--- UNT 1008 IN LATR.f01 (steady flow) ---

Flow Title=Multiple
Program Version=4.10
Number of Profiles= 7
Profile Names=10-year,25-year,50-year,1pct_min,100-year,1pct_plu,500-year
River Rch & RM=UNT 1008 IN LATR,Reach-1         ,4798
     886    1279    1620    1502    2031    2747    3203
River Rch & RM=UNT 1008 IN LATR,Reach-1         ,3373
    1121    1637    2088    1949    2636    3565    4215
Boundary for River Rch & Prof#=UNT 1008 IN LATR,Reach-1         , 1
Up Type= 0
Dn Type= 3
Dn Slope=0.018
Boundary for River Rch & Prof#=UNT 1008 IN LATR,Reach-1         , 2
Up Type= 0
Dn Type= 3
Dn Slope=0.018
Boundary for River Rch & Prof#=UNT 1008 IN LATR,Reach-1         , 3
Up Type= 0
Dn Type= 3
Dn Slope=0.018
Boundary for River Rch & Prof#=UNT 1008 IN LATR,Reach-1         , 4
Up Type= 0
Dn Type= 3
Dn Slope=0.018
Boundary for River Rch & Prof#=UNT 1008 IN LATR,Reach-1         , 5
Up Type= 0
Dn Type= 3
Dn Slope=0.018
Boundary for River Rch & Prof#=UNT 1008 IN LATR,Reach-1         , 6
Up Type= 0
Dn Type= 3
Dn Slope=0.018
Boundary for River Rch & Prof#=UNT 1008 IN LATR,Reach-1         , 7
Up Type= 0
Dn Type= 3
Dn Slope=0.018
DSS Import GetInterval= 0
DSS Import GetPeak= 0
DSS Import FillOption= 0

--- UNT 1008 IN LATR.g01 (geometry) ---

Geom Title=Existing Conditions
Program Version=4.10

River Reach=UNT 1008 IN LATR,Reach-1
Reach XY= 30
      2951368.47     10050953.73      2951333.22      10051002.7
      2951328.76     10051074.79      2951551.68     10051291.45
      2951569.18     10051370.82      2951656.87     10051525.56
      2951706.55     10051678.78      2951708.08     10051892.88
      2951765.85     10052018.85      2951780.17     10052118.92
      2951902.83     10052271.35      2952010.85     10052471.79
      2952065.51     10052509.39      2952368.68     10052633.54
      2952404.19     10052716.34       2952495.9     10052844.82
      2952516.57     10052919.85      2952488.61     10052963.67
      2952507.39     10052989.95      2952572.38      10052985.8
      2952673.73     10053023.36      2952790.14     10053013.69
      2952968.47     10053033.73      2953198.69     10053184.68
      2953467.54     10053443.67      2953666.34      10053709.9
      2953830.57     10053887.07      2953903.87     10054001.56
      2954157.12     10054263.28      2954158.07     10054332.59

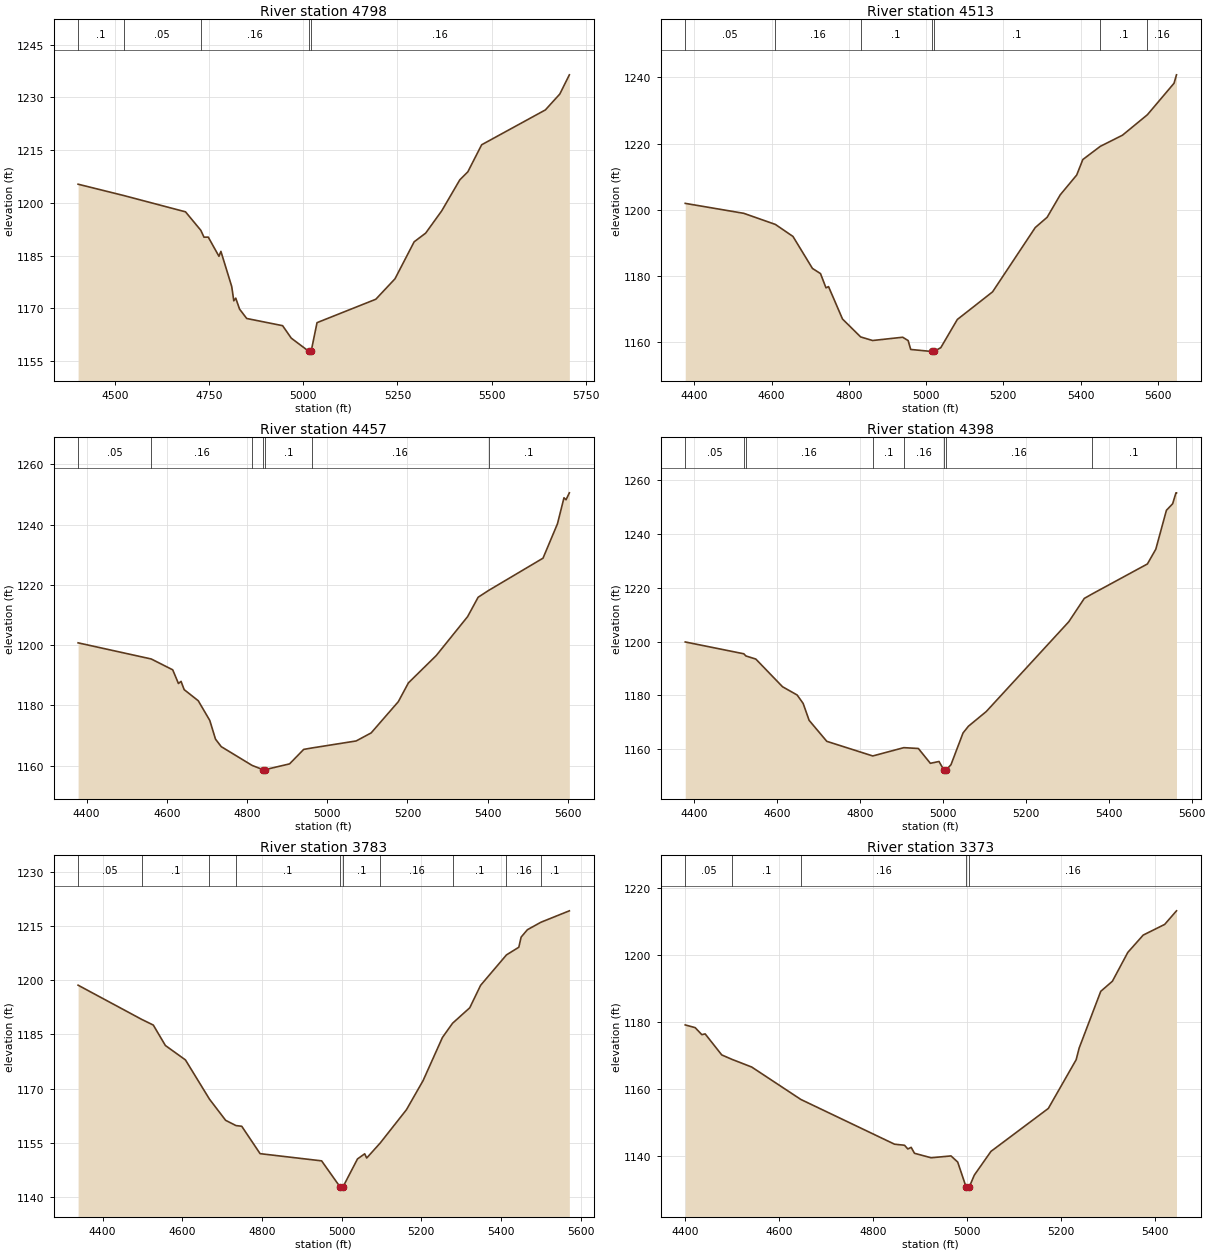
Type RM Length L Ch R = 1 ,4798    ,285,285,285
BEGIN DESCRIPTION:
UNT 1008 IN LATR 10.0
END DESCRIPTION:
XS GIS Cut Line= 4
      2950763.98     10050887.97      2951102.48      10050908.8
      2951451.44     10051006.03      2952043.43     10050896.66
#Sta/Elev= 30
  4402.9  1205.3  4523.9 1202.08  4687.9 1197.44  4728.5 1192.18  4736.9 1190.23
  4748.3 1190.24  4776.6 1184.79  4781.8 1186.19  4810.5 1176.18    4816 1172.12
  4821.2 1172.88  4831.3 1169.76  4850.2  1167.1  4945.5 1165.05  4968.4 1161.51
  5015.2 1157.74  5017.9 1157.24  5021.2 1157.74  5036.8 1165.91  5192.8 1172.57
  5243.6 1178.38  5294.5 1188.91    5325 1191.38  5367.7 1197.73  5415.5 1206.52
  5436.9 1208.82  5473.6 1216.52  5642.6 1226.43  5680.9 1230.95  5706.3 1236.42
#Mann= 5 ,-1 , 0
  4402.9      .1       0  4523.9     .05       0  4728.5     .16       0
  5015.2     .07       0  5021.2     .16       0
Bank Sta=5015.2,5021.2
XS Rating Curve= 0 ,0
Exp/Cntr=0.3,0.1

Type RM Length L Ch R = 1 ,4513    ,56,56,56
BEGIN DESCRIPTION:
Mapping XS e838eb4f
END DESCRIPTION:
XS GIS Cut Line= 3
      2950987.88     10051607.29      2951552.09     10051119.46
      2952064.68     10050999.97
#Sta/Elev= 30
  4376.3 1201.95    4528 1198.94  4609.7 1195.59  4655.3 1191.96  4705.7  1182.3
  4726.6 1180.74  4740.8 1176.43  4747.4  1176.8  4783.6 1167.01  4830.6  1161.6
  4861.5 1160.52  4939.4 1161.51  4953.6  1160.5  4960.2 1157.82  5014.2 1157.21
    5017 1156.71  5020.2 1157.21  5038.1 1158.36  5080.9 1166.87  5172.2 1175.22
  5282.7 1194.64  5313.5 1197.75  5347.5 1204.54  5390.1 1210.52  5405.9 1215.19
  5451.1 1219.17  5508.6 1222.54  5573.1 1228.72  5642.1 1238.23  5648.5 1240.78
#Mann= 7 ,-1 , 0
  4376.3     .05       0  4609.7     .16       0  4830.6      .1       0
  5014.2     .07       0  5020.2      .1       0  5451.1      .1       0
  5573.1     .16       0
Bank Sta=5014.2,5020.2
XS Rating Curve= 0 ,0
Exp/Cntr=0.3,0.1

Type RM Length L Ch R = 1 ,4457    ,59,59,59
BEGIN DESCRIPTION:
Mapping XS 6175445a
END DESCRIPTION:
XS GIS Cut Line= 4
      2951021.67     10051639.36      2951553.38     10051194.46
      2951724.82     10051131.52      2952067.68     10051066.42
#Sta/Elev= 30
  4378.7 1200.77    4561 1195.42  4614.6 1191.82  4628.9 1187.28  4635.4 1187.99
  4643.2 1185.24  4678.3 1181.56    4707 1175.03  4721.3 1168.82  4735.6 1166.33
  4812.5 1160.11  4839.3 1158.71    4842 1158.21  4845.3 1158.71    4906 1160.62
  4941.2 1165.42  4961.2 1165.88    5072 1168.22  5109.4 1170.89  5177.1 1181.25
  5202.3 1187.49  5271.6 1196.54  5349.9 1209.47  5376.1 1215.89  5402.3 1218.16
  5537.9 1228.86  5573.9 1240.26  5590.2  1248.9  5595.3 1248.25  5603.6 1250.54
#Mann= 7 ,-1 , 0
  4378.7     .05       0    4561     .16       0  4812.5      .1       0
  4839.3     .07       0  4845.3      .1       0  4961.2     .16       0
  5402.3      .1       0
Bank Sta=4839.3,4845.3
XS Rating Curve= 0 ,0
Exp/Cntr=0.3,0.1

Type RM Length L Ch R = 1 ,4398    ,615,615,615
BEGIN DESCRIPTION:
UNT 1008 IN LATR 9.0
END DESCRIPTION:
XS GIS Cut Line= 3
      2951048.62     10051662.86      2951651.04     10051195.85
      2952067.66     10051124.68
#Sta/Elev= 30
  4378.6 1199.83  4519.9 1195.44  4524.9 1194.64  4548.9 1193.48  4613.2 1183.22
  4648.5 1180.15    4663 1177.02  4677.4 1170.75    4720 1162.96  4830.9 1157.53
  4905.8 1160.61  4940.9  1160.3  4969.8  1154.8  4990.7 1155.48  5002.2  1152.4
  5004.9  1151.9  5008.2  1152.4  5019.6 1154.29  5048.6 1166.05  5061.7 1168.57
  5104.7 1174.02  5303.8 1207.35  5341.1 1215.99  5360.6 1217.69  5493.3 1228.77
  5513.6 1234.26  5539.2 1248.69  5554.2 1251.11  5562.2 1255.17  5563.5 1255.17
#Mann= 9 ,-1 , 0
  4378.6     .05       0  4519.9      .1       0  4524.9     .16       0
  4830.9      .1       0  4905.8     .16       0  5002.2     .07       0
  5008.2     .16       0  5360.6      .1       0  5562.2     .16       0
Bank Sta=5002.2,5008.2
XS Rating Curve= 0 ,0
Exp/Cntr=0.3,0.1

Type RM Length L Ch R = 1 ,3783    ,410,410,410
BEGIN DESCRIPTION:
UNT 1008 IN LATR 8.0
END DESCRIPTION:
XS GIS Cut Line= 4
       2951051.3     10051785.99      2951504.94     10051846.48
      2951867.84     10051863.28      2952223.78     10051655.09
#Sta/Elev= 30
  4338.3 1198.62  4497.8 1189.17  4527.1 1187.59  4557.4 1181.94  4607.8 1177.95
  4668.1  1167.1  4708.7 1161.24  4734.6 1159.79  4749.1  1159.6  4795.2 1152.02
  4949.6 1150.03  4996.7 1142.71  4999.5 1142.21  5002.7 1142.71  5039.7 1150.56
  5057.8 1151.98  5062.8 1150.81  5096.9 1154.99  5162.5 1164.16  5204.2 1172.19
    5253 1184.17  5278.4  1188.1  5321.5 1192.37  5348.8 1198.59  5413.7    1207
  5444.7 1209.12  5450.5 1211.92  5466.2 1213.96  5500.3 1216.04  5571.6 1219.19
#Mann= 10 ,-1 , 0
  4338.3     .05       0  4497.8      .1       0  4668.1     .05       0
  4734.6      .1       0  4996.7     .07       0  5002.7      .1       0
  5096.9     .16       0  5278.4      .1       0  5413.7     .16       0
  5500.3      .1       0
Bank Sta=4996.7,5002.7
XS Rating Curve= 0 ,0
Exp/Cntr=0.3,0.1

Type RM Length L Ch R = 1 ,3373    ,429,429,429
BEGIN DESCRIPTION:
UNT 1008 IN LATR 7.0
END DESCRIPTION:
XS GIS Cut Line= 3
      2951441.08     10052646.23      2951968.65     10052115.29
      2952252.58     10052028.44
#Sta/Elev= 30
  4400.7 1179.08  4421.8 1178.27    4436 1176.18  4443.1  1176.4  4478.4 1170.14
  4500.5  1168.8  4542.1 1166.54  4646.7 1156.88  4846.1 1143.55  4867.3 1143.24
  4874.4 1142.13  4881.5 1142.61  4888.5 1140.85  4923.9 1139.51  4966.3 1140.06
  4980.5 1138.23  4998.7 1130.67  5001.4 1130.17  5004.7 1130.67  5015.8 1134.33
  5051.2  1141.4  5173.4 1154.21  5232.6 1168.72  5238.9 1172.16  5284.9 1189.08
  5309.7 1192.09  5342.5 1200.68  5375.3 1205.84  5420.9 1209.01  5446.1 1213.06
#Mann= 5 ,-1 , 0
  4400.7     .05       0  4500.5      .1       0  4646.7     .16       0
  4998.7     .07       0  5004.7     .16       0
Bank Sta=4998.7,5004.7
XS Rating Curve= 0 ,0
Exp/Cntr=0.3,0.1

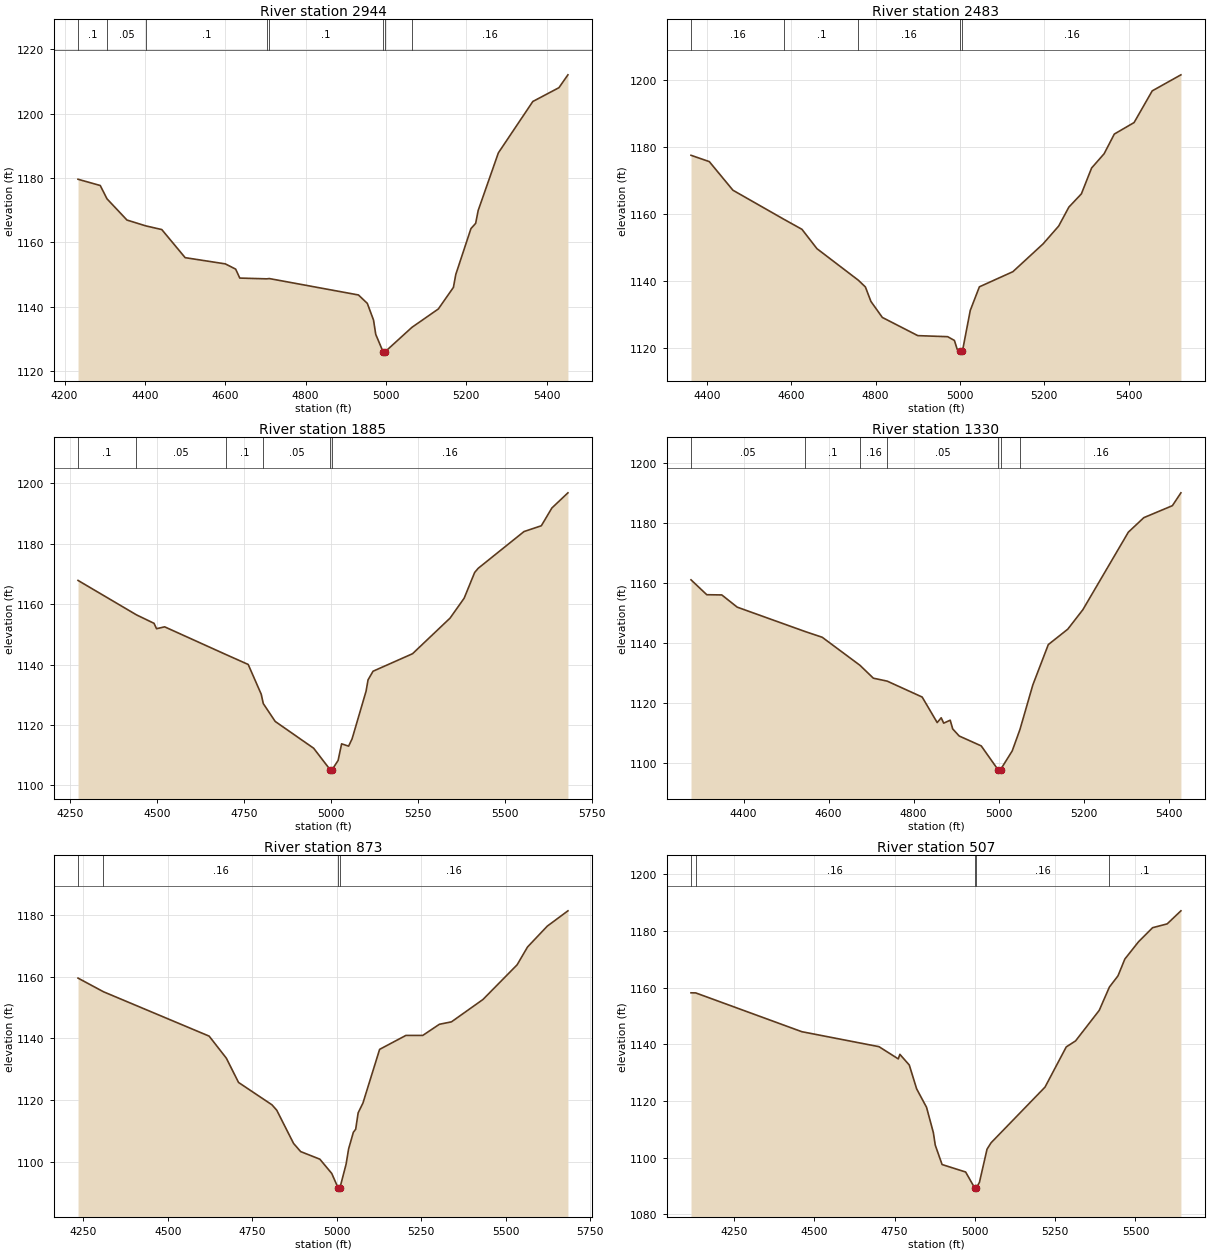
Type RM Length L Ch R = 1 ,2944    ,461,461,461
BEGIN DESCRIPTION:
UNT 1008 IN LATR 6.0
END DESCRIPTION:
XS GIS Cut Line= 4
      2951434.33     10052743.67      2952109.78     10052602.53
      2952197.14     10052326.99      2952392.02     10052185.87
#Sta/Elev= 30
  4233.5 1179.63  4288.8 1177.69  4305.6 1173.55  4355.3 1166.95  4402.3 1165.13
    4442 1163.99  4500.2 1155.25  4600.1 1153.32  4625.9 1151.69  4636.2  1148.9
  4703.2 1148.66  4709.7 1148.75  4931.6 1143.65  4953.7 1141.04  4969.2 1135.84
  4974.7 1131.39  4992.7 1126.06  4995.5 1125.56  4998.7 1126.06  5064.7 1133.57
  5130.6  1139.3  5168.1 1146.01    5174 1150.03  5211.7 1164.28  5223.5 1165.93
  5229.7 1169.91    5280 1187.84  5365.8 1203.82  5430.8 1208.11  5453.2 1212.11
#Mann= 8 ,-1 , 0
  4233.5      .1       0  4305.6     .05       0  4402.3      .1       0
  4703.2     .16       0  4709.7      .1       0  4992.7     .07       0
  4998.7      .1       0  5064.7     .16       0
Bank Sta=4992.7,4998.7
XS Rating Curve= 0 ,0
Exp/Cntr=0.3,0.1

Type RM Length L Ch R = 1 ,2483    ,598,598,598
BEGIN DESCRIPTION:
UNT 1008 IN LATR 5.0
END DESCRIPTION:
XS GIS Cut Line= 4
      2952032.51     10053247.66      2952314.75      10052891.5
      2952583.57     10052740.29      2952731.43     10052370.63
#Sta/Elev= 30
  4362.6 1177.48  4405.9  1175.6    4462 1167.07  4583.4 1158.37  4625.5 1155.43
  4661.1 1149.66  4759.3 1140.25  4775.9 1138.25  4788.9 1133.96    4816 1129.18
  4900.1 1123.76  4970.8 1123.45  4986.8 1122.33  4993.4  1119.7  4999.7 1119.05
  5002.4 1118.55  5005.7 1119.05  5024.4 1131.28    5046  1138.3  5125.4 1142.81
  5197.1 1151.11  5233.9  1156.4  5258.1 1162.05  5287.7 1165.99  5311.9 1173.69
  5341.6 1177.94  5365.8 1183.81  5412.6 1187.23  5455.6 1196.67  5523.6 1201.45
#Mann= 5 ,-1 , 0
  4362.6     .16       0  4583.4      .1       0  4759.3     .16       0
  4999.7     .07       0  5005.7     .16       0
Bank Sta=4999.7,5005.7
XS Rating Curve= 0 ,0
Exp/Cntr=0.3,0.1

Type RM Length L Ch R = 1 ,1885    ,555,555,555
BEGIN DESCRIPTION:
UNT 1008 IN LATR 4.0
END DESCRIPTION:
XS GIS Cut Line= 4
      2952597.03      10053674.4       2952859.1     10053261.13
      2952906.15      10052790.7      2952845.77     10052347.93
#Sta/Elev= 30
  4272.6 1167.81  4440.5 1156.43  4491.2 1153.62  4498.4 1151.84  4521.7 1152.46
  4698.5 1143.27    4762 1140.02  4799.5 1130.17  4805.4 1127.08  4839.7 1121.17
  4950.3 1112.31  4997.5 1105.24  5000.3 1104.74  5003.5 1105.24  5020.6 1108.28
  5030.7 1113.77  5050.8    1113  5060.8 1115.42    5101 1131.16  5106.7 1134.92
  5121.1 1137.78  5234.7 1143.57  5342.7 1155.36  5383.1 1161.93  5413.3 1170.43
  5423.4 1171.81  5555.2 1183.97  5605.1 1185.89  5635.4 1191.76  5681.6 1196.78
#Mann= 6 ,-1 , 0
  4272.6      .1       0  4440.5     .05       0  4698.5      .1       0
  4805.4     .05       0  4997.5     .07       0  5003.5     .16       0
Bank Sta=4997.5,5003.5
XS Rating Curve= 0 ,0
Exp/Cntr=0.3,0.1

Type RM Length L Ch R = 1 ,1330    ,457,457,457
BEGIN DESCRIPTION:
UNT 1008 IN LATR 3.0
END DESCRIPTION:
XS GIS Cut Line= 3
      2952832.66     10053810.31      2953218.11     10053510.81
      2953572.15     10052948.51
#Sta/Elev= 30
  4276.2 1161.04  4313.3 1156.07  4348.6    1156  4384.9 1151.92  4544.5 1143.79
  4584.8 1141.88  4673.7 1132.51  4705.2 1128.21  4737.7 1127.23    4820 1121.92
  4855.4 1113.39  4864.8    1115  4870.7  1113.2    4886 1114.19  4891.9 1111.27
  4907.2 1108.91    4959 1105.61  4998.4 1097.69  5001.1 1097.19  5004.4 1097.69
  5031.9 1103.94  5050.1 1111.09  5080.3 1125.93  5116.8 1139.42  5162.6 1144.57
  5198.1 1151.07  5305.1 1176.95  5341.6  1181.8  5408.7 1185.79  5428.8 1190.08
#Mann= 7 ,-1 , 0
  4276.2     .05       0  4544.5      .1       0  4673.7     .16       0
  4737.7     .05       0  4998.4     .07       0  5004.4     .05       0
  5050.1     .16       0
Bank Sta=4998.4,5004.4
XS Rating Curve= 0 ,0
Exp/Cntr=0.3,0.1

Type RM Length L Ch R = 1 ,873     ,366,366,366
BEGIN DESCRIPTION:
UNT 1008 IN LATR 2.0
END DESCRIPTION:
XS GIS Cut Line= 4
      2952957.73     10053963.93      2953403.01       10053878.
      2953905.61     10053406.64      2954063.94     10053144.49
#Sta/Elev= 30
  4234.8 1159.54    4310 1155.11  4622.6 1140.71  4673.5 1133.54  4709.5 1125.68
  4808.2 1118.44  4822.4 1116.69  4872.2  1105.9  4893.2 1103.25  4949.9 1100.79
  4985.1 1096.16  5003.5 1091.57  5006.3 1091.07  5009.5 1091.57  5027.6 1099.19
  5034.9 1104.09    5049 1109.51  5055.9 1110.51  5063.2 1115.82  5077.4 1119.01
  5126.7 1136.42  5204.4 1140.94  5254.2 1140.94  5303.5 1144.56  5339.2 1145.35
  5432.3  1152.6  5533.2 1163.84  5564.2 1169.65  5622.4 1176.39  5683.6 1181.37
#Mann= 4 ,-1 , 0
  4234.8     .05       0    4310     .16       0  5003.5     .07       0
  5009.5     .16       0
Bank Sta=5003.5,5009.5
XS Rating Curve= 0 ,0
Exp/Cntr=0.3,0.1

Type RM Length L Ch R = 1 ,507     ,400,400,400
BEGIN DESCRIPTION:
Mapping XS 06305996
END DESCRIPTION:
XS GIS Cut Line= 4
      2953013.94      10054020.5      2953692.75     10054050.01
      2954006.98     10053855.57      2954253.12     10053448.23
#Sta/Elev= 30
  4116.6 1158.15  4131.2 1158.12  4461.4 1144.43  4701.7 1139.14  4761.7 1134.83
  4766.7 1136.43    4796 1132.67  4818.9 1124.25  4849.7 1117.74    4871 1108.77
  4876.9 1104.37  4898.1 1097.54  4971.4  1094.9  4999.2 1089.36  5001.9 1088.86
  5005.2 1089.36  5014.4 1091.27    5038 1102.96  5050.6 1105.22  5218.5 1124.87
  5284.6 1139.06  5313.6 1141.18  5387.3 1151.97  5418.8 1160.17  5445.6 1164.14
  5466.9 1170.06  5509.6 1176.18  5553.3 1181.13  5598.8 1182.49  5641.5 1187.09
#Mann= 5 ,-1 , 0
  4116.6     .05       0  4131.2     .16       0  4999.2     .07       0
  5005.2     .16       0  5418.8      .1       0
Bank Sta=4999.2,5005.2
XS Rating Curve= 0 ,0
Exp/Cntr=0.3,0.1

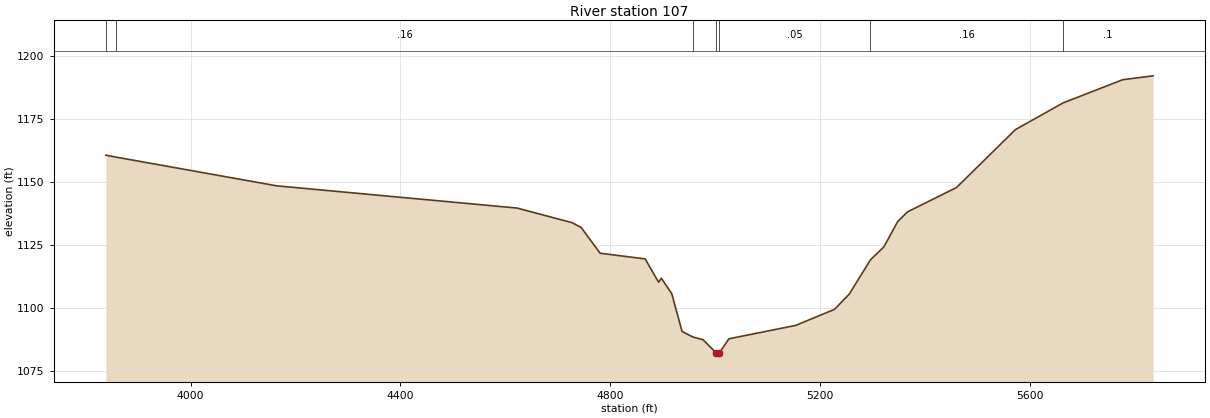
Type RM Length L Ch R = 1 ,107     ,0,0,0
BEGIN DESCRIPTION:
UNT 1008 IN LATR 1.0
END DESCRIPTION:
XS GIS Cut Line= 4
      2953006.98     10054079.52      2954092.05     10054277.44
      2954180.59      10054188.9      2954339.96      10053437.1
#Sta/Elev= 30
  3838.4 1160.64  3857.7 1159.85  4164.2 1148.43  4622.6 1139.59  4727.5 1133.78
  4744.6 1131.88  4780.8 1121.65  4866.6 1119.39  4892.4  1110.1  4897.5 1111.73
  4917.4 1105.55    4937 1090.57  4957.5 1088.36  4976.8 1087.29  5002.1 1082.04
  5004.9 1081.54  5008.1 1082.04  5026.3 1087.62  5153.7 1092.96  5227.7 1099.34
  5255.9 1105.43  5296.2    1119  5321.9 1124.19  5347.9 1134.13  5366.5 1138.04
  5460.3 1147.76  5572.8  1170.8  5663.7 1181.41  5777.2 1190.61  5835.1 1192.16
#Mann= 7 ,-1 , 0
  3838.4     .05       0  3857.7     .16       0  4957.5     .05       0
  5002.1     .07       0  5008.1     .05       0  5296.2     .16       0
  5663.7      .1       0
Bank Sta=5002.1,5008.1
XS Rating Curve= 0 ,0
Exp/Cntr=0.3,0.1

Chan Stop Cuts=-1
Use User Specified Reach Order=0
Composite Channel Slope=5