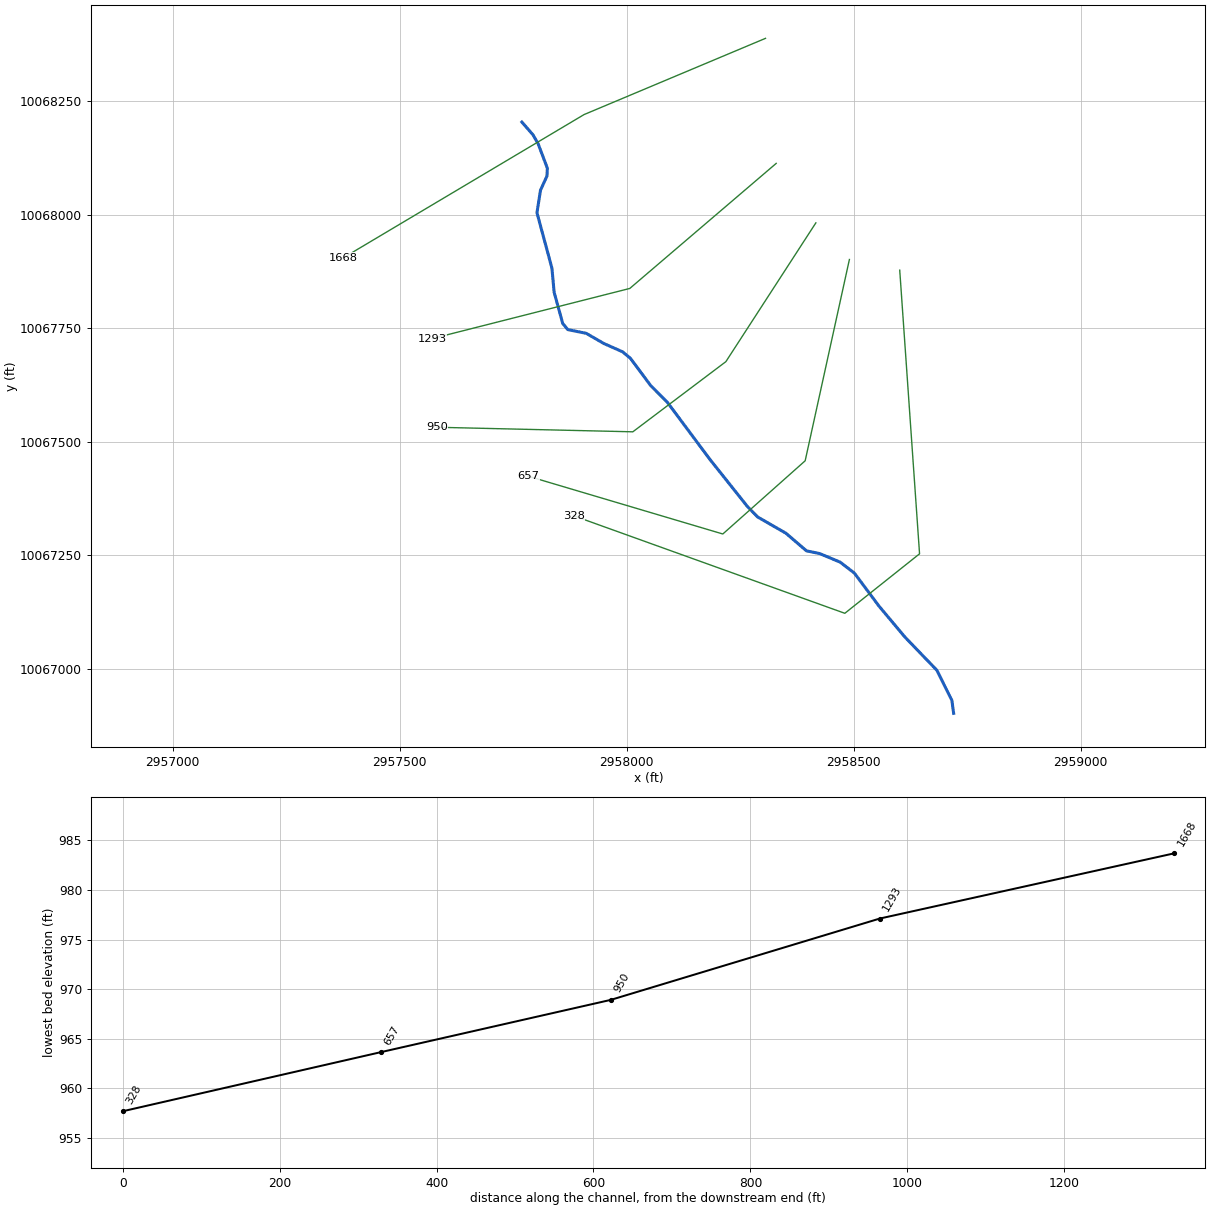
--- UNT 1009 IN LATR.prj (project) ---

Proj Title=UNT 1009 IN LATR Base Level Engineering
Current Plan=p01
Default Exp/Contr=0.3,0.1
English Units
Geom File=g01
Flow File=f01
Plan File=p01
BEGIN DESCRIPTION:
UNT 1009 IN LATR
END DESCRIPTION:

--- UNT 1009 IN LATR.p01 (plan) ---

Plan Title=Multiple Run
Short Identifier=Multiple
Geom File=g01
Flow File=f01
Subcritical Flow
K Sum by GR= 0
Std Step Tol= 0.01
Critical Tol= 0.01
Num of Std Step Trials= 20
Max Error Tol= 0.3
Flow Tol Ratio= 0.001
Split Flow NTrial= 30
Split Flow Tol= 0.02
Split Flow Ratio= 0.02
Log Output Level= 0
Friction Slope Method= 1
Unsteady Friction Slope Method= 2
Unsteady Bridges Friction Slope Method= 1
Parabolic Critical Depth
Global Vel Dist=  1 , 1 , 1
Global Log Level= 0
CheckData=True
Encroach Param= -1, 0, 0, 0
BEGIN DESCRIPTION:
Multiple Run
END DESCRIPTION:

--- UNT 1009 IN LATR.f01 (steady flow) ---

Flow Title=Multiple
Number of Profiles=7
Profile Names=10-year,25-year,50-year,1pct_min,100-year,1pct_plu,500-year
River Rch & RM= UNT 1009 IN LATR,Reach-1,1668
     811    1170    1481    1373    1857    2511    2929
Boundary for River Rch & Prof#=UNT 1009 IN LATR,Reach-1,1
Up Type=0
Dn Type=3
Dn Slope=0.005
Boundary for River Rch & Prof#=UNT 1009 IN LATR,Reach-1,2
Up Type=0
Dn Type=3
Dn Slope=0.005
Boundary for River Rch & Prof#=UNT 1009 IN LATR,Reach-1,3
Up Type=0
Dn Type=3
Dn Slope=0.005
Boundary for River Rch & Prof#=UNT 1009 IN LATR,Reach-1,4
Up Type=0
Dn Type=3
Dn Slope=0.005
Boundary for River Rch & Prof#=UNT 1009 IN LATR,Reach-1,5
Up Type=0
Dn Type=3
Dn Slope=0.005
Boundary for River Rch & Prof#=UNT 1009 IN LATR,Reach-1,6
Up Type=0
Dn Type=3
Dn Slope=0.005
Boundary for River Rch & Prof#=UNT 1009 IN LATR,Reach-1,7
Up Type=0
Dn Type=3
Dn Slope=0.005

--- UNT 1009 IN LATR.g01 (geometry) ---

Geom Title=Existing Conditions

River Reach=UNT 1009 IN LATR,Reach-1
Reach XY= 30
      2957769.18     10068204.33      2957793.55     10068176.38
      2957804.87     10068156.86      2957825.34     10068102.73
      2957824.42     10068085.23      2957810.21     10068054.15
      2957802.45     10068004.46      2957835.41     10067882.47
      2957840.27     10067829.44      2957859.12     10067760.77
      2957870.38     10067747.06      2957911.02     10067738.85
      2957949.62     10067716.52      2957990.96     10067698.19
      2958008.40     10067683.77      2958052.74     10067624.09
      2958089.54     10067587.18      2958183.49     10067461.10
      2958266.10     10067357.30      2958288.60     10067334.28
      2958350.97     10067298.43      2958396.21     10067259.65
      2958425.26     10067253.59      2958470.58     10067234.69
      2958501.75     10067210.63      2958556.28     10067137.55
      2958612.91     10067069.91      2958683.51     10066996.57
      2958716.55     10066930.32      2958720.52     10066901.52

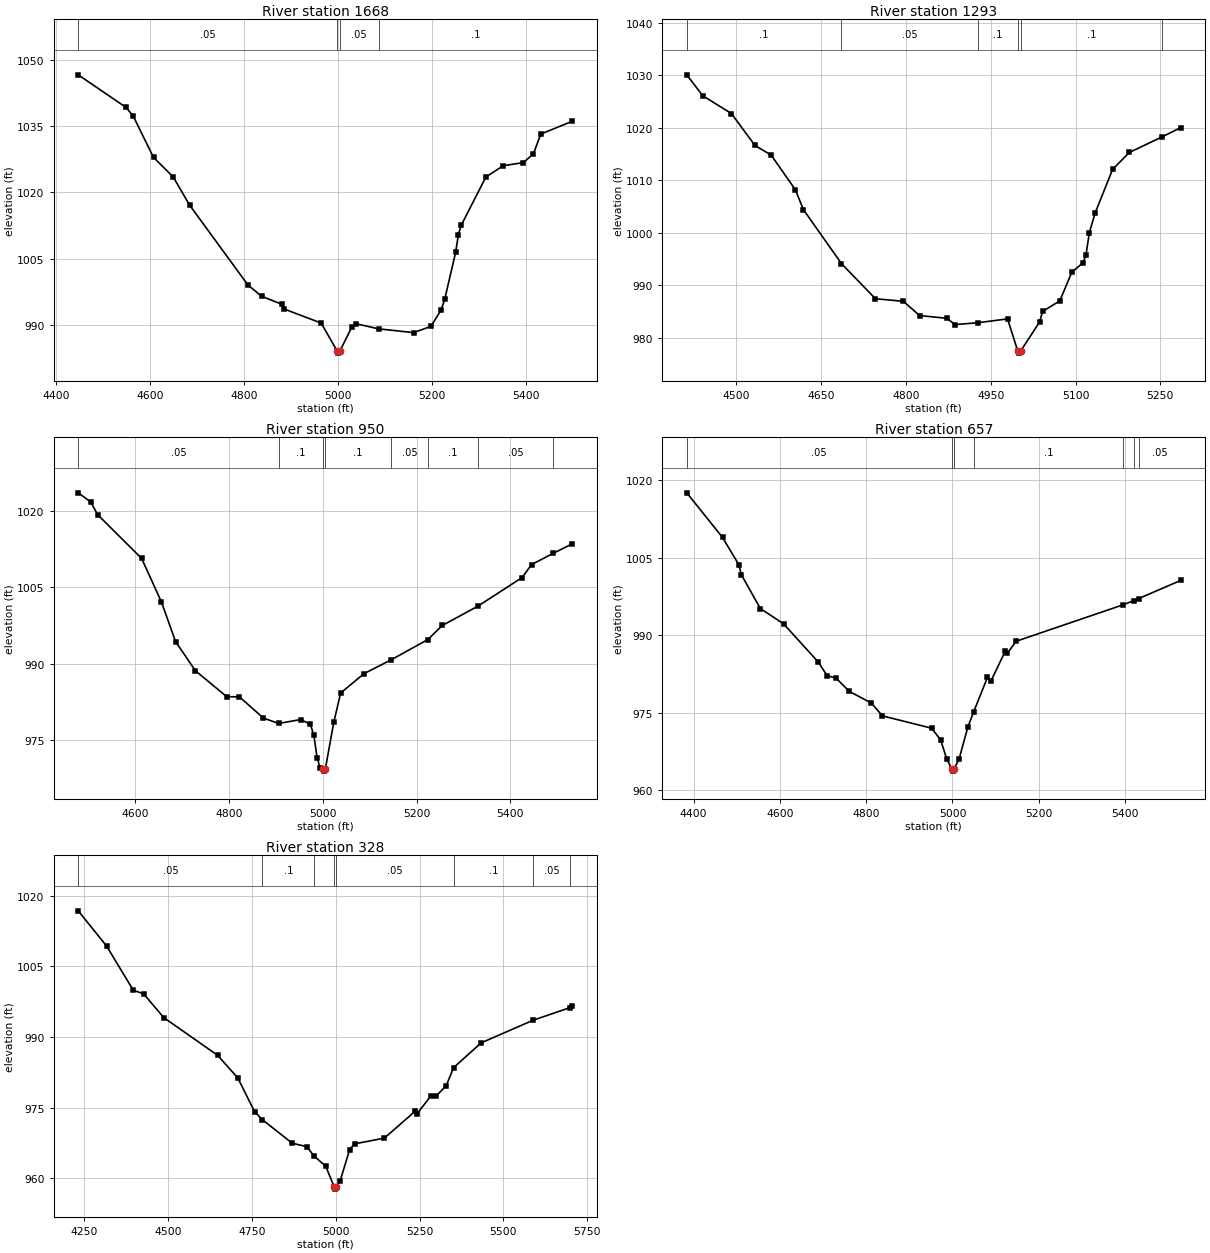
Type RM Length L Ch R = 1,1668,375,375,375
BEGIN DESCRIPTION:
UNT 1009 IN LATR 3.0
END DESCRIPTION:
XS GIS Cut Line= 3
      2958305.99     10068388.81      2957906.15     10068220.81
      2957375.21     10067904.93
#Sta/Elev= 30
  4446.6 1046.60  4548.5 1039.22  4563.2 1037.35  4606.9 1027.93  4649.0 1023.47
  4683.6 1017.15  4807.7  999.10  4836.9  996.53  4880.3  994.71  4883.9  993.69
  4963.7  990.47  4997.7  984.17  5000.5  983.67  5003.7  984.17  5028.9  989.53
  5037.8  990.32  5085.9  989.16  5160.4  988.31  5197.4  989.71  5218.9  993.40
  5226.7  995.80  5250.0 1006.46  5255.9 1010.47  5261.7 1012.53  5314.3 1023.48
  5351.3 1026.05  5394.1 1026.75  5415.6 1028.73  5431.2 1033.20  5498.1 1036.09
#Mann=4,-1,0
  4446.6    0.05       0  4997.7   0.035       0  5003.7    0.05       0
  5085.9     0.1       0
Bank Sta=4997.7,5003.7
Exp/Cntr=0.3,0.1

Type RM Length L Ch R = 1,1293,343,343,343
BEGIN DESCRIPTION:
Mapping XS 034f0d61
END DESCRIPTION:
XS GIS Cut Line= 3
      2958329.53     10068113.27      2958006.95     10067837.74
      2957571.79     10067727.28
#Sta/Elev= 30
  4412.8 1030.12  4441.1 1026.13  4491.7 1022.75  4533.4 1016.66  4561.9 1014.84
  4604.7 1008.24  4619.0 1004.44  4686.2  994.17  4746.3  987.47  4795.7  986.98
  4824.3  984.27  4872.6  983.74  4887.1  982.54  4928.0  982.91  4979.9  983.63
  4997.6  977.61  5000.4  977.11  5003.6  977.61  5036.4  983.02  5041.8  985.06
  5072.2  987.06  5093.4  992.50  5113.2  994.33  5118.4  995.73  5124.4 1000.02
  5134.7 1003.81  5165.6 1012.11  5195.1 1015.33  5252.8 1018.29  5286.0 1020.06
#Mann=6,-1,0
  4412.8     0.1       0  4686.2    0.05       0  4928.0     0.1       0
  4997.6    0.07       0  5003.6     0.1       0  5252.8    0.05       0
Bank Sta=4997.6,5003.6
Exp/Cntr=0.3,0.1

Type RM Length L Ch R = 1,950,293,293,293
BEGIN DESCRIPTION:
Mapping XS 8ea930bf
END DESCRIPTION:
XS GIS Cut Line= 4
      2958416.90     10067982.24      2958218.65     10067676.45
      2958013.67     10067521.88      2957581.84     10067531.92
#Sta/Elev= 30
  4478.7 1023.50  4505.1 1021.73  4520.2 1019.20  4613.8 1010.64  4656.1 1002.09
  4686.3  994.31  4728.6  988.61  4795.1  983.53  4822.5  983.47  4873.6  979.32
  4905.8  978.27  4952.7  979.03  4973.5  978.14  4981.1  975.92  4988.1  971.48
  4994.4  969.56  4999.7  969.42  5002.4  968.92  5005.7  969.42  5023.5  978.48
  5038.1  984.23  5088.0  988.04  5145.7  990.74  5224.0  994.72  5255.1  997.50
  5331.0 1001.28  5425.1 1006.89  5445.2 1009.43  5491.7 1011.64  5531.8 1013.50
#Mann=8,-1,0
  4478.7    0.05       0  4905.8     0.1       0  4999.7    0.07       0
  5005.7     0.1       0  5145.7    0.05       0  5224.0     0.1       0
  5331.0    0.05       0  5491.7     0.1       0
Bank Sta=4999.7,5005.7
Exp/Cntr=0.3,0.1

Type RM Length L Ch R = 1,657,329,329,329
BEGIN DESCRIPTION:
UNT 1009 IN LATR 2.0
END DESCRIPTION:
XS GIS Cut Line= 4
      2958490.82     10067901.55      2958393.38     10067458.04
      2958211.93     10067296.75      2957782.61     10067424.20
#Sta/Elev= 30
  4384.3 1017.52  4467.1 1008.88  4504.9 1003.62  4510.9 1001.66  4554.7  995.13
  4608.7  992.16  4689.2  984.75  4709.7  982.13  4730.2  981.66  4760.9  979.10
  4812.1  976.83  4837.8  974.35  4951.5  971.97  4972.4  969.74  4986.7  966.03
  4997.9  964.16  5000.6  963.66  5003.9  964.16  5015.1  965.94  5036.0  972.28
  5049.3  975.16  5081.2  981.83  5089.1  981.09  5122.3  986.86  5127.5  986.49
  5147.4  988.79  5395.5  995.85  5420.2  996.65  5431.7  997.06  5529.0 1000.57
#Mann=7,-1,0
  4384.3    0.05       0  4997.9   0.035       0  5003.9    0.05       0
  5049.3     0.1       0  5395.5    0.05       0  5420.2     0.1       0
  5431.7    0.05       0
Bank Sta=4997.9,5003.9
Exp/Cntr=0.3,0.1

Type RM Length L Ch R = 1,328,0,0,0
BEGIN DESCRIPTION:
UNT 1009 IN LATR 1.0
END DESCRIPTION:
XS GIS Cut Line= 4
      2958601.71     10067878.07      2958645.39     10067253.06
      2958480.74     10067122.02      2957883.07     10067336.91
#Sta/Elev= 30
  4232.9 1016.78  4317.4 1009.30  4397.1  999.91  4427.7  999.17  4487.9  994.11
  4648.2  986.12  4708.4  981.32  4758.5  974.15  4781.8  972.44  4870.5  967.46
  4913.8  966.73  4935.9  964.73  4970.5  962.56  4995.7  958.21  4998.4  957.71
  5001.7  958.21  5013.1  959.37  5041.9  966.12  5056.3  967.32  5145.1  968.53
  5237.2  974.25  5242.6  973.69  5284.8  977.58  5298.7  977.41  5329.4  979.65
  5351.8  983.51  5433.6  988.75  5588.7  993.56  5698.3  996.23  5705.0  996.57
#Mann=8,-1,0
  4232.9    0.05       0  4781.8     0.1       0  4935.9    0.05       0
  4995.7   0.035       0  5001.7    0.05       0  5351.8     0.1       0
  5588.7    0.05       0  5698.3     0.1       0
Bank Sta=4995.7,5001.7
Exp/Cntr=0.3,0.1

Chan Stop Cuts=-1