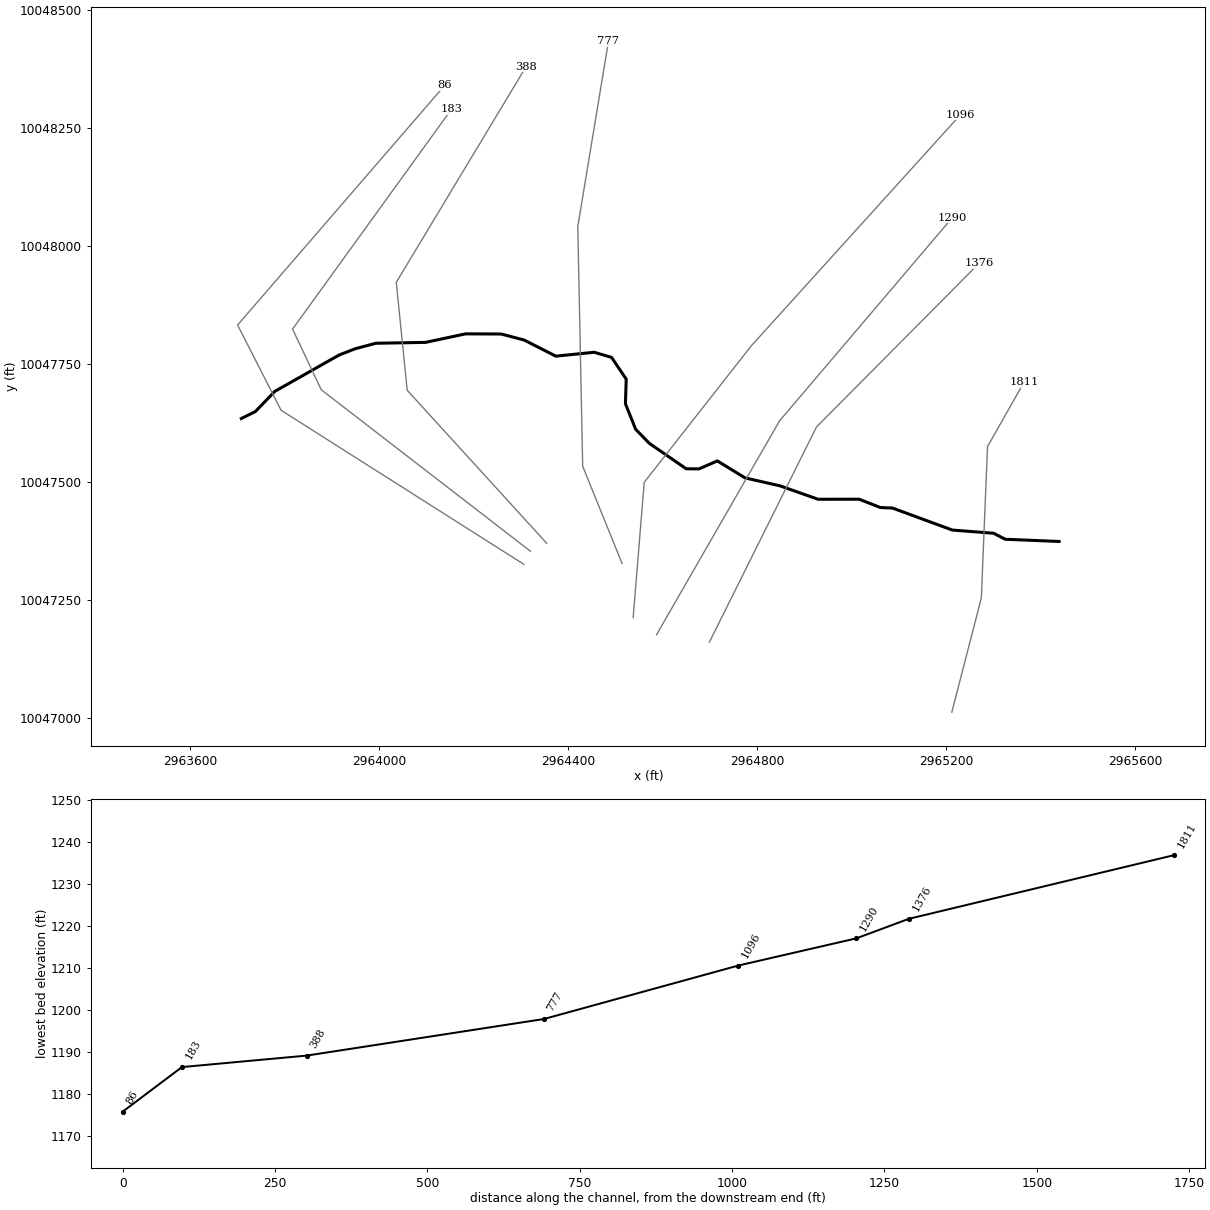
--- UNT 1011 IN LATR.prj (project) ---

Proj Title=UNT 1011 IN LATR Base Level Engineering
Current Plan=p01
Default Exp/Contr=0.3,0.1
English Units
Geom File=g01
Flow File=f01
Plan File=p01
Y Axis Title=Elevation
X Axis Title(PF)=Main Channel Distance
X Axis Title(XS)=Station
BEGIN DESCRIPTION:
UNT 1011 IN LATR
END DESCRIPTION:
DSS Export Rating Curves= 0
DSS Export Rating Curve Sorted= 0
DSS Export Volume Flow Curves= 0
DXF OffsetX= 0
DXF OffsetY= 0
DXF ScaleX= 1
DXF ScaleY= 10

--- UNT 1011 IN LATR.p01 (plan) ---

Plan Title=Multiple Run
Short Identifier=Multiple
Geom File=g01
Flow File=f01
Subcritical Flow
K Sum by GR= 0
Std Step Tol= 0.01
Critical Tol= 0.01
Num of Std Step Trials= 20
Max Error Tol= 0.3
Flow Tol Ratio= 0.001
Split Flow NTrial= 30
Split Flow Tol= 0.02
Split Flow Ratio= 0.02
Log Output Level= 0
Friction Slope Method= 1
Unsteady Friction Slope Method= 2
Unsteady Bridges Friction Slope Method= 1
Parabolic Critical Depth
Global Vel Dist=  1 , 1 , 1
Global Log Level= 0
CheckData=True
Encroach Param= -1, 0, 0, 0
BEGIN DESCRIPTION:
Multiple Run
END DESCRIPTION:

--- UNT 1011 IN LATR.f01 (steady flow) ---

Flow Title=Multiple
Program Version=4.10
Number of Profiles= 7
Profile Names=10-year,25-year,50-year,1pct_min,100-year,1pct_plu,500-year
River Rch & RM=UNT 1011 IN LATR,Reach-1         ,1811
     334     458     561     507     685     927    1021
Boundary for River Rch & Prof#=UNT 1011 IN LATR,Reach-1         , 1
Up Type= 0
Dn Type= 3
Dn Slope=0.111
Boundary for River Rch & Prof#=UNT 1011 IN LATR,Reach-1         , 2
Up Type= 0
Dn Type= 3
Dn Slope=0.111
Boundary for River Rch & Prof#=UNT 1011 IN LATR,Reach-1         , 3
Up Type= 0
Dn Type= 3
Dn Slope=0.111
Boundary for River Rch & Prof#=UNT 1011 IN LATR,Reach-1         , 4
Up Type= 0
Dn Type= 3
Dn Slope=0.111
Boundary for River Rch & Prof#=UNT 1011 IN LATR,Reach-1         , 5
Up Type= 0
Dn Type= 3
Dn Slope=0.111
Boundary for River Rch & Prof#=UNT 1011 IN LATR,Reach-1         , 6
Up Type= 0
Dn Type= 3
Dn Slope=0.111
Boundary for River Rch & Prof#=UNT 1011 IN LATR,Reach-1         , 7
Up Type= 0
Dn Type= 3
Dn Slope=0.111
DSS Import GetInterval= 0
DSS Import GetPeak= 0
DSS Import FillOption= 0

--- UNT 1011 IN LATR.g01 (geometry) ---

Geom Title=Existing Conditions

River Reach=UNT 1011 IN LATR,Reach-1
Reach XY= 30
      2965439.36     10047373.26      2965325.36     10047377.95
      2965300.72     10047390.67      2965213.39     10047397.41
      2965086.77     10047444.03      2965061.08     10047445.16
      2965016.17     10047462.81      2964929.23     10047462.66
      2964848.67     10047491.09      2964774.76     10047507.89
      2964715.98     10047543.89      2964677.11     10047526.98
      2964650.00     10047527.27      2964571.93     10047581.25
      2964543.17     10047610.89      2964521.49     10047664.95
      2964523.13     10047717.13      2964492.17     10047763.17
      2964455.33     10047774.04      2964374.17     10047765.83
      2964306.95     10047800.04      2964258.48     10047812.73
      2964183.10     10047813.06      2964098.32     10047794.99
      2963993.16     10047793.14      2963949.40     10047781.47
      2963915.94     10047768.46      2963779.41     10047691.26
      2963738.33     10047648.52      2963708.47     10047633.73

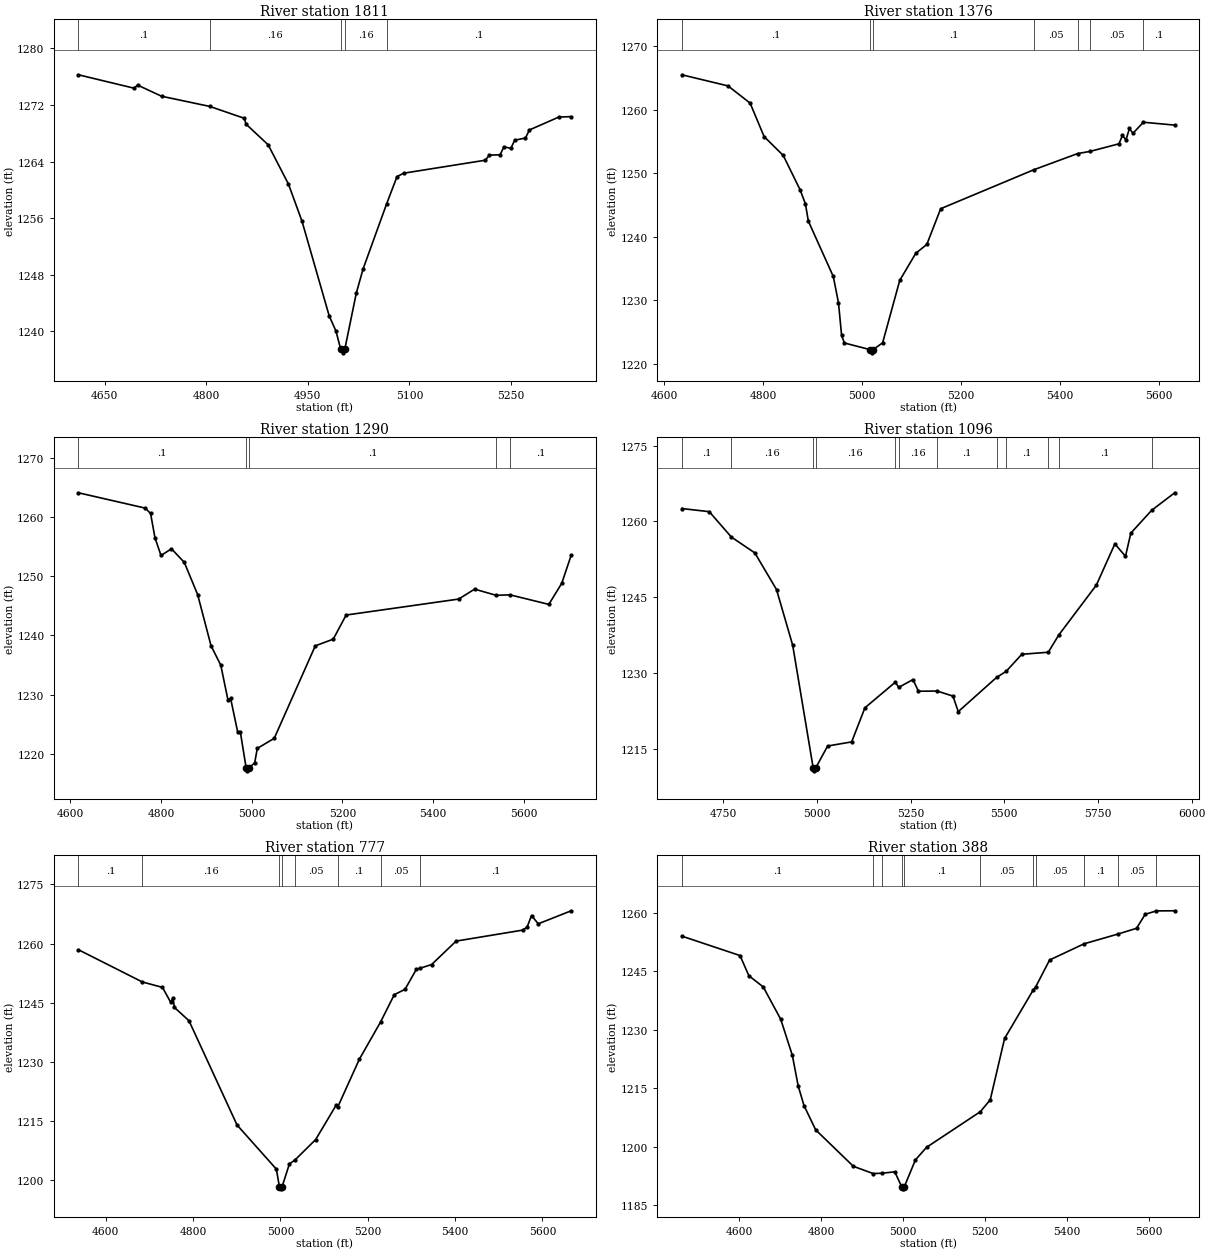
Type RM Length L Ch R = 1,1811,435,435,435
BEGIN DESCRIPTION:
UNT 1011 IN LATR 3.0
END DESCRIPTION:
XS GIS Cut Line= 4
      2965212.29     10047011.59      2965274.79     10047253.79
      2965287.81     10047574.10      2965364.99     10047710.46
#Sta/Elev= 30
  4611.3 1276.28  4693.5 1274.38  4698.7 1274.82  4734.2 1273.24  4805.3 1271.80
  4856.2 1270.12  4858.8 1269.29  4891.4 1266.37  4921.4 1260.80  4941.4 1255.54
  4981.5 1242.15  4991.5 1240.00  4998.5 1237.42  5001.2 1236.92  5004.5 1237.42
  5021.5 1245.37  5031.5 1248.79  5066.3 1258.02  5081.6 1261.87  5091.6 1262.35
  5212.1 1264.19  5217.8 1264.91  5233.7 1264.95  5239.4 1266.08  5249.6 1265.87
  5255.3 1267.02  5271.2 1267.33  5277.0 1268.47  5320.3 1270.29  5338.7 1270.36
#Mann=5,-1,0
  4611.3     0.1       0  4805.3    0.16       0  4998.5    0.07       0
  5004.5    0.16       0  5066.3     0.1       0
Bank Sta=4998.5,5004.5
Exp/Cntr=0.3,0.1

Type RM Length L Ch R = 1,1376,86,86,86
BEGIN DESCRIPTION:
Mapping XS ad5ab2ba
END DESCRIPTION:
XS GIS Cut Line= 3
      2964699.28     10047160.06      2964925.83     10047615.77
      2965269.58     10047962.12
#Sta/Elev= 30
  4635.4 1265.46  4728.8 1263.71  4773.5 1261.00  4801.7 1255.75  4840.5 1252.78
  4874.5 1247.39  4885.2 1245.20  4891.3 1242.45  4941.7 1233.76  4952.2 1229.62
  4958.5 1224.50  4964.1 1223.31  5016.2 1222.26  5019.0 1221.76  5022.2 1222.26
  5041.5 1223.34  5076.1 1233.14  5108.5 1237.40  5130.9 1238.80  5158.9 1244.41
  5347.5 1250.54  5436.0 1253.08  5460.7 1253.41  5519.5 1254.61  5526.6 1255.92
  5533.7 1255.21  5540.7 1257.02  5547.8 1256.26  5568.9 1258.00  5632.3 1257.55
#Mann=7,-1,0
  4635.4     0.1       0  5016.2    0.07       0  5022.2     0.1       0
  5347.5    0.05       0  5436.0     0.1       0  5460.7    0.05       0
  5568.9     0.1       0
Bank Sta=5016.2,5022.2
Exp/Cntr=0.3,0.1

Type RM Length L Ch R = 1,1290,194,194,194
BEGIN DESCRIPTION:
Mapping XS 01f69ebd
END DESCRIPTION:
XS GIS Cut Line= 3
      2964587.28     10047175.65      2964847.71     10047628.79
      2965213.19     10048059.07
#Sta/Elev= 30
  4617.6 1264.12  4765.0 1261.53  4776.9 1260.62  4786.6 1256.50  4799.9 1253.52
  4823.0 1254.65  4851.3 1252.35  4880.7 1246.91  4910.2 1238.27  4931.8 1234.96
  4947.6 1229.08  4953.4 1229.37  4969.2 1223.61  4974.9 1223.68  4987.7 1217.61
  4990.5 1217.11  4993.7 1217.61  5006.5 1218.44  5012.3 1220.90  5049.7 1222.61
  5140.2 1238.24  5179.8 1239.37  5208.3 1243.45  5456.6 1246.15  5491.7 1247.83
  5539.4 1246.78  5569.6 1246.87  5655.4 1245.25  5683.9 1248.81  5704.8 1253.57
#Mann=5,-1,0
  4617.6     0.1       0  4987.7    0.07       0  4993.7     0.1       0
  5539.4    0.05       0  5569.6     0.1       0
Bank Sta=4987.7,4993.7
Exp/Cntr=0.3,0.1

Type RM Length L Ch R = 1,1096,319,319,319
BEGIN DESCRIPTION:
Mapping XS 83b1fc54
END DESCRIPTION:
XS GIS Cut Line= 4
      2964537.81     10047212.09      2964561.25     10047498.58
      2964787.81     10047787.65      2965230.53     10048277.24
#Sta/Elev= 30
  4640.0 1262.53  4713.1 1261.91  4772.0 1256.89  4834.7 1253.75  4892.5 1246.50
  4935.7 1235.46  4990.5 1211.12  4993.3 1210.62  4996.5 1211.12  5028.8 1215.53
  5093.0 1216.35  5128.3 1223.09  5209.5 1228.17  5218.4 1227.14  5256.6 1228.68
  5271.1 1226.38  5321.2 1226.41  5363.2 1225.41  5377.4 1222.34  5479.6 1229.11
  5505.0 1230.30  5547.0 1233.69  5617.5 1234.09  5645.5 1237.50  5745.8 1247.38
  5795.1 1255.53  5823.5 1253.08  5837.7 1257.66  5893.3 1262.18  5954.8 1265.65
#Mann=12,-1,0
  4640.0     0.1       0  4772.0    0.16       0  4990.5    0.07       0
  4996.5    0.16       0  5209.5    0.05       0  5218.4    0.16       0
  5321.2     0.1       0  5479.6    0.05       0  5505.0     0.1       0
  5617.5    0.05       0  5645.5     0.1       0  5893.3    0.05       0
Bank Sta=4990.5,4996.5
Exp/Cntr=0.3,0.1

Type RM Length L Ch R = 1,777,389,389,389
BEGIN DESCRIPTION:
UNT 1011 IN LATR 2.0
END DESCRIPTION:
XS GIS Cut Line= 4
      2964514.36     10047326.74      2964431.04     10047532.44
      2964420.62     10048040.25      2964485.72     10048433.44
#Sta/Elev= 30
  4537.4 1258.45  4683.8 1250.28  4730.0 1248.90  4748.7 1245.14  4754.1 1246.23
  4757.3 1243.82  4790.6 1240.47  4900.7 1214.05  4990.7 1202.87  4997.7 1198.38
  5000.4 1197.88  5003.7 1198.38  5020.7 1204.23  5032.8 1205.13  5080.7 1210.36
  5127.2 1219.00  5131.1 1218.57  5180.7 1230.70  5229.4 1240.16  5260.7 1247.06
  5285.3 1248.41  5311.3 1253.50  5320.0 1253.76  5346.3 1254.70  5402.3 1260.63
  5554.6 1263.41  5564.7 1264.14  5574.9 1267.10  5590.4 1265.01  5665.8 1268.31
#Mann=8,-1,0
  4537.4     0.1       0  4683.8    0.16       0  4997.7    0.07       0
  5003.7    0.16       0  5032.8    0.05       0  5131.1     0.1       0
  5229.4    0.05       0  5320.0     0.1       0
Bank Sta=4997.7,5003.7
Exp/Cntr=0.3,0.1

Type RM Length L Ch R = 1,388,205,205,205
BEGIN DESCRIPTION:
Mapping XS 8975b18d
END DESCRIPTION:
XS GIS Cut Line= 4
      2964354.74     10047369.50      2964059.60     10047693.57
      2964036.45     10047922.16      2964311.16     10048379.05
#Sta/Elev= 30
  4460.6 1254.02  4602.3 1249.04  4623.9 1243.86  4659.0 1240.98  4701.6 1232.68
  4729.9 1223.41  4744.1 1215.58  4758.3 1210.54  4786.7 1204.31  4878.6 1194.95
  4926.8 1193.09  4947.4 1193.17  4979.5 1193.53  4996.6 1189.67  4999.4 1189.17
  5002.6 1189.67  5029.8 1196.59  5057.0 1199.83  5188.1 1208.97  5212.2 1212.02
  5247.2 1227.77  5317.3 1240.26  5323.0 1241.01  5356.9 1247.90  5440.8 1252.05
  5522.9 1254.54  5568.7 1256.03  5590.0 1259.64  5617.3 1260.50  5661.8 1260.53
#Mann=11,-1,0
  4460.6     0.1       0  4926.8    0.05       0  4947.4     0.1       0
  4996.6    0.07       0  5002.6     0.1       0  5188.1    0.05       0
  5317.3     0.1       0  5323.0    0.05       0  5440.8     0.1       0
  5522.9    0.05       0  5617.3     0.1       0
Bank Sta=4996.6,5002.6
Exp/Cntr=0.3,0.1

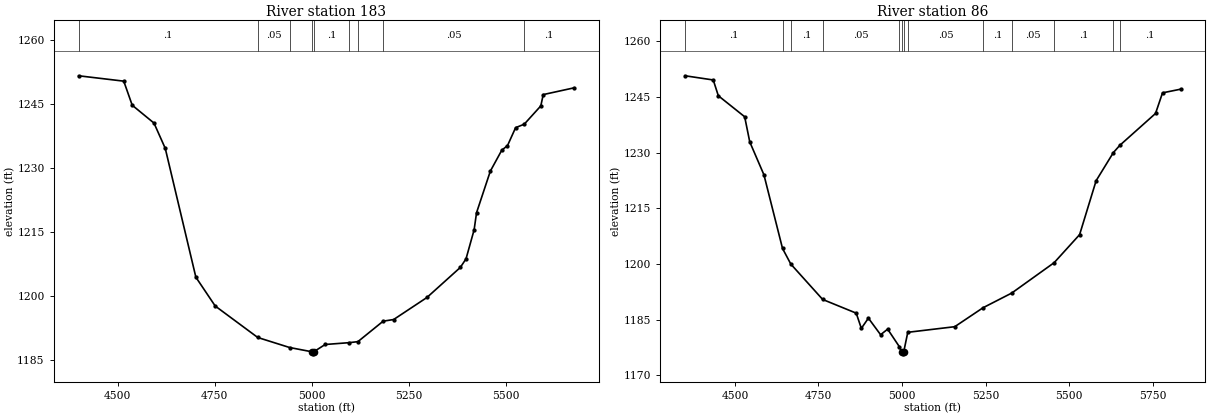
Type RM Length L Ch R = 1,183,97,97,97
BEGIN DESCRIPTION:
Mapping XS d55891aa
END DESCRIPTION:
XS GIS Cut Line= 4
      2964320.42     10047352.61      2963877.71     10047694.62
      2963816.95     10047823.10      2964153.34     10048288.87
#Sta/Elev= 30
  4399.4 1251.60  4515.6 1250.34  4537.4 1244.70  4593.5 1240.51  4622.5 1234.58
  4701.3 1204.39  4751.1 1197.64  4860.7 1190.26  4942.8 1187.91  4999.1 1186.93
  5001.8 1186.43  5005.1 1186.93  5034.3 1188.62  5096.3 1189.05  5118.6 1189.29
  5183.7 1194.09  5210.6 1194.47  5296.4 1199.64  5382.3 1206.68  5397.0 1208.69
  5417.9 1215.52  5424.1 1219.51  5459.7 1229.27  5489.1 1234.16  5503.8 1235.23
  5524.7 1239.44  5546.9 1240.25  5589.6 1244.54  5595.8 1247.19  5675.5 1248.78
#Mann=9,-1,0
  4399.4     0.1       0  4860.7    0.05       0  4942.8     0.1       0
  4999.1    0.07       0  5005.1     0.1       0  5096.3    0.05       0
  5118.6     0.1       0  5183.7    0.05       0  5546.9     0.1       0
Bank Sta=4999.1,5005.1
Exp/Cntr=0.3,0.1

Type RM Length L Ch R = 1,86,0,0,0
BEGIN DESCRIPTION:
UNT 1011 IN LATR 1.0
END DESCRIPTION:
XS GIS Cut Line= 4
      2964306.50     10047324.85      2963792.64     10047651.22
      2963700.63     10047831.78      2964139.10     10048339.57
#Sta/Elev= 30
  4351.0 1250.73  4435.2 1249.60  4450.4 1245.35  4529.2 1239.69  4544.4 1232.92
  4586.8 1224.06  4642.4 1204.22  4667.3 1200.00  4762.5 1190.48  4862.9 1186.79
  4878.2 1182.69  4899.3 1185.44  4935.8 1180.98  4956.9 1182.48  4992.1 1177.73
  4998.9 1176.33  5001.7 1175.83  5004.9 1176.33  5017.1 1181.63  5157.6 1183.14
  5242.1 1188.24  5328.2 1192.21  5455.0 1200.39  5531.1 1207.94  5580.5 1222.47
  5632.0 1230.03  5651.2 1231.98  5758.2 1240.58  5779.1 1246.13  5833.3 1247.12
#Mann=13,-1,0
  4351.0     0.1       0  4642.4    0.05       0  4667.3     0.1       0
  4762.5    0.05       0  4992.1     0.1       0  4998.9    0.07       0
  5004.9     0.1       0  5017.1    0.05       0  5242.1     0.1       0
  5328.2    0.05       0  5455.0     0.1       0  5632.0    0.05       0
  5651.2     0.1       0
Bank Sta=4998.9,5004.9
Exp/Cntr=0.3,0.1

Chan Stop Cuts=-1