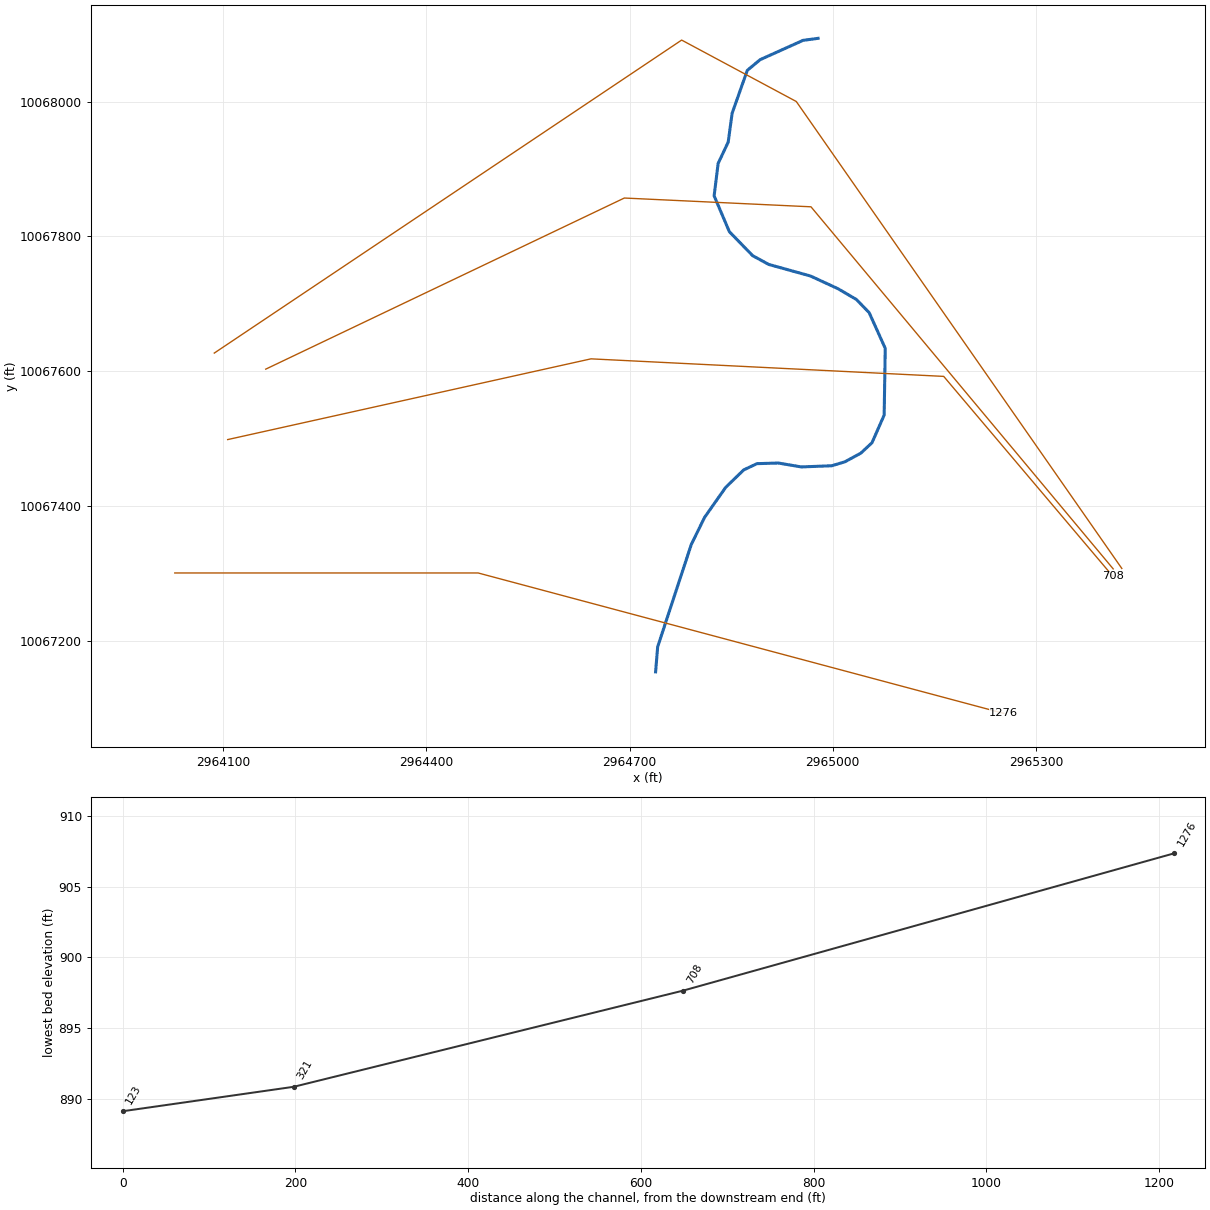
--- UNT 1013 IN LATR.prj (project) ---

Proj Title=UNT 1013 IN LATR Base Level Engineering
Current Plan=p01
Default Exp/Contr=0.3,0.1
English Units
Geom File=g01
Flow File=f01
Plan File=p01
Y Axis Title=Elevation
X Axis Title(PF)=Main Channel Distance
X Axis Title(XS)=Station
BEGIN DESCRIPTION:
UNT 1013 IN LATR
END DESCRIPTION:
DSS Export Rating Curves= 0
DSS Export Rating Curve Sorted= 0
DSS Export Volume Flow Curves= 0
DXF OffsetX= 0
DXF OffsetY= 0
DXF ScaleX= 1
DXF ScaleY= 10

--- UNT 1013 IN LATR.p01 (plan) ---

Plan Title=Multiple Run
Program Version=4.10
Short Identifier=Multiple
Geom File=g01
Flow File=f01
Subcritical Flow
K Sum by GR= 0
Std Step Tol= 0.01
Critical Tol= 0.01
Num of Std Step Trials= 20
Max Error Tol= 0.3
Flow Tol Ratio= 0.001
Split Flow NTrial= 30
Split Flow Tol= 0.02
Split Flow Ratio= 0.02
Log Output Level= 0
Friction Slope Method= 1
Unsteady Friction Slope Method= 2
Unsteady Bridges Friction Slope Method= 1
Parabolic Critical Depth
Global Vel Dist= 1 , 1 , 1
Global Log Level= 0
CheckData=True
Encroach Param=-1 ,0,0, 0
BEGIN DESCRIPTION:
Multiple Run
END DESCRIPTION:
Computation Interval=1HOUR
Output Interval=1HOUR
Run HTab= 0
Run UNet= 0
Run PostProcess= 0
Run WQNet= 0
UNET Theta= 1
UNET Theta Warmup= 1
UNET ZTol= 0.02
UNET ZSATol= 0.05
UNET MxIter= 20
UNET MaxInSteps= 0
UNET DtIC= 0
UNET DtMin= 0
UNET MaxCRTS= 20
UNET WFStab= 2
UNET SFStab= 1
UNET WFX= 1
UNET SFX= 1
UNET DSS MLevel= 4
UNET DZMax Abort= 100
UNET Convert EG Bridges= 0
UNET Use Existing IB Tables=-1
UNET Froude Reduction=False
UNET Froude Limit= 1
UNET Froude Power= 10
UNET Time Slicing=0,0, 5
UNET Junction Losses=0
Instantaneous Interval=1HOUR
Write IC File= 0
Write IC File at Sim End=0
Echo Input=False
Echo Parameters=False
Echo Output=False
Write Detailed= 0
WQ AD Non Conservative
WQ ULTIMATE=-1
WQ Max Comp Step=1HOUR
WQ Output Interval=15MIN
WQ Output Selected Increments= 0
WQ Output face flow=0
WQ Output face velocity=0
WQ Output face area=0
WQ Output face dispersion=0
WQ Output cell volume=0
WQ Output cell surface area=0
WQ Output cell continuity=0
WQ Output cumulative cell continuity=0
WQ Output face conc=0
WQ Output face dconc_dx=0
WQ Output face courant=0
WQ Output face peclet=0
WQ Output face adv mass=0
WQ Output face disp mass=0
WQ Output cell mass=0
WQ Output cell source sink temp=0
WQ Output cell source sink nsm=0
WQ Output MaxMinRange=-1
WQ Daily Max Min Mean=-1
WQ Daily Range=0
WQ Daily Time=0
WQ Create Restart=0
WQ Fixed Restart=0
WQ System Summary=0
WQ Use Fixed Temperature=0
Sorting and Armoring Iterations= 10
XS Update Threshold= 0.02
Hydraulics Update Threshold= 0.02
Energy Slope Method= 1
Volume Change Method= 0
XS Weighting Method= 0
Number of US Weighted Cross Sections= 1
Number of DS Weighted Cross Sections= 1
Upstream XS Weight=0.25
Main XS Weight=0.5
Downstream XS Weight=0.25
Number of DS XS's Weighted with US Boundary= 1
Upstream Boundary Weight= 1
Weight of XSs Associated with US Boundary= 0
Number of US XS's Weighted with DS Boundary= 1
Downstream Boundary Weight= 0.5
Weight of XSs Associated with DS Boundary= 0.5
Sediment Output Level= 4
Mass or Volume Output= 0
Output Increment Type= 1
Profile and TS Output Increment= 10
XS Output Flag= 0
XS Output Increment= 10
Disregard all LS=0
Disregard all Conn=0
Disregard all Breaches=0
Disregard all Pumps=0

--- UNT 1013 IN LATR.f01 (steady flow) ---

Flow Title=Multiple
Program Version=4.10
Number of Profiles= 7
Profile Names=10-year,25-year,50-year,1pct_min,100-year,1pct_plu,500-year
River Rch & RM=UNT 1013 IN LATR,Reach-1         ,1276
    1102    1627    2092    1969    2663    3602    4332
Boundary for River Rch & Prof#=UNT 1013 IN LATR,Reach-1         , 1
Up Type= 0
Dn Type= 3
Dn Slope=0.005
Boundary for River Rch & Prof#=UNT 1013 IN LATR,Reach-1         , 2
Up Type= 0
Dn Type= 3
Dn Slope=0.005
Boundary for River Rch & Prof#=UNT 1013 IN LATR,Reach-1         , 3
Up Type= 0
Dn Type= 3
Dn Slope=0.005
Boundary for River Rch & Prof#=UNT 1013 IN LATR,Reach-1         , 4
Up Type= 0
Dn Type= 3
Dn Slope=0.005
Boundary for River Rch & Prof#=UNT 1013 IN LATR,Reach-1         , 5
Up Type= 0
Dn Type= 3
Dn Slope=0.005
Boundary for River Rch & Prof#=UNT 1013 IN LATR,Reach-1         , 6
Up Type= 0
Dn Type= 3
Dn Slope=0.005
Boundary for River Rch & Prof#=UNT 1013 IN LATR,Reach-1         , 7
Up Type= 0
Dn Type= 3
Dn Slope=0.005
DSS Import GetInterval= 0
DSS Import GetPeak= 0
DSS Import FillOption= 0

--- UNT 1013 IN LATR.g01 (geometry) ---

Geom Title=Existing Conditions
Program Version=4.10

River Reach=UNT 1013 IN LATR,Reach-1
Reach XY= 30
      2964738.47     10067153.73      2964741.52     10067190.87
      2964791.13     10067342.63      2964810.74     10067382.83
      2964841.89      10067427.4      2964868.57     10067453.37
      2964888.22     10067462.64      2964919.67     10067463.58
      2964953.55     10067457.79      2964998.57     10067459.52
      2965018.09     10067465.43       2965041.5     10067478.21
        2965058.     10067493.68      2965075.97     10067534.69
      2965077.56     10067633.78      2965053.83      10067686.7
      2965034.99     10067706.23      2965007.94     10067722.14
      2964967.35     10067741.01      2964905.51     10067758.26
      2964881.84     10067771.23      2964847.41     10067806.77
       2964824.9     10067860.02       2964830.8     10067908.05
      2964845.68     10067939.81      2964851.46     10067982.53
      2964873.86     10068046.19      2964892.91     10068062.11
      2964956.27     10068090.77      2964978.47     10068093.73

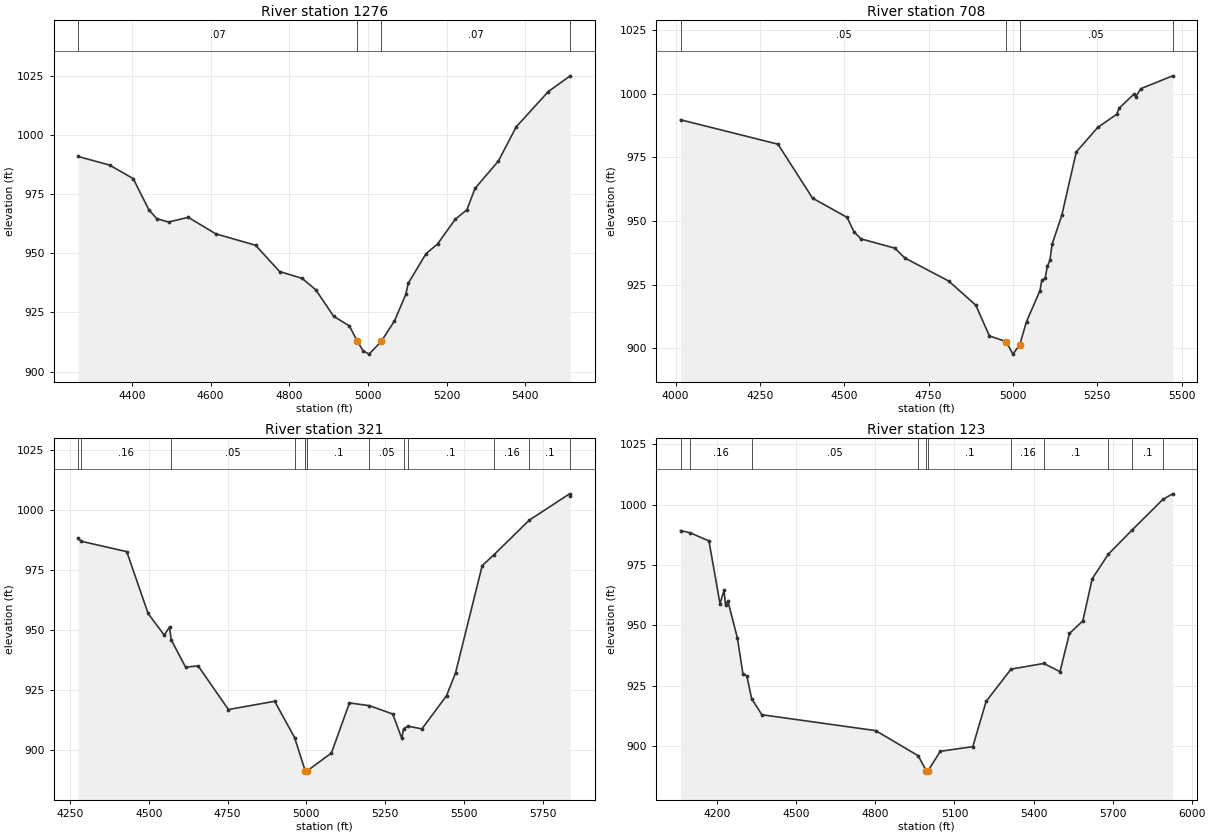
Type RM Length L Ch R = 1 ,1276    ,568,568,568
BEGIN DESCRIPTION:
UNT 1013 IN LATR 2.0
END DESCRIPTION:
XS GIS Cut Line= 3
      2964028.45     10067300.45       2964476.4     10067300.45
      2965252.47     10067092.11
#Sta/Elev= 30
  4263.2  990.95  4343.2  987.31  4403.2   981.6  4443.2  968.36  4463.2  964.66
  4493.2  963.22  4543.2  965.21  4613.2  958.24  4714.5   953.4  4775.4   942.3
  4832.9   939.4  4867.7  934.53  4912.9  923.37  4952.9   919.3  4972.1  913.12
  4987.7  908.79    5003  907.36  5034.3   912.8  5067.7  921.41  5096.4   932.6
  5102.5  937.27  5148.2  949.91  5177.3  953.95  5222.5  964.46  5251.7  968.36
  5272.4  977.43  5332.1  989.07  5377.3  1003.5  5458.8  1018.4  5514.7 1025.06
#Mann= 4 ,-1 , 0
  4263.2     .07       0  4972.1     .05       0  5034.3     .07       0
  5514.7      .1       0
Bank Sta=4972.1,5034.3
XS Rating Curve= 0 ,0
Exp/Cntr=0.3,0.1

Type RM Length L Ch R = 1 ,708     ,451,451,451
BEGIN DESCRIPTION:
Mapping XS 430050bf
END DESCRIPTION:
XS GIS Cut Line= 4
      2964106.58     10067498.36      2964643.06     10067618.16
       2965163.9     10067592.12       2965413.7     10067295.47
#Sta/Elev= 30
  4014.5  989.79  4303.3   980.2  4405.8  958.99  4508.3  951.41  4528.7  945.77
  4549.2  942.98  4649.7  939.32  4679.7  935.44  4809.9  926.36    4890  916.87
  4930.1  904.83  4980.1  902.56  4999.9  897.65  5020.2  901.34  5040.2  910.46
  5080.2  922.62  5085.5  926.69  5095.3   927.4  5101.9  932.14  5109.6  934.54
  5116.2  940.91  5144.8  952.23  5187.7  977.12  5251.4  986.78  5307.4  991.93
  5315.1  994.37    5358   999.8  5364.6  998.93  5378.9 1002.01  5473.5 1007.07
#Mann= 4 ,-1 , 0
  4014.5     .05       0  4980.1     .03       0  5020.2     .05       0
  5473.5      .1       0
Bank Sta=4980.1,5020.2
XS Rating Curve= 0 ,0
Exp/Cntr=0.3,0.1

Type RM Length L Ch R = 1 ,321     ,198,198,198
BEGIN DESCRIPTION:
Mapping XS 3767f9df
END DESCRIPTION:
XS GIS Cut Line= 4
      2964162.78     10067602.87       2964692.3     10067856.78
      2964967.91     10067843.75      2965414.18     10067306.49
#Sta/Elev= 30
  4275.9  988.07  4285.3  986.88  4430.1  982.56    4498  956.83  4548.9  947.83
    4566  951.17  4571.2  945.89  4616.9  934.49  4656.6  935.05  4752.8  916.87
  4899.4  920.32  4962.9  905.16  4996.5  891.34  4999.2  890.84  5002.5  891.34
  5079.6   898.8  5136.8  919.63  5200.3  918.48  5274.3     915  5302.9  904.86
  5308.6  908.91  5323.1  909.95  5366.7  908.82  5444.9  922.64  5473.5  932.14
  5558.1  976.77  5594.9   981.2  5707.4  995.66  5835.2 1006.61  5837.5 1005.67
#Mann= 12 ,-1 , 0
  4275.9     .05       0  4285.3     .16       0  4571.2     .05       0
  4962.9      .1       0  4996.5     .07       0  5002.5      .1       0
  5200.3     .05       0  5308.6     .16       0  5323.1      .1       0
  5594.9     .16       0  5707.4      .1       0  5835.2     .16       0
Bank Sta=4996.5,5002.5
XS Rating Curve= 0 ,0
Exp/Cntr=0.3,0.1

Type RM Length L Ch R = 1 ,123     ,0,0,0
BEGIN DESCRIPTION:
UNT 1013 IN LATR 1.0
END DESCRIPTION:
XS GIS Cut Line= 4
      2964086.81     10067626.73      2964776.93     10068091.15
      2964946.21       10068000.       2965426.9     10067307.12
#Sta/Elev= 30
  4060.5  989.28  4097.9  988.33  4168.3  984.97  4210.3  958.92  4225.3  964.52
  4231.3  958.51  4240.2  960.03  4276.2  944.74  4297.2  929.91  4312.2  929.01
  4330.1  919.59  4369.2  912.91  4801.1  906.32  4962.4   895.9  4993.3  889.61
  4996.1  889.11  4999.3  889.61  5046.3  897.75  5169.4  899.67  5220.1  918.44
  5314.7  931.83  5438.7  934.17  5500.4  930.78  5536.2  946.61  5586.9   951.8
  5622.7  969.31  5683.9  979.51  5774.8   989.6  5890.8 1002.21  5927.9 1004.52
#Mann= 11 ,-1 , 0
  4060.5     .05       0  4097.9     .16       0  4330.1     .05       0
  4962.4      .1       0  4993.3     .07       0  4999.3      .1       0
  5314.7     .16       0  5438.7      .1       0  5683.9     .16       0
  5774.8      .1       0  5890.8     .16       0
Bank Sta=4993.3,4999.3
XS Rating Curve= 0 ,0
Exp/Cntr=0.3,0.1

Chan Stop Cuts=-1
Use User Specified Reach Order=0
Composite Channel Slope=5