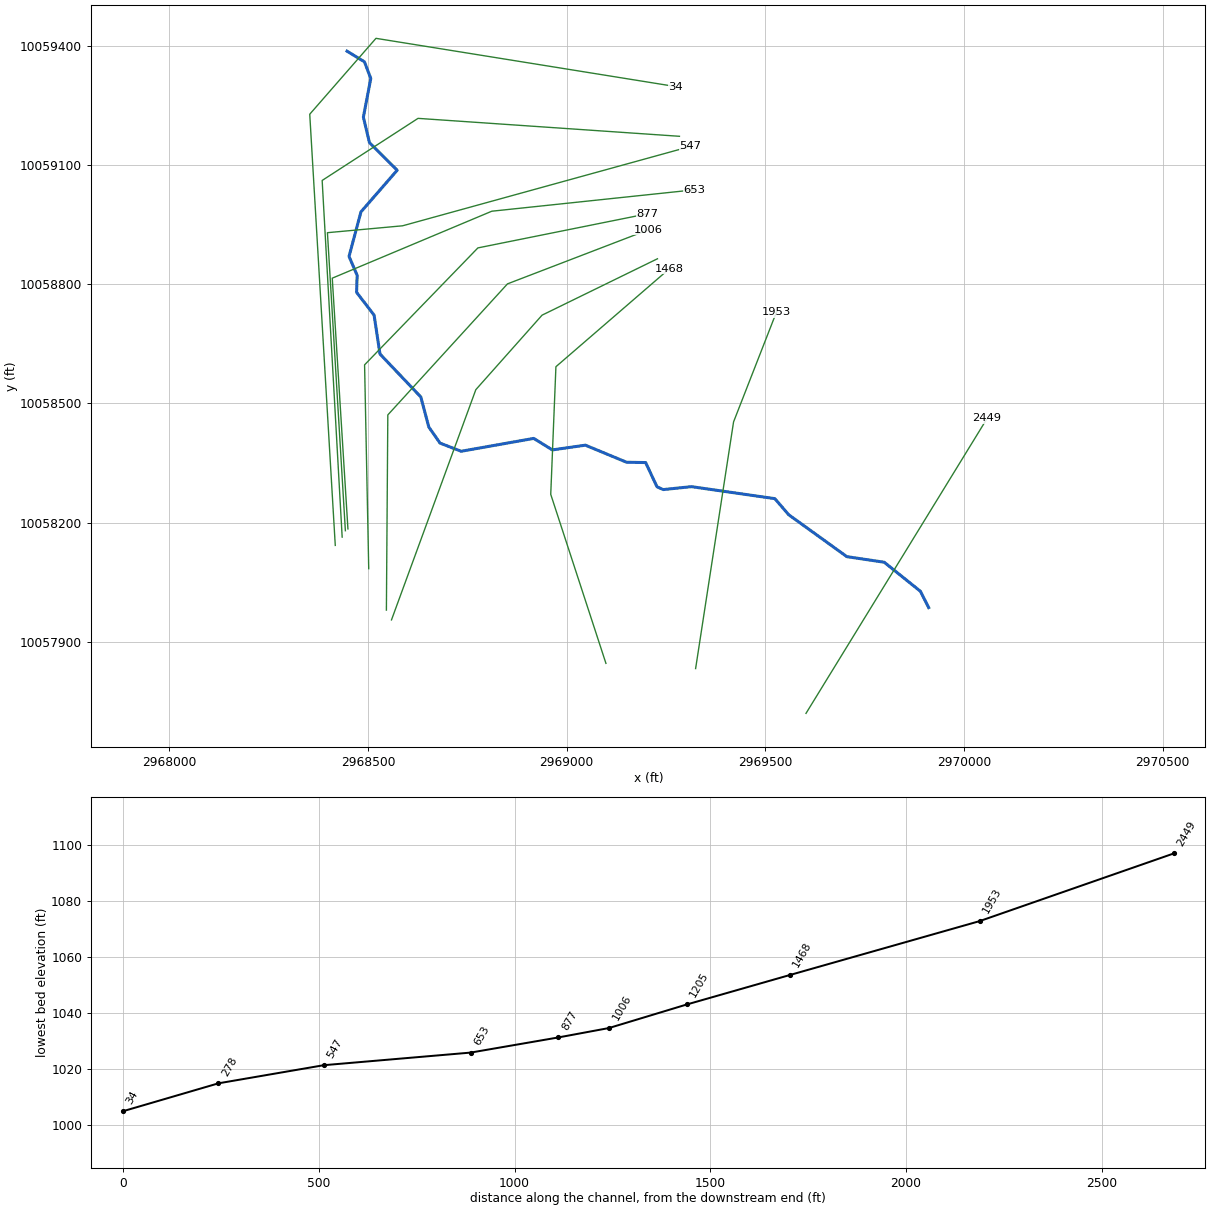
--- UNT 1015 IN LATR.prj (project) ---

Proj Title=UNT 1015 IN LATR Base Level Engineering
Current Plan=p01
Default Exp/Contr=0.3,0.1
English Units
Geom File=g01
Flow File=f01
Plan File=p01
Y Axis Title=Elevation
X Axis Title(PF)=Main Channel Distance
X Axis Title(XS)=Station
BEGIN DESCRIPTION:
UNT 1015 IN LATR
END DESCRIPTION:
DSS Export Rating Curves= 0
DSS Export Rating Curve Sorted= 0
DSS Export Volume Flow Curves= 0
DXF OffsetX= 0
DXF OffsetY= 0
DXF ScaleX= 1
DXF ScaleY= 10

--- UNT 1015 IN LATR.p01 (plan) ---

Plan Title=Multiple Run
Short Identifier=Multiple
Geom File=g01
Flow File=f01
Subcritical Flow
K Sum by GR= 0
Std Step Tol= 0.01
Critical Tol= 0.01
Num of Std Step Trials= 20
Max Error Tol= 0.3
Flow Tol Ratio= 0.001
Split Flow NTrial= 30
Split Flow Tol= 0.02
Split Flow Ratio= 0.02
Log Output Level= 0
Friction Slope Method= 1
Unsteady Friction Slope Method= 2
Unsteady Bridges Friction Slope Method= 1
Parabolic Critical Depth
Global Vel Dist=  1 , 1 , 1
Global Log Level= 0
CheckData=True
Encroach Param= -1, 0, 0, 0
BEGIN DESCRIPTION:
Multiple Run
END DESCRIPTION:

--- UNT 1015 IN LATR.f01 (steady flow) ---

Flow Title=Multiple
Program Version=4.10
Number of Profiles= 7
Profile Names=10-year,25-year,50-year,1pct_min,100-year,1pct_plu,500-year
River Rch & RM=UNT 1015 IN LATR,Reach-1         ,2449
     241     322     387     344     465     629     668
Boundary for River Rch & Prof#=UNT 1015 IN LATR,Reach-1         , 1
Up Type= 0
Dn Type= 3
Dn Slope=0.046
Boundary for River Rch & Prof#=UNT 1015 IN LATR,Reach-1         , 2
Up Type= 0
Dn Type= 3
Dn Slope=0.046
Boundary for River Rch & Prof#=UNT 1015 IN LATR,Reach-1         , 3
Up Type= 0
Dn Type= 3
Dn Slope=0.046
Boundary for River Rch & Prof#=UNT 1015 IN LATR,Reach-1         , 4
Up Type= 0
Dn Type= 3
Dn Slope=0.046
Boundary for River Rch & Prof#=UNT 1015 IN LATR,Reach-1         , 5
Up Type= 0
Dn Type= 3
Dn Slope=0.046
Boundary for River Rch & Prof#=UNT 1015 IN LATR,Reach-1         , 6
Up Type= 0
Dn Type= 3
Dn Slope=0.046
Boundary for River Rch & Prof#=UNT 1015 IN LATR,Reach-1         , 7
Up Type= 0
Dn Type= 3
Dn Slope=0.046
DSS Import GetInterval= 0
DSS Import GetPeak= 0
DSS Import FillOption= 0

--- UNT 1015 IN LATR.g01 (geometry) ---

Geom Title=Existing Conditions
Program Version=4.10

River Reach=UNT 1015 IN LATR,Reach-1
Reach XY= 30
        2969911.     10057986.28      2969890.23     10058027.43
      2969799.05     10058100.53      2969705.12     10058114.56
      2969558.84     10058219.97      2969523.87     10058260.53
      2969314.03     10058290.74      2969242.94     10058283.35
      2969227.23     10058290.53       2969198.7     10058351.38
      2969150.94      10058352.1      2969047.11     10058395.09
      2968963.93     10058383.23      2968917.11     10058412.15
      2968734.46     10058379.77      2968681.33     10058400.26
      2968653.03     10058440.83       2968632.9     10058516.46
      2968530.14     10058624.54      2968515.34     10058722.49
      2968471.27     10058779.76      2968472.74     10058822.56
      2968452.31     10058870.16      2968482.25     10058982.16
      2968573.38     10059086.96      2968503.68     10059156.48
      2968488.38     10059220.61      2968507.04     10059317.92
      2968491.11     10059359.81      2968447.24     10059386.67

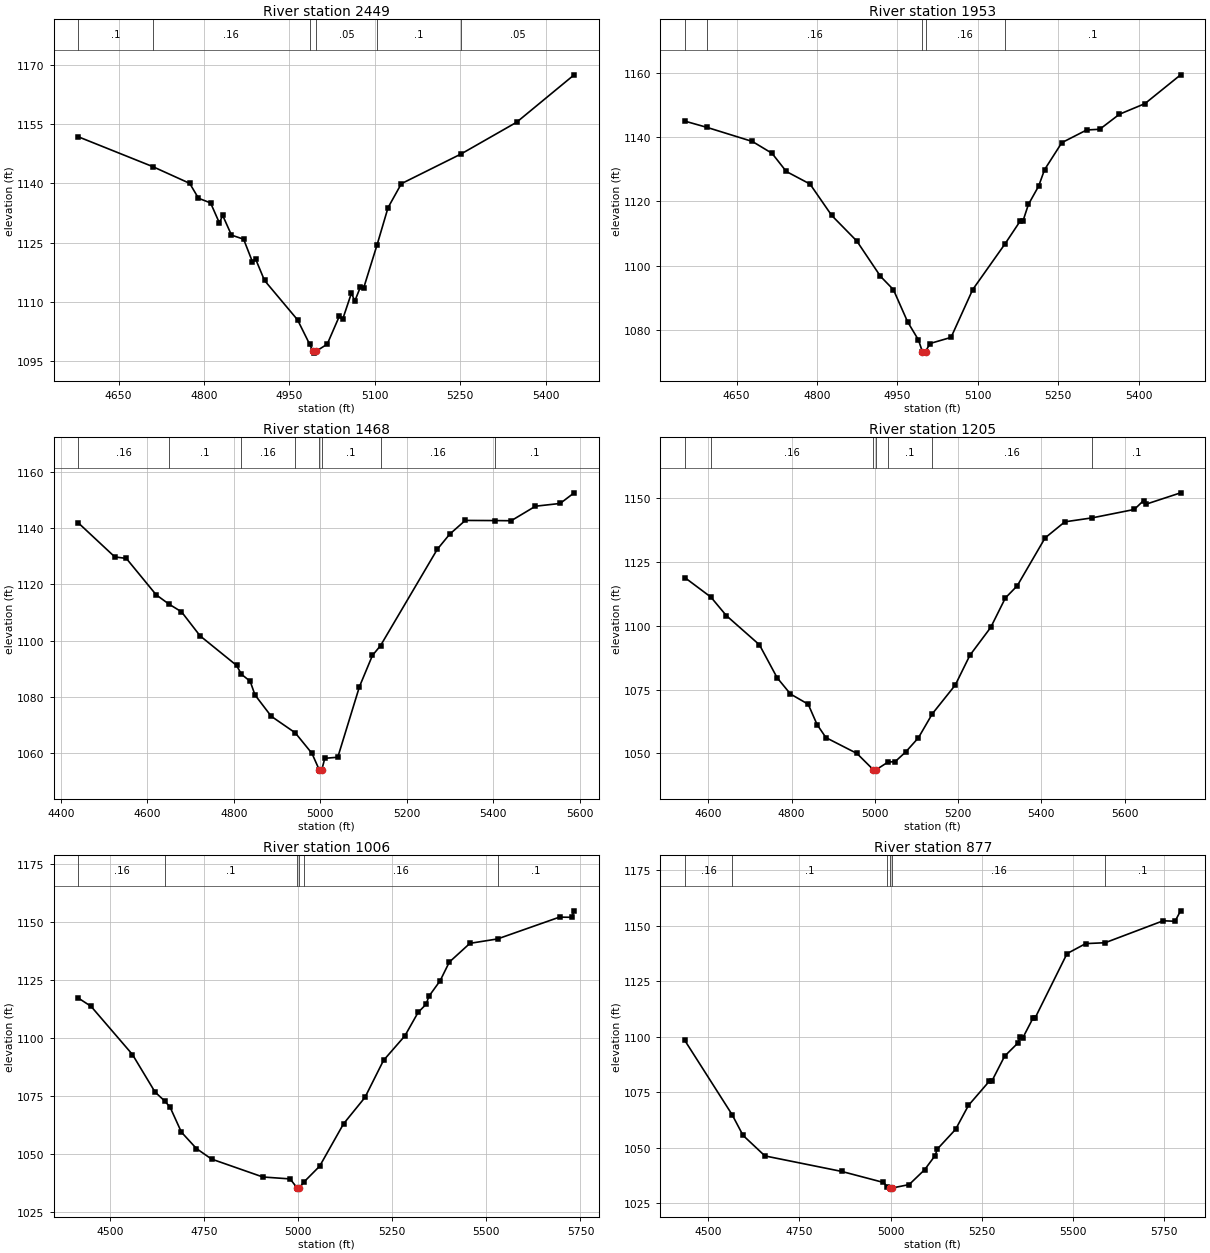
Type RM Length L Ch R = 1 ,2449    ,496,496,496
BEGIN DESCRIPTION:
UNT 1015 IN LATR 4.0
END DESCRIPTION:
XS GIS Cut Line= 2
      2969602.28     10057720.17      2970057.99     10058462.33
#Sta/Elev= 30
  4579.4 1151.76  4709.9 1144.23    4775 1139.98  4790.4 1136.22  4811.7 1135.03
  4827.1 1129.99    4833 1131.86  4848.4 1126.89  4869.7 1125.86  4885.1 1120.17
    4891 1120.76  4906.4 1115.42  4964.4 1105.46  4985.7 1099.28  4991.3 1097.53
    4994 1097.03  4997.3 1097.53  5016.6  1099.3  5037.9  1106.4  5043.7 1105.59
  5059.1 1112.21    5065 1110.19  5074.6 1113.68  5080.4 1113.43  5104.2 1124.46
  5123.4 1133.84  5146.8  1139.9  5251.3 1147.39  5349.2 1155.44  5450.3 1167.44
#Mann= 6 ,-1 , 0
  4579.4      .1       0  4709.9     .16       0  4985.7     .07       0
  4997.3     .05       0  5104.2      .1       0  5251.3     .05       0
Bank Sta=4991.3,4997.3
XS Rating Curve= 0 ,0
Exp/Cntr=0.3,0.1

Type RM Length L Ch R = 1 ,1953    ,485,485,485
BEGIN DESCRIPTION:
UNT 1015 IN LATR 3.0
END DESCRIPTION:
XS GIS Cut Line= 3
      2969324.48     10057832.95      2969419.97     10058453.66
      2969527.96     10058730.11
#Sta/Elev= 30
  4553.4 1144.95  4595.4 1142.97  4679.5 1138.62  4716.1 1134.94  4742.7  1129.3
  4786.9  1125.4  4827.4 1115.64  4874.2 1107.69  4918.4 1096.72  4942.5 1092.58
    4969 1082.58  4989.2 1076.96  4996.4 1073.36  4999.1 1072.86  5002.4 1073.36
  5010.8 1075.85    5050 1077.75  5090.4 1092.61  5150.8 1106.84  5178.9 1113.87
  5184.1 1113.87  5194.3 1119.07  5213.4 1124.75  5224.4 1129.86  5256.6 1138.25
  5302.9 1142.19  5327.4 1142.42    5364 1147.08  5411.6 1150.38  5478.2 1159.33
#Mann= 5 ,-1 , 0
  4553.4      .1       0  4595.4     .16       0  4996.4     .07       0
  5002.4     .16       0  5150.8      .1       0
Bank Sta=4996.4,5002.4
XS Rating Curve= 0 ,0
Exp/Cntr=0.3,0.1

Type RM Length L Ch R = 1 ,1468    ,263,263,263
BEGIN DESCRIPTION:
UNT 1015 IN LATR 2.0
END DESCRIPTION:
XS GIS Cut Line= 4
      2969098.79     10057846.04       2968959.9     10058271.37
      2968972.92     10058592.55      2969258.65     10058839.31
#Sta/Elev= 30
  4440.6 1141.91  4524.9 1129.81  4551.5 1129.28  4620.5 1116.34    4650 1113.03
  4679.1 1110.29  4722.2 1101.71  4806.4 1091.22  4817.7 1088.06  4837.9 1085.57
    4849 1080.71  4886.6 1073.12  4942.1 1067.23  4980.7 1059.93  4997.5  1054.1
  5000.2  1053.6  5003.5  1054.1  5010.5 1058.16  5040.5 1058.54  5090.6 1083.66
  5120.6 1094.76  5139.3 1098.25  5270.5 1132.51  5299.1 1137.87  5335.2 1142.79
    5404 1142.74  5441.4 1142.68  5497.6 1147.85  5554.6 1148.83    5587 1152.61
#Mann= 8 ,-1 , 0
  4440.6     .16       0    4650      .1       0  4817.7     .16       0
  4942.1      .1       0  4997.5     .07       0  5003.5      .1       0
  5139.3     .16       0    5404      .1       0
Bank Sta=4997.5,5003.5
XS Rating Curve= 0 ,0
Exp/Cntr=0.3,0.1

Type RM Length L Ch R = 1 ,1205    ,199,199,199
BEGIN DESCRIPTION:
Mapping XS 26a29545
END DESCRIPTION:
XS GIS Cut Line= 4
      2968559.12     10057955.33      2968771.37     10058534.78
      2968938.04     10058722.28      2969228.44     10058864.22
#Sta/Elev= 30
  4543.5 1118.82  4606.2 1111.18  4643.2 1103.96  4722.8 1092.52  4765.4 1079.61
  4797.4 1073.26    4840 1069.26  4861.3  1061.3  4882.6  1056.2  4957.1    1050
  4996.7 1043.59  4999.5 1043.09  5002.7 1043.59  5031.6 1046.62    5049 1046.83
  5074.2 1050.59  5104.7 1056.12  5138.2 1065.53  5193.3 1076.77  5228.4 1088.41
  5278.5 1099.33  5313.7 1110.85  5342.1 1115.59  5409.1 1134.34  5456.5 1140.63
  5522.4 1142.19  5623.4 1145.47  5645.7 1148.96  5652.6 1147.59  5734.7 1151.98
#Mann= 7 ,-1 , 0
  4543.5      .1       0  4606.2     .16       0  4996.7     .07       0
  5002.7     .16       0  5031.6      .1       0  5138.2     .16       0
  5522.4      .1       0
Bank Sta=4996.7,5002.7
XS Rating Curve= 0 ,0
Exp/Cntr=0.3,0.1

Type RM Length L Ch R = 1 ,1006    ,129,129,129
BEGIN DESCRIPTION:
Mapping XS 7633f242
END DESCRIPTION:
XS GIS Cut Line= 4
      2968546.31     10057980.04      2968549.89     10058471.23
      2968851.04     10058801.05      2969204.75     10058936.82
#Sta/Elev= 30
  4416.6 1117.18  4450.3 1113.62  4560.3 1092.81  4620.3  1076.6  4646.1 1072.71
  4660.3 1070.04  4690.3 1059.28  4730.3 1052.18  4770.3 1047.66  4906.6 1039.91
    4979 1039.08  4997.7 1035.17  5000.4 1034.67  5003.7 1035.17  5015.5 1037.71
  5057.4 1044.57  5120.9 1062.88  5177.7 1074.26    5227 1090.26  5283.7 1100.85
  5318.9 1110.99  5340.5 1114.57  5347.2 1117.87  5377.2 1124.61  5401.8 1132.72
  5456.5 1140.82  5529.8 1142.72  5694.4 1152.14  5726.6 1152.06  5733.3 1154.86
#Mann= 6 ,-1 , 0
  4416.6     .16       0  4646.1      .1       0  4997.7     .07       0
  5003.7      .1       0  5015.5     .16       0  5529.8      .1       0
Bank Sta=4997.7,5003.7
XS Rating Curve= 0 ,0
Exp/Cntr=0.3,0.1

Type RM Length L Ch R = 1 ,877     ,224,224,224
BEGIN DESCRIPTION:
Mapping XS ce10d1ab
END DESCRIPTION:
XS GIS Cut Line= 4
      2968501.84      10058084.3      2968491.42     10058597.28
      2968776.58     10058891.55      2969203.57     10058977.47
#Sta/Elev= 30
  4436.1 1098.35  4565.7 1064.89  4595.6 1055.56  4655.6 1046.29  4865.6 1039.31
    4980 1034.35  4991.1 1032.46  4998.1 1031.82  5000.8 1031.32  5004.1 1031.82
  5050.7 1033.37  5093.1 1040.06  5121.4 1046.34  5128.4 1049.46    5178 1058.27
  5213.3 1069.08  5269.9 1079.88    5277 1079.91  5312.3 1091.25  5347.8 1097.04
  5354.7 1099.71  5362.5 1099.63  5390.9 1108.67    5396 1108.53  5483.3 1137.48
  5534.3 1141.99  5587.7 1142.39  5746.8 1152.29  5779.1 1152.06  5794.5 1156.77
#Mann= 6 ,-1 , 0
  4436.1     .16       0  4565.7      .1       0  4991.1     .16       0
  4998.1     .07       0  5004.1     .16       0  5587.7      .1       0
Bank Sta=4998.1,5004.1
XS Rating Curve= 0 ,0
Exp/Cntr=0.3,0.1

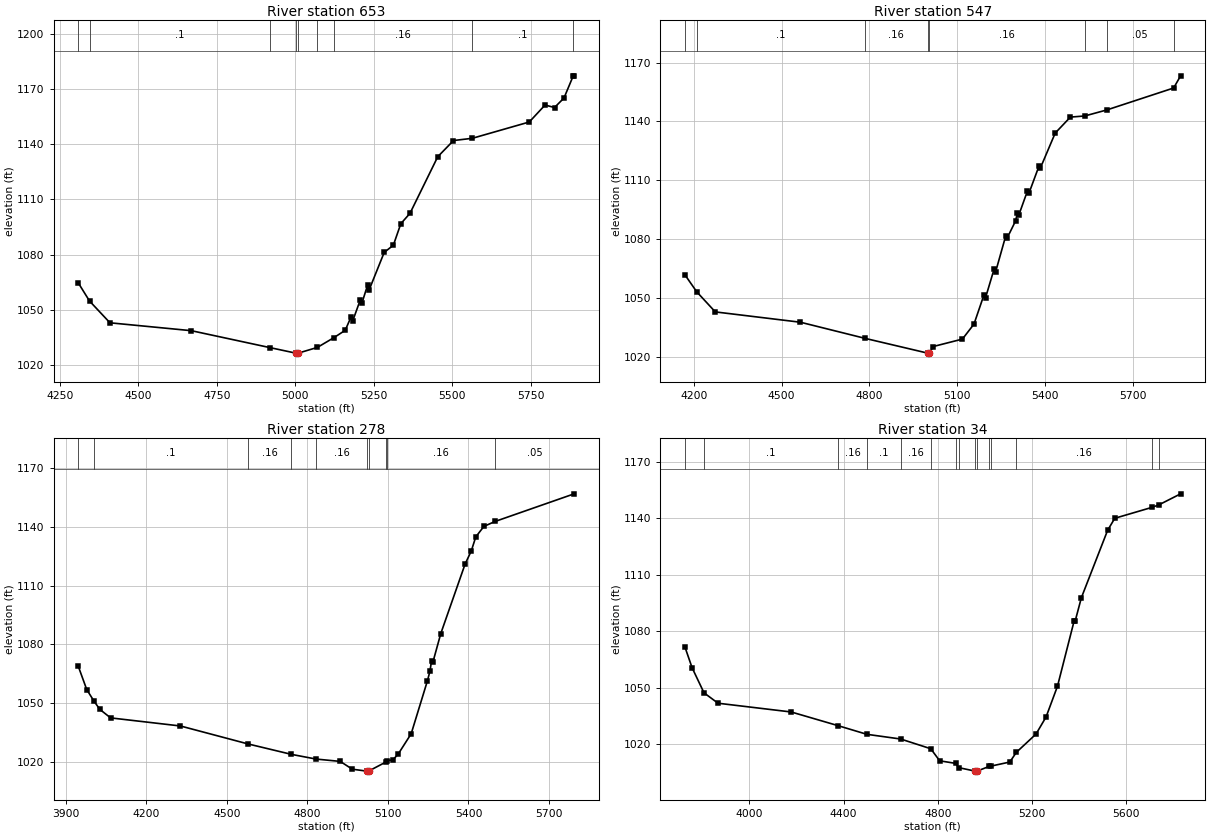
Type RM Length L Ch R = 1 ,653     ,375,375,375
BEGIN DESCRIPTION:
Mapping XS bce573f4
END DESCRIPTION:
XS GIS Cut Line= 4
      2968449.52     10058184.39      2968410.08     10058815.39
       2968811.6     10058983.89      2969320.69     10059037.67
#Sta/Elev= 30
  4308.5 1064.57  4344.3 1054.74  4409.3 1042.93  4668.5 1038.65  4919.2 1029.44
  5002.3 1026.41    5005 1025.91  5008.3 1026.41    5070 1029.56  5123.2 1034.91
  5158.7 1038.85    5177 1045.98  5182.5 1043.88  5206.2 1055.12  5211.7 1053.49
    5230  1063.4  5235.4 1061.02    5283 1081.21  5312.1 1085.09  5335.9 1096.79
  5365.1 1102.42  5453.5 1133.17  5503.7 1141.98  5563.6 1143.19  5745.1 1152.05
  5795.4 1161.27  5825.5 1159.92  5855.7 1165.08  5885.2 1177.14  5888.1 1177.14
#Mann= 9 ,-1 , 0
  4308.5     .16       0  4344.3      .1       0  4919.2     .16       0
  5002.3     .07       0  5008.3     .16       0    5070      .1       0
  5123.2     .16       0  5563.6      .1       0  5885.2     .05       0
Bank Sta=5002.3,5008.3
XS Rating Curve= 0 ,0
Exp/Cntr=0.3,0.1

Type RM Length L Ch R = 1 ,547     ,269,269,269
BEGIN DESCRIPTION:
Mapping XS 9eb604e2
END DESCRIPTION:
XS GIS Cut Line= 4
      2968443.08     10058179.85      2968397.94     10058929.84
      2968587.18      10058947.2      2969311.18     10059146.86
#Sta/Elev= 30
  4169.8 1061.92  4210.9 1053.11  4273.9 1042.93  4564.4 1037.67  4784.7 1029.46
    4999 1021.91  5001.8 1021.41    5005 1021.91  5017.8 1025.29  5117.3 1029.07
  5156.9 1036.72  5191.2 1051.71  5196.4 1050.21  5225.6 1064.78  5230.8  1063.4
  5265.2 1081.66  5270.3 1080.66  5299.2 1089.41  5304.7 1093.33  5309.9 1092.29
  5339.1 1104.48  5344.3 1103.34  5378.6  1117.2  5383.8 1116.37  5434.1 1134.08
  5485.9 1142.23  5534.8 1142.79  5610.8  1145.9  5838.3 1157.05  5862.2 1163.26
#Mann= 8 ,-1 , 0
  4169.8     .16       0  4210.9      .1       0  4784.7     .16       0
    4999     .07       0    5005     .16       0  5534.8      .1       0
  5610.8     .05       0  5838.3      .1       0
Bank Sta=4999,5005
XS Rating Curve= 0 ,0
Exp/Cntr=0.3,0.1

Type RM Length L Ch R = 1 ,278     ,244,244,244
BEGIN DESCRIPTION:
Mapping XS 877c72c0
END DESCRIPTION:
XS GIS Cut Line= 4
      2968435.01     10058163.73      2968384.66      10059061.3
      2968625.98     10059217.55      2969283.76     10059172.42
#Sta/Elev= 30
  3947.6 1068.79  3978.9 1056.99  4005.9 1051.11  4027.7 1046.89  4067.8 1042.57
  4327.7 1038.45  4578.2 1029.34  4741.1 1023.98  4832.8 1021.59  4922.6  1020.4
  4967.5 1016.43  5021.9 1015.44  5024.6 1014.94  5027.9 1015.44  5092.4 1020.07
  5097.2  1020.8  5118.5 1021.21  5137.8 1024.02  5186.7  1034.5  5246.8  1061.3
  5256.8 1066.49  5262.4 1071.62  5267.4  1070.9  5296.9 1085.54  5387.2 1120.86
  5410.6 1127.69  5427.2 1134.78  5457.3 1140.12  5498.9 1142.64  5793.4 1156.72
#Mann= 10 ,-1 , 0
  3947.6     .16       0  4005.9      .1       0  4578.2     .16       0
  4741.1      .1       0  4832.8     .16       0  5021.9     .07       0
  5027.9     .16       0  5092.4      .1       0  5097.2     .16       0
  5498.9     .05       0
Bank Sta=5021.9,5027.9
XS Rating Curve= 0 ,0
Exp/Cntr=0.3,0.1

Type RM Length L Ch R = 1 ,34      ,0,0,0
BEGIN DESCRIPTION:
UNT 1015 IN LATR 1.0
END DESCRIPTION:
XS GIS Cut Line= 4
      2968417.65     10058142.85      2968353.41     10059227.96
      2968520.08     10059418.94      2969274.38     10059297.55
#Sta/Elev= 30
    3726 1071.79  3756.9 1060.56  3807.5 1047.19  3867.1 1041.65  4177.7 1036.99
  4376.8  1029.7  4498.8  1025.1  4642.2  1022.6  4769.9 1017.43  4807.9 1010.99
  4875.4 1009.64  4889.1 1007.35  4959.6 1005.47  4962.4 1004.97  4965.6 1005.47
  5018.5 1008.05  5024.7 1008.16  5105.4 1010.34  5133.4 1015.52  5216.8 1025.25
  5259.5 1034.37  5307.9 1050.73  5378.1 1085.27  5383.2 1085.54  5409.2 1097.81
  5520.6  1133.7    5551 1140.11    5708 1145.89  5737.1 1147.19  5830.5 1153.13
#Mann= 15 ,-1 , 0
    3726     .16       0  3807.5      .1       0  4376.8     .16       0
  4498.8      .1       0  4642.2     .16       0  4769.9      .1       0
  4875.4     .05       0  4889.1      .1       0  4959.6     .07       0
  4965.6      .1       0  5018.5     .05       0  5024.7      .1       0
  5133.4     .16       0    5708     .05       0  5737.1      .1       0
Bank Sta=4959.6,4965.6
XS Rating Curve= 0 ,0
Exp/Cntr=0.3,0.1

Chan Stop Cuts=-1
Use User Specified Reach Order=0
Composite Channel Slope=5