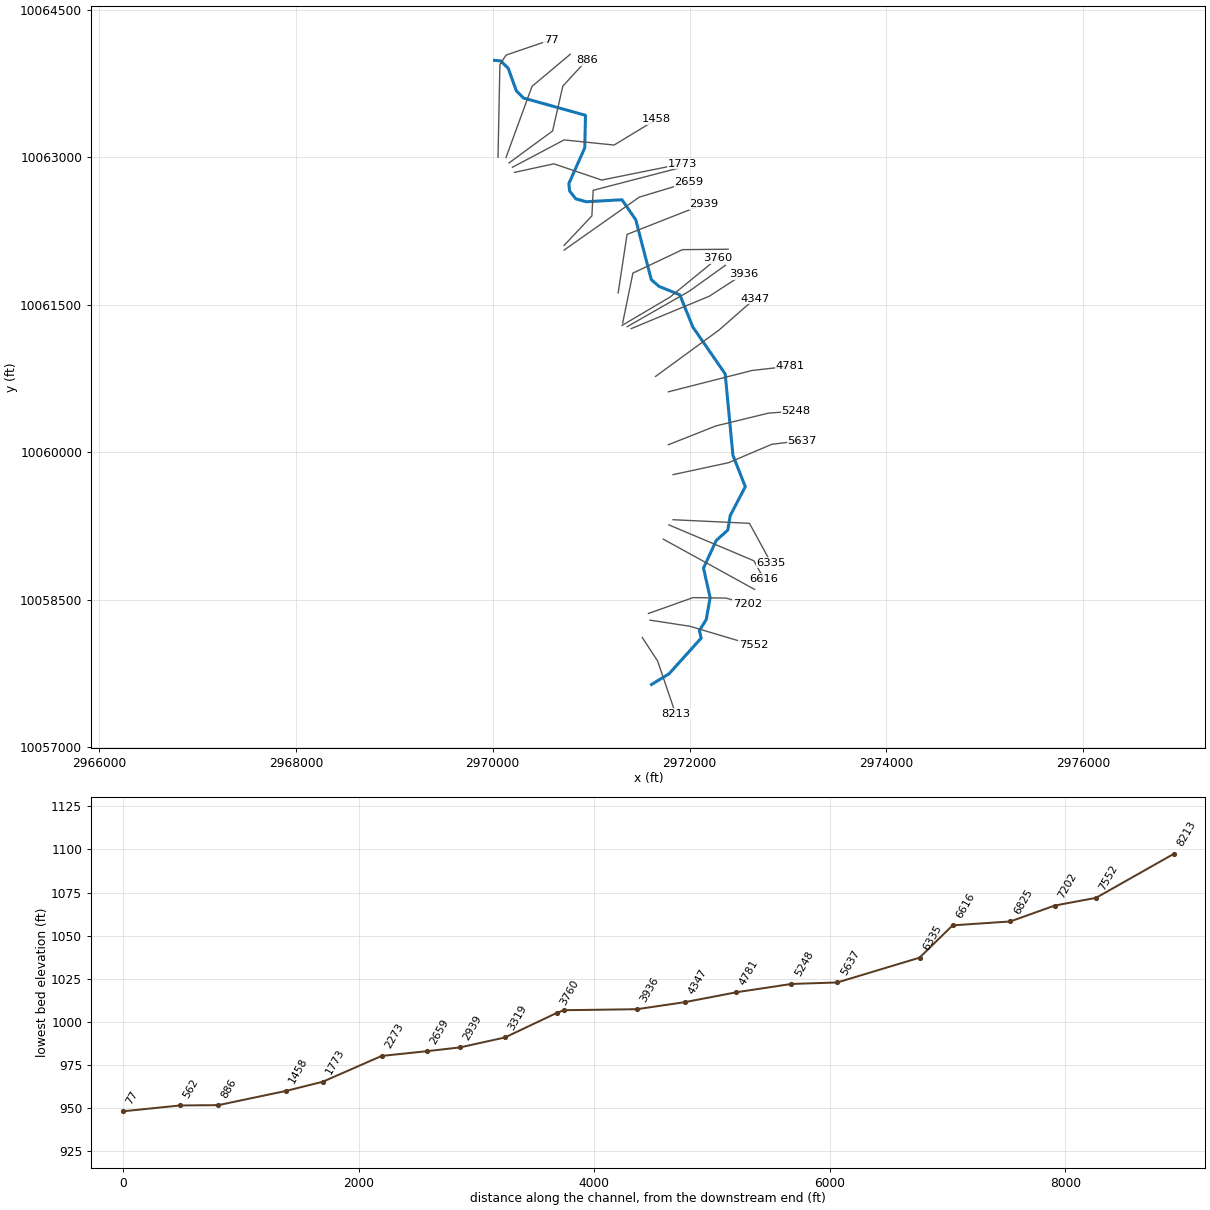
--- UNT 1016 IN LATR.prj (project) ---

Proj Title=UNT 1016 IN LATR Base Level Engineering
Current Plan=p01
Default Exp/Contr=0.3,0.1
English Units
Geom File=g01
Flow File=f01
Plan File=p01
Y Axis Title=Elevation
X Axis Title(PF)=Main Channel Distance
X Axis Title(XS)=Station
BEGIN DESCRIPTION:
UNT 1016 IN LATR
END DESCRIPTION:
DSS Export Rating Curves= 0
DSS Export Rating Curve Sorted= 0
DSS Export Volume Flow Curves= 0
DXF OffsetX= 0
DXF OffsetY= 0
DXF ScaleX= 1
DXF ScaleY= 10

--- UNT 1016 IN LATR.p01 (plan) ---

Plan Title=Multiple Run
Short Identifier=Multiple
Geom File=g01
Flow File=f01
Subcritical Flow
K Sum by GR= 0
Std Step Tol= 0.01
Critical Tol= 0.01
Num of Std Step Trials= 20
Max Error Tol= 0.3
Flow Tol Ratio= 0.001
Split Flow NTrial= 30
Split Flow Tol= 0.02
Split Flow Ratio= 0.02
Log Output Level= 0
Friction Slope Method= 1
Unsteady Friction Slope Method= 2
Unsteady Bridges Friction Slope Method= 1
Parabolic Critical Depth
Global Vel Dist=  1 , 1 , 1
Global Log Level= 0
CheckData=True
Encroach Param= -1, 0, 0, 0
BEGIN DESCRIPTION:
Multiple Run
END DESCRIPTION:

--- UNT 1016 IN LATR.f01 (steady flow) ---

Flow Title=Multiple
Program Version=4.10
Number of Profiles= 7
Profile Names=10-year,25-year,50-year,1pct_min,100-year,1pct_plu,500-year
River Rch & RM=UNT 1016 IN LATR,Reach-1         ,8213
    1250    1852    2387    2252    3046    4120    4978
River Rch & RM=UNT 1016 IN LATR,Reach-1         ,5637
    1362    2022    2610    2465    3333    4508    5455
River Rch & RM=UNT 1016 IN LATR,Reach-1         ,2659
    1465    2182    2820    2667    3606    4877    5917
River Rch & RM=UNT 1016 IN LATR,Reach-1         ,2273
    1465    2182    2820    2667    3606    4877    5917
Boundary for River Rch & Prof#=UNT 1016 IN LATR,Reach-1         , 1
Up Type= 0
Dn Type= 3
Dn Slope=0.005
Boundary for River Rch & Prof#=UNT 1016 IN LATR,Reach-1         , 2
Up Type= 0
Dn Type= 3
Dn Slope=0.005
Boundary for River Rch & Prof#=UNT 1016 IN LATR,Reach-1         , 3
Up Type= 0
Dn Type= 3
Dn Slope=0.005
Boundary for River Rch & Prof#=UNT 1016 IN LATR,Reach-1         , 4
Up Type= 0
Dn Type= 3
Dn Slope=0.005
Boundary for River Rch & Prof#=UNT 1016 IN LATR,Reach-1         , 5
Up Type= 0
Dn Type= 3
Dn Slope=0.005
Boundary for River Rch & Prof#=UNT 1016 IN LATR,Reach-1         , 6
Up Type= 0
Dn Type= 3
Dn Slope=0.005
Boundary for River Rch & Prof#=UNT 1016 IN LATR,Reach-1         , 7
Up Type= 0
Dn Type= 3
Dn Slope=0.005
DSS Import GetInterval= 0
DSS Import GetPeak= 0
DSS Import FillOption= 0

--- UNT 1016 IN LATR.g01 (geometry) ---

Geom Title=Existing Conditions
Program Version=4.10

River Reach=UNT 1016 IN LATR,Reach-1
Reach XY= 30
      2971613.47     10057638.73      2971791.53     10057747.41
      2972117.83     10058110.41       2972099.8     10058188.04
      2972169.24     10058298.56      2972208.93     10058522.03
       2972141.4     10058822.46      2972270.95     10059102.67
      2972388.35     10059208.75      2972413.09     10059356.53
      2972566.08     10059649.52      2972440.36     10059969.41
      2972361.97     10060796.21      2972033.03     10061273.08
      2971901.13     10061600.31      2971689.44     10061686.05
      2971610.96     10061754.59      2971453.55     10062362.78
      2971313.38     10062566.71      2970949.64     10062546.53
      2970844.78     10062576.04      2970781.55     10062655.06
      2970773.45     10062730.75      2970935.48     10063094.97
      2970942.55     10063425.35      2970312.06     10063601.18
      2970240.06     10063674.33      2970157.48      10063903.8
      2970081.16     10063978.37      2970018.47     10063983.73

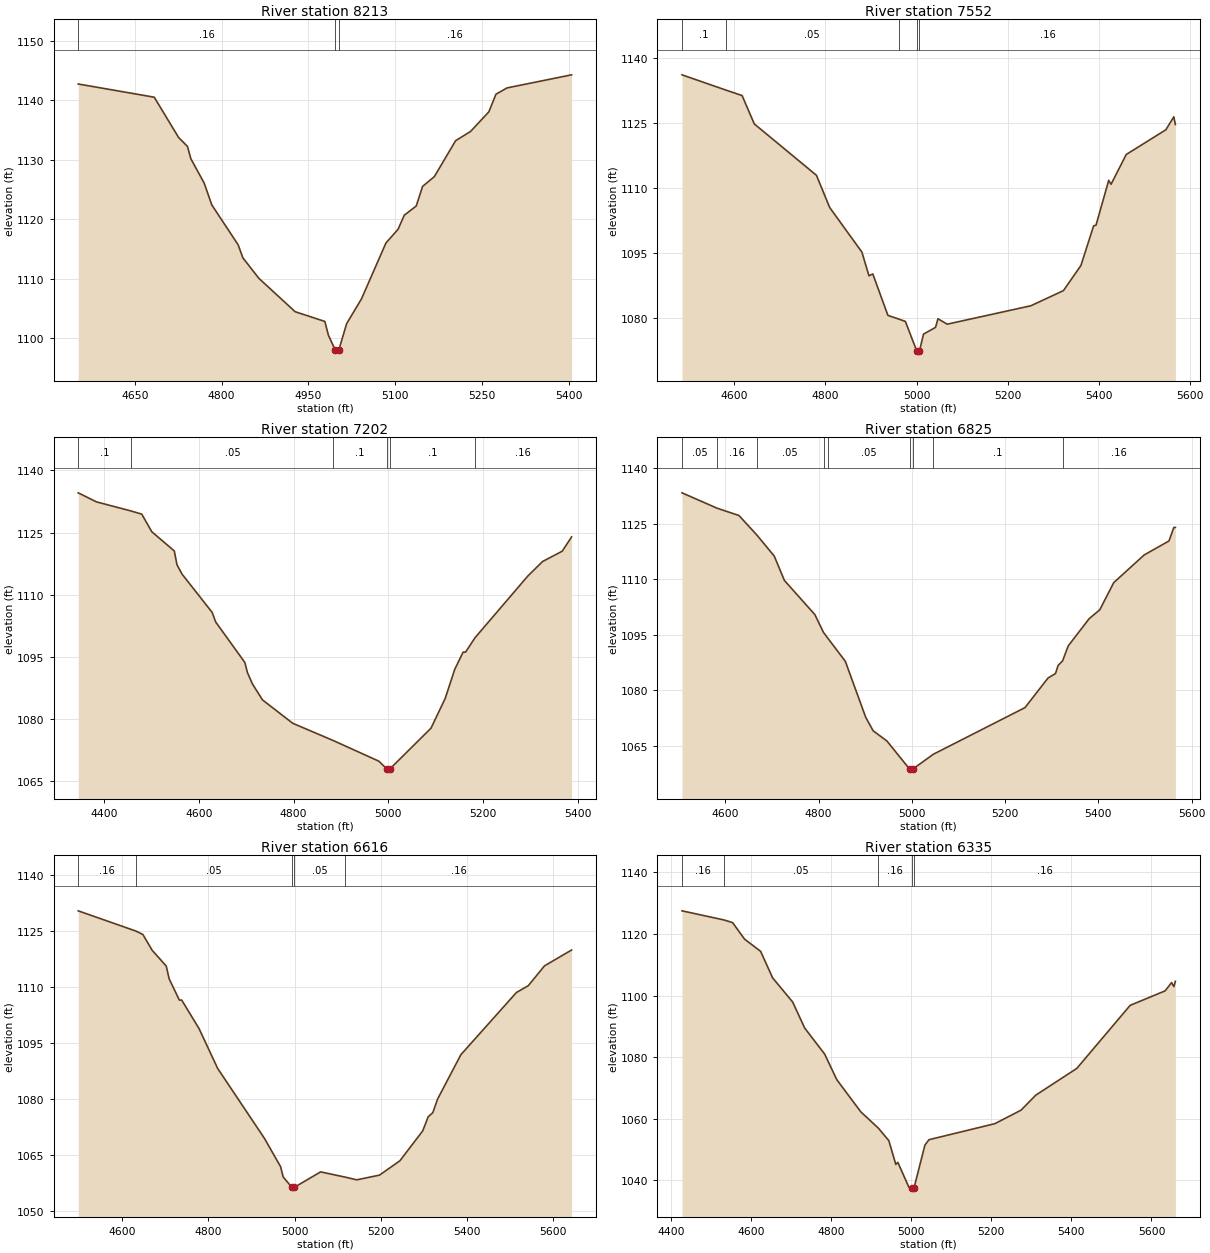
Type RM Length L Ch R = 1 ,8213    ,661,661,661
BEGIN DESCRIPTION:
UNT 1016 IN LATR 18.0
END DESCRIPTION:
XS GIS Cut Line= 3
       2971519.8     10058115.98      2971676.05      10057876.4
      2971858.34     10057339.96
#Sta/Elev= 30
  4552.3  1142.7  4683.7 1140.48  4725.9 1133.69  4741.1 1132.21    4747 1130.13
  4769.9 1126.06  4783.2 1122.37  4828.6 1115.69  4836.9 1113.48  4864.5 1110.04
  4927.2 1104.43  4978.5  1102.8  4984.7 1100.47  4996.6 1097.97  4999.3 1097.47
  5002.6 1097.97  5016.1 1102.41  5041.8 1106.59  5084.1 1115.98    5105 1118.28
  5115.8 1120.65  5136.4 1122.19  5147.4 1125.49  5167.7 1127.13  5204.4 1133.16
  5230.5 1134.74  5261.9 1138.02  5274.2 1140.98  5293.3 1142.04  5404.9 1144.24
#Mann= 3 ,-1 , 0
  4552.3     .16       0  4996.6     .07       0  5002.6     .16       0
Bank Sta=4996.6,5002.6
XS Rating Curve= 0 ,0
Exp/Cntr=0.3,0.1

Type RM Length L Ch R = 1 ,7552    ,350,350,350
BEGIN DESCRIPTION:
UNT 1016 IN LATR 17.0
END DESCRIPTION:
XS GIS Cut Line= 3
      2971597.97     10058293.06      2972004.17     10058230.57
      2972648.52     10058038.31
#Sta/Elev= 30
    4485 1136.01  4580.8 1132.52    4617 1131.23  4643.7 1124.71  4780.3 1112.86
  4809.3 1105.45  4880.1 1095.17  4895.6 1089.71    4904 1090.14  4937.2 1080.59
  4960.7 1079.76  4975.5 1079.21  5000.5  1072.4  5003.2  1071.9  5006.5  1072.4
  5015.3 1076.28  5041.8 1077.84    5047 1079.82  5067.4 1078.57  5251.1 1082.81
  5322.6  1086.3    5361 1092.09  5388.9 1101.23  5394.1 1101.36    5422  1111.7
  5427.2  1110.8  5460.4 1117.65  5547.5 1123.35    5565 1126.34  5568.4 1124.55
#Mann= 5 ,-1 , 0
    4485      .1       0  4580.8     .05       0  4960.7     .16       0
  5000.5     .07       0  5006.5     .16       0
Bank Sta=5000.5,5006.5
XS Rating Curve= 0 ,0
Exp/Cntr=0.3,0.1

Type RM Length L Ch R = 1 ,7202    ,377,377,377
BEGIN DESCRIPTION:
UNT 1016 IN LATR 16.0
END DESCRIPTION:
XS GIS Cut Line= 4
      2971582.28     10058360.77      2972035.42     10058522.24
      2972368.76     10058517.03      2972587.55     10058459.73
#Sta/Elev= 30
  4345.8  1134.6  4384.2 1132.42  4457.6 1130.21  4479.8 1129.46    4501 1125.21
  4548.5 1120.57  4554.1 1117.26  4564.7    1115  4628.4 1105.73  4635.7 1103.44
  4697.3 1093.66  4702.7 1091.23  4713.3 1088.47  4734.5 1084.63  4798.2 1078.99
  4884.2  1074.8  4979.9 1069.84  4996.9 1067.94  4999.7 1067.44  5002.9 1067.94
  5089.9 1077.81  5119.9 1085.01  5139.9 1091.99  5157.6 1096.15  5162.7 1096.15
  5182.9 1099.66  5294.3 1114.55  5325.3 1118.03  5366.7 1120.52  5386.4 1123.97
#Mann= 6 ,-1 , 0
  4345.8      .1       0  4457.6     .05       0  4884.2      .1       0
  4996.9     .07       0  5002.9      .1       0  5182.9     .16       0
Bank Sta=4996.9,5002.9
XS Rating Curve= 0 ,0
Exp/Cntr=0.3,0.1

Type RM Length L Ch R = 1 ,6825    ,490,490,490
BEGIN DESCRIPTION:
UNT 1016 IN LATR 15.0
END DESCRIPTION:
XS GIS Cut Line= 2
      2971733.36     10059115.98      2972660.44     10058605.57
#Sta/Elev= 30
  4506.8 1133.32  4582.1 1129.17    4629  1127.2  4667.4 1121.93  4704.7 1116.25
  4726.5 1109.67  4791.8 1100.46  4810.4 1095.63  4820.2 1093.99  4857.2 1087.84
  4900.8 1072.77  4916.8  1069.1  4946.4 1066.34  4995.3 1058.71    4998 1058.21
  5001.3 1058.71    5046 1062.77  5242.5 1075.35  5291.8 1083.32  5307.9 1084.55
  5313.6 1086.74  5323.1 1087.95  5335.4 1092.03  5380.2 1099.36    5403 1101.76
  5432.9 1109.09  5498.2 1116.55  5551.4 1120.33  5561.8 1123.98  5565.1 1123.98
#Mann= 9 ,-1 , 0
  4506.8     .05       0  4582.1     .16       0  4667.4     .05       0
  4810.4      .1       0  4820.2     .05       0  4995.3    .035       0
  5001.3     .05       0    5046      .1       0  5323.1     .16       0
Bank Sta=4995.3,5001.3
XS Rating Curve= 0 ,0
Exp/Cntr=0.3,0.1

Type RM Length L Ch R = 1 ,6616    ,281,281,281
BEGIN DESCRIPTION:
Mapping XS 89a3515f
END DESCRIPTION:
XS GIS Cut Line= 3
      2971790.17     10059261.36      2972652.97      10058896.8
      2972754.44      10058714.5
#Sta/Elev= 30
  4497.8 1130.48  4632.2 1125.04  4647.9 1124.15  4669.6 1119.89  4702.2 1115.69
  4708.9 1112.27  4732.6 1106.57    4738 1106.58  4778.2 1098.96  4821.6 1088.25
  4930.2 1069.52  4967.6 1061.95  4973.6  1059.2  4993.7 1056.44  4996.5 1055.94
  4999.7 1056.44  5060.5 1060.56  5118.1 1059.14  5144.4 1058.43  5197.2 1059.69
  5244.6 1063.54  5297.5 1071.54  5310.2 1075.32    5321 1076.43    5332 1080.06
  5386.1 1091.95    5515  1108.6  5542.5 1110.42  5580.2 1115.74  5643.1 1119.99
#Mann= 5 ,-1 , 0
  4497.8     .16       0  4632.2     .05       0  4993.7     .07       0
  4999.7     .05       0  5118.1     .16       0
Bank Sta=4993.7,4999.7
XS Rating Curve= 0 ,0
Exp/Cntr=0.3,0.1

Type RM Length L Ch R = 1 ,6335    ,698,698,698
BEGIN DESCRIPTION:
UNT 1016 IN LATR 14.0
END DESCRIPTION:
XS GIS Cut Line= 3
      2971832.31      10059313.9      2972608.34     10059277.45
      2972826.47     10058877.55
#Sta/Elev= 30
  4427.4 1127.52  4532.5 1124.55  4553.7 1123.71  4583.7 1118.33  4623.8 1114.37
  4653.8 1105.76  4703.9  1097.9  4733.9 1089.46  4783.9 1080.99    4814 1072.72
    4874 1062.27  4917.7 1056.99  4944.1 1052.91  4961.5 1045.18  4966.5 1045.87
  4994.2 1037.78  5001.2 1037.67  5003.9 1037.17  5007.2 1037.67  5034.2 1051.47
  5044.2 1053.21  5209.2 1058.43  5274.4 1062.82    5311 1067.67  5413.6 1076.36
  5546.8 1096.83  5634.2 1101.54  5650.3 1104.23    5656 1102.94  5659.8 1104.64
#Mann= 5 ,-1 , 0
  4427.4     .16       0  4532.5     .05       0  4917.7     .16       0
  5001.2     .07       0  5007.2     .16       0
Bank Sta=5001.2,5007.2
XS Rating Curve= 0 ,0
Exp/Cntr=0.3,0.1

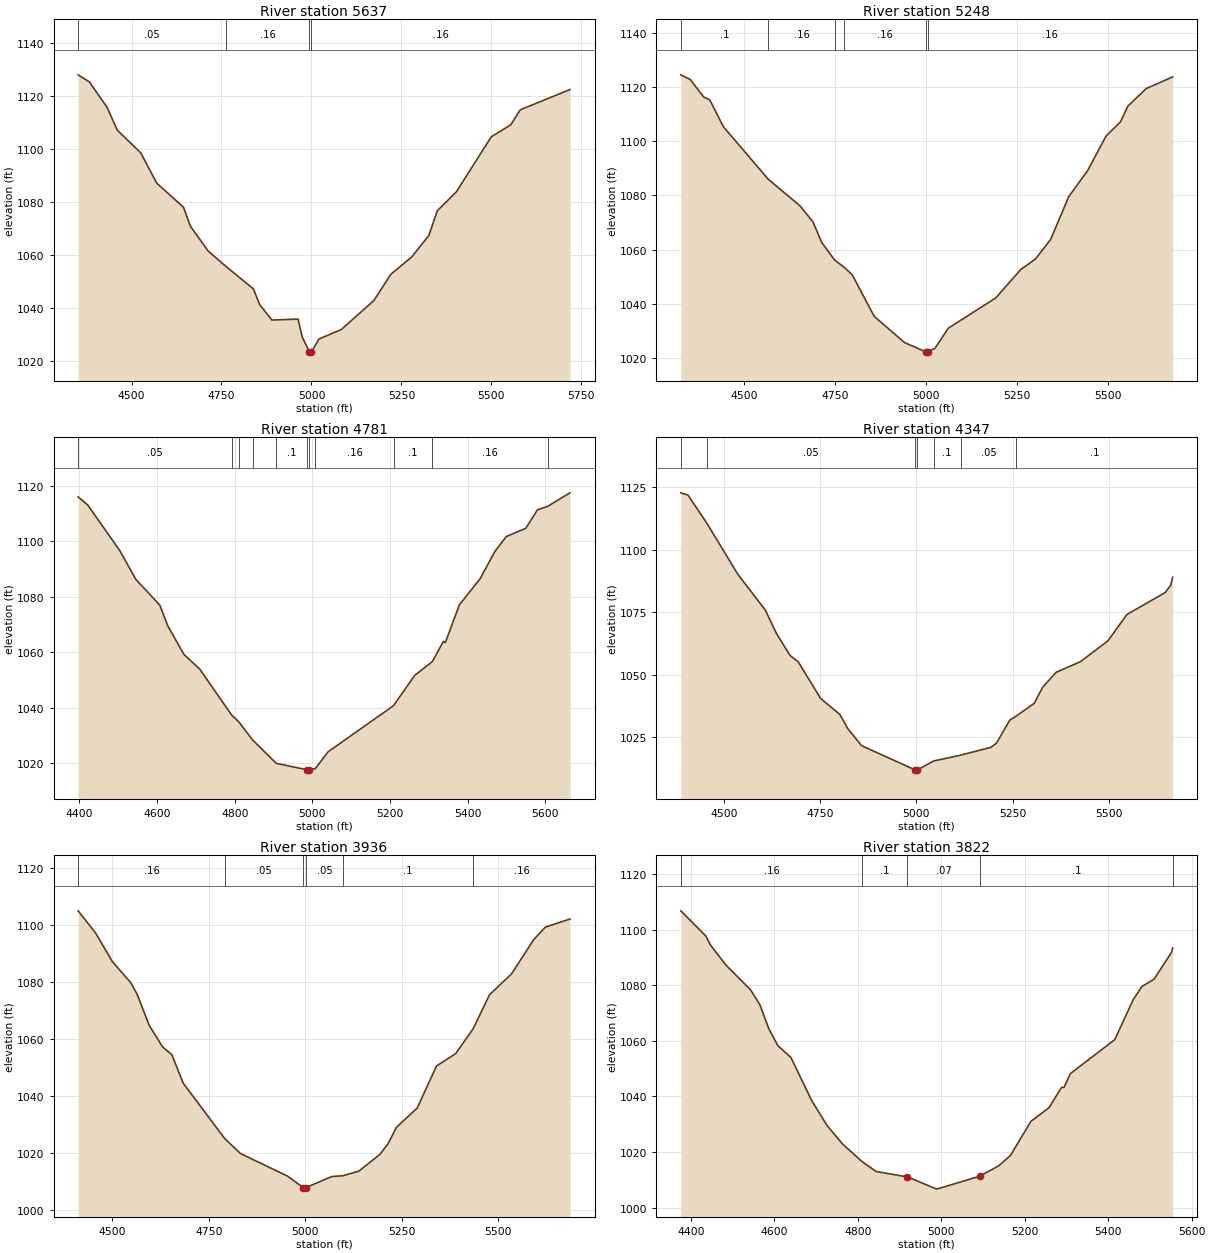
Type RM Length L Ch R = 1 ,5637    ,389,389,389
BEGIN DESCRIPTION:
UNT 1016 IN LATR 13.0
END DESCRIPTION:
XS GIS Cut Line= 4
      2971832.33     10059772.25      2972396.54     10059893.77
       2972834.9      10060080.4       2973145.4     10060119.21
#Sta/Elev= 30
  4351.7 1127.96    4383 1125.28  4432.3 1115.65  4460.3 1107.07  4525.9 1098.44
  4570.1 1087.02  4644.4 1077.94  4663.6 1070.77  4712.9 1061.38  4762.5 1055.55
  4838.8 1047.05  4855.8 1041.21  4889.9 1035.29  4962.6 1035.66  4974.4  1028.9
  4994.1 1023.29  4996.8 1022.79  5000.1 1023.29  5020.7  1028.1  5083.1 1031.72
  5173.4 1042.66  5220.6 1052.59  5278.8 1059.15    5326 1067.21  5349.7  1076.6
  5402.4 1083.71  5499.6 1104.53  5554.1 1109.11  5580.2 1114.74  5718.2  1122.4
#Mann= 4 ,-1 , 0
  4351.7     .05       0  4762.5     .16       0  4994.1     .07       0
  5000.1     .16       0
Bank Sta=4994.1,5000.1
XS Rating Curve= 0 ,0
Exp/Cntr=0.3,0.1

Type RM Length L Ch R = 1 ,5248    ,467,467,467
BEGIN DESCRIPTION:
UNT 1016 IN LATR 12.0
END DESCRIPTION:
XS GIS Cut Line= 4
       2971784.6     10060076.07      2972266.33     10060267.03
      2972800.18     10060397.24      2973080.95     10060418.84
#Sta/Elev= 30
  4327.4 1124.44  4353.1 1122.74  4389.8 1116.31  4406.9 1115.18  4443.8 1105.39
    4567    1086  4654.3 1076.18  4689.7 1070.32    4714 1062.68  4749.7 1056.13
  4775.8 1053.53  4797.7 1050.75  4858.1 1035.43  4941.4 1025.79  4999.2 1022.42
  5001.9 1021.92  5005.2 1022.42  5024.8 1023.73  5061.3 1031.11  5191.5 1042.27
  5259.5 1052.64  5300.7 1056.67  5341.9 1063.78  5391.6 1079.55  5443.5 1089.17
  5493.7 1101.85  5533.8 1107.16  5553.9 1112.94    5604 1119.37  5676.7 1123.68
#Mann= 6 ,-1 , 0
  4327.4      .1       0    4567     .16       0  4749.7      .1       0
  4775.8     .16       0  4999.2     .07       0  5005.2     .16       0
Bank Sta=4999.2,5005.2
XS Rating Curve= 0 ,0
Exp/Cntr=0.3,0.1

Type RM Length L Ch R = 1 ,4781    ,434,434,434
BEGIN DESCRIPTION:
UNT 1016 IN LATR 11.0
END DESCRIPTION:
XS GIS Cut Line= 3
      2971784.55     10060614.25      2972635.25     10060831.27
      2973021.58     10060874.67
#Sta/Elev= 30
  4396.7 1115.94  4421.4 1113.01  4503.9 1096.59  4545.2 1086.23  4607.1 1076.92
  4627.8 1069.39  4669.1 1059.19  4710.3  1053.8    4792 1037.33  4809.9 1034.97
  4845.8 1028.38  4906.9 1019.91    4986  1017.6  4988.7  1017.1    4992  1017.6
  5007.6 1018.02  5040.6 1024.08  5209.1  1040.7  5263.4 1051.58  5309.2 1056.61
  5337.4 1063.84  5342.4 1063.41  5378.5 1076.99  5432.5 1086.52  5469.1 1096.07
  5499.3 1101.61  5549.6 1104.62  5579.8 1111.28  5605.6 1112.48  5663.4 1117.39
#Mann= 11 ,-1 , 0
  4396.7     .05       0    4792      .1       0  4809.9     .16       0
  4845.8     .05       0  4906.9      .1       0    4986     .07       0
    4992      .1       0  5007.6     .16       0  5209.1      .1       0
  5309.2     .16       0  5605.6     .05       0
Bank Sta=4986,4992
XS Rating Curve= 0 ,0
Exp/Cntr=0.3,0.1

Type RM Length L Ch R = 1 ,4347    ,411,411,411
BEGIN DESCRIPTION:
UNT 1016 IN LATR 10.0
END DESCRIPTION:
XS GIS Cut Line= 3
      2971654.39     10060770.53      2972301.05     10061243.59
      2972660.33     10061559.59
#Sta/Elev= 30
    4387 1122.73  4405.8 1121.81  4454.9 1110.53  4535.5  1090.1  4606.5  1075.9
  4635.8 1066.47  4671.4 1057.62  4692.2 1055.16  4750.9 1040.44  4800.9 1034.08
  4821.9 1028.29  4857.4 1021.58  4996.5  1011.9  4999.3  1011.4  5002.5  1011.9
  5044.6 1015.45    5115 1017.78  5193.7 1020.93    5208 1022.53  5243.1 1031.85
  5259.1 1033.35  5306.7 1038.56  5328.5    1045  5363.6 1050.94  5427.1 1055.21
  5498.3 1063.52  5547.6 1074.05  5647.3 1082.85  5661.5 1085.75  5666.7 1088.94
#Mann= 7 ,-1 , 0
    4387      .1       0  4454.9     .05       0  4996.5    .035       0
  5002.5     .05       0  5044.6      .1       0    5115     .05       0
  5259.1      .1       0
Bank Sta=4996.5,5002.5
XS Rating Curve= 0 ,0
Exp/Cntr=0.3,0.1

Type RM Length L Ch R = 1 ,3936    ,617,617,617
BEGIN DESCRIPTION:
UNT 1016 IN LATR 9.0
END DESCRIPTION:
XS GIS Cut Line= 3
      2971406.92      10061256.6      2972201.22     10061586.47
      2972548.44     10061812.16
#Sta/Elev= 30
  4411.4 1104.93  4456.4 1097.21  4500.1 1087.12  4547.9 1079.67  4564.7  1075.5
  4595.6 1064.71  4630.3 1057.18  4654.2 1054.44  4683.8 1044.42    4791 1025.03
    4832 1019.75  4954.5 1011.79  4994.8 1007.76  4997.5 1007.26  5000.8 1007.76
  5068.5 1011.68  5097.7 1011.97  5138.6 1013.57  5192.7 1019.39  5214.4 1023.18
    5236 1028.95    5290 1035.74  5339.8 1050.45  5389.6 1054.83  5434.5 1063.48
  5477.2 1075.46  5534.5 1082.85  5591.9 1094.87  5622.1 1099.23  5685.6 1102.06
#Mann= 6 ,-1 , 0
  4411.4     .16       0    4791     .05       0  4994.8    .035       0
  5000.8     .05       0  5097.7      .1       0  5434.5     .16       0
Bank Sta=4994.8,5000.8
XS Rating Curve= 0 ,0
Exp/Cntr=0.3,0.1

Type RM Length L Ch R = 1 ,3822    ,62,62,62
BEGIN DESCRIPTION:
Mapping XS 9636fba3
END DESCRIPTION:
XS GIS Cut Line= 3
      2971366.63     10061276.41      2971996.87     10061637.11
      2972364.43     10061900.77
#Sta/Elev= 30
    4376 1106.76  4435.5 1097.78  4447.2 1094.41  4484.4 1087.21  4543.5 1078.27
    4565 1073.12  4586.6 1064.45  4608.5 1058.28  4639.9 1054.01  4689.2 1038.62
  4726.2 1029.58  4763.6  1022.9  4809.9 1016.62  4844.2    1013  4919.1 1011.07
  4989.3 1006.68  5092.5 1011.34  5137.1 1015.03  5165.6 1018.74  5214.9 1031.06
  5258.6 1036.02  5288.1 1043.25  5294.3 1043.27    5309 1048.16  5415.8 1060.45
    5460 1074.82  5480.9 1079.55  5510.2 1082.22  5552.2 1091.94  5554.5 1093.35
#Mann= 5 ,-1 , 0
    4376     .16       0  4809.9      .1       0  4919.1     .07       0
  5092.5      .1       0  5554.5     .16       0
Bank Sta=4919.1,5092.5
XS Rating Curve= 0 ,0
Exp/Cntr=0.3,0.1

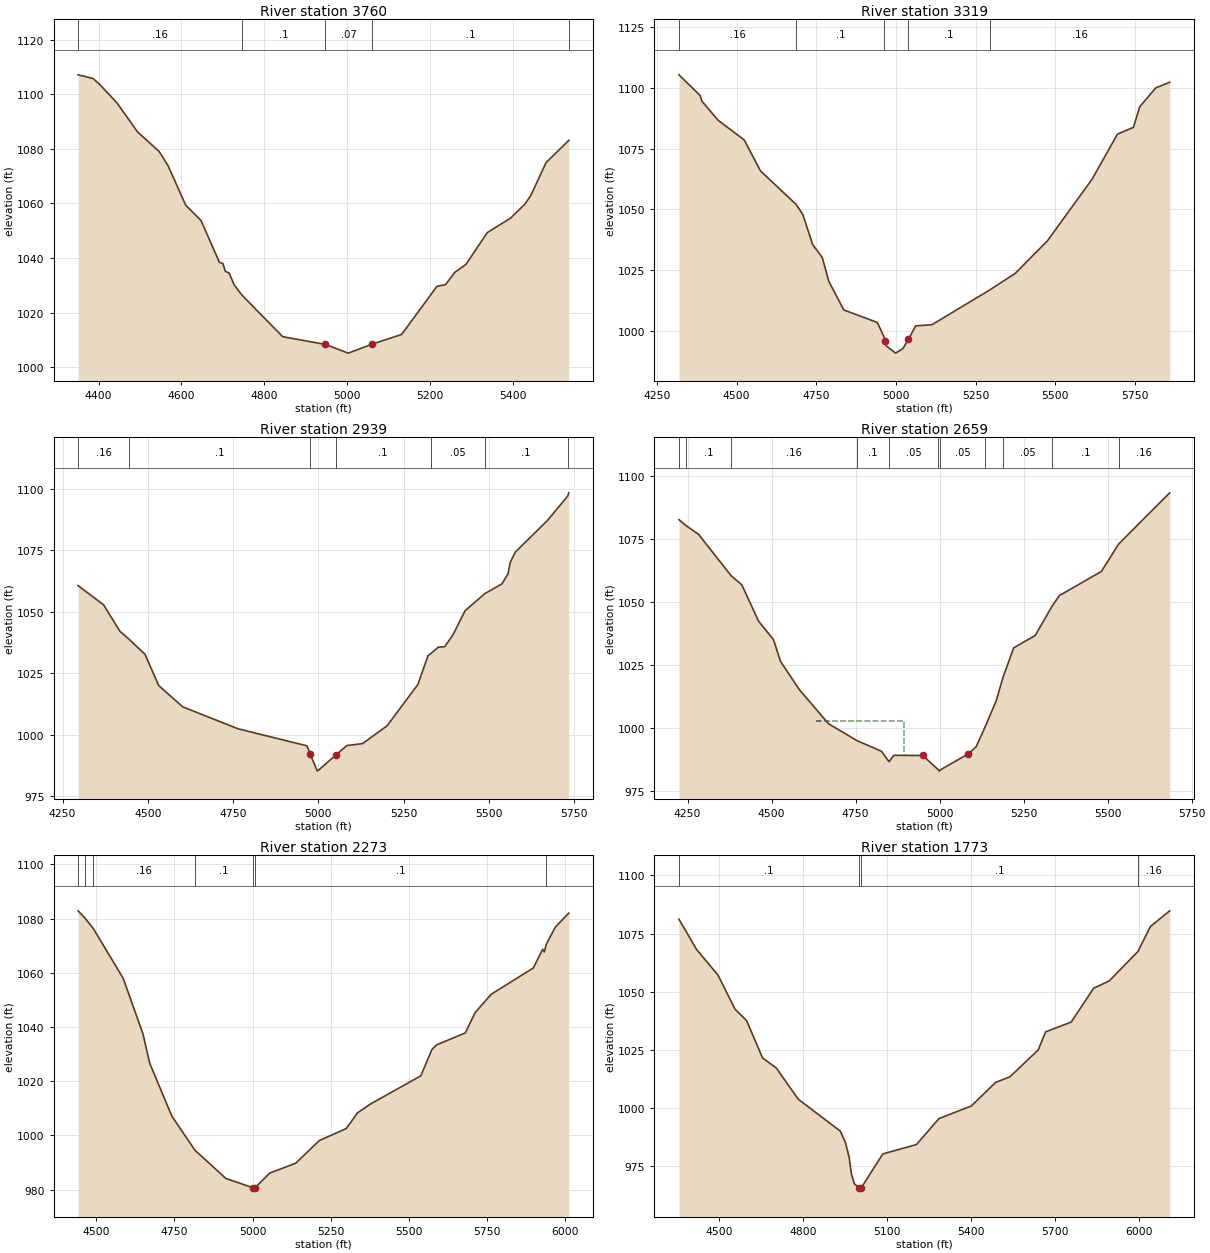
Type RM Length L Ch R = 1 ,3760    ,441,441,441
BEGIN DESCRIPTION:
Mapping XS 742aab69
END DESCRIPTION:
XS GIS Cut Line= 3
      2971314.61     10061289.47      2971801.55     10061577.21
      2972280.96     10061969.57
#Sta/Elev= 30
  4350.5 1107.07  4386.2 1105.76  4401.4 1103.78  4444.7 1096.73  4494.4 1086.12
  4546.1 1079.03  4567.6 1073.87  4610.5 1059.31  4647.5  1053.7  4691.8  1038.4
  4700.3 1037.95  4706.1  1035.1  4715.1 1034.52  4727.5 1030.13    4746 1026.43
  4844.6 1011.16  4947.3 1008.34    5003 1005.14  5060.7 1008.44  5131.8 1011.97
  5217.1 1029.59    5238 1030.25  5260.2 1034.72  5287.5 1037.69  5338.5 1049.27
  5394.4 1054.53  5429.6 1059.73    5444 1062.95  5480.6  1074.9  5535.6 1083.08
#Mann= 5 ,-1 , 0
  4350.5     .16       0    4746      .1       0  4947.3     .07       0
  5060.7      .1       0  5535.6      .1       0
Bank Sta=4947.3,5060.7
XS Rating Curve= 0 ,0
Exp/Cntr=0.3,0.1

Type RM Length L Ch R = 1 ,3319    ,380,380,380
BEGIN DESCRIPTION:
UNT 1016 IN LATR 8.0
END DESCRIPTION:
XS GIS Cut Line= 4
      2971320.15     10061313.07      2971424.31     10061820.85
      2971927.79     10062059.56      2972392.22      10062063.9
#Sta/Elev= 30
    4319 1105.34  4385.6 1096.83  4391.1 1094.47  4442.2 1086.62  4523.8 1078.56
  4574.9 1065.82  4687.3 1051.95  4707.6 1047.94  4738.5 1035.55  4768.8 1030.17
  4789.2 1020.43  4836.3 1008.62  4941.5 1003.47  4963.7  997.19    4965  995.94
  4970.8  993.69  4998.9  990.85  5021.8  992.72    5039  996.52  5061.8 1002.06
  5112.8 1002.53  5294.7 1016.87    5374 1023.63  5475.2 1037.02  5615.2 1062.36
  5695.2 1080.95  5745.2 1083.74  5765.2 1092.22  5815.2 1099.96    5859 1102.29
#Mann= 5 ,-1 , 0
    4319     .16       0  4687.3      .1       0  4963.7     .09       0
    5039      .1       0  5294.7     .16       0
Bank Sta=4965,5039
XS Rating Curve= 0 ,0
Exp/Cntr=0.3,0.1

Type RM Length L Ch R = 1 ,2939    ,280,280,280
BEGIN DESCRIPTION:
UNT 1016 IN LATR 7.0
END DESCRIPTION:
XS GIS Cut Line= 3
      2971274.68     10061619.97      2971364.83     10062214.41
      2972144.31     10062521.13
#Sta/Elev= 30
  4295.4 1060.64    4370 1052.85  4418.1 1042.05  4445.3 1038.76  4491.9 1032.61
  4531.8 1019.94  4602.6 1011.24  4764.5 1002.34  4966.7  995.39  4975.8  992.04
    4997   985.1    5051  991.61  5083.2  995.49  5129.3  996.31  5201.4 1003.55
  5291.8 1020.39  5321.6 1032.16  5328.9 1032.88  5351.9 1035.59  5370.4 1035.75
  5394.8 1040.64  5429.9 1050.38  5487.7 1057.34  5538.3 1061.37  5556.1  1065.5
  5562.7 1070.13  5577.6 1074.31    5671 1087.07    5731 1097.09  5734.3 1098.42
#Mann= 7 ,-1 , 0
  4295.4     .16       0  4445.3      .1       0  4975.8     .07       0
    5051      .1       0  5328.9     .05       0  5487.7      .1       0
    5731     .16       0
Bank Sta=4975.8,5051
XS Rating Curve= 0 ,0
Exp/Cntr=0.3,0.1

Type RM Length L Ch R = 1 ,2659    ,386,386,386
BEGIN DESCRIPTION:
UNT 1016 IN LATR 6.0
END DESCRIPTION:
XS GIS Cut Line= 3
      2970725.49      10062055.2      2971489.42     10062593.42
      2971992.91     10062745.34
#Sta/Elev= 30
  4224.2 1082.56  4245.2 1080.22  4282.7 1076.73  4379.3 1060.37  4411.3 1056.74
  4461.2 1042.32  4505.6 1035.02  4526.5 1026.38  4583.1 1015.11  4669.4 1001.68
  4754.4  994.97  4827.2  990.75  4849.3  986.65  4863.9  989.17  4949.6   989.1
  4996.4   983.4  4999.2   982.9  5002.4   983.4  5085.7  989.79  5108.6  992.57
  5134.2 1000.08  5168.1 1010.71  5188.8 1020.17  5220.4 1031.75  5284.6 1036.69
  5335.7 1048.51  5356.2 1052.47  5481.5 1062.06  5532.5 1072.87  5684.6  1093.2
#Mann= 11 ,-1 , 0
  4224.2     .16       0  4245.2      .1       0  4379.3     .16       0
  4754.4      .1       0  4849.3     .05       0  4996.4    .035       0
  5002.4     .05       0  5134.2      .1       0  5188.8     .05       0
  5335.7      .1       0  5532.5     .16       0
#XS Ineff= 1 ,-1
 4630.91 4894.55 1002.83
Permanent Ineff=
       F
Bank Sta=4949.6,5085.7
XS Rating Curve= 0 ,0
Exp/Cntr=0.3,0.1

Type RM Length L Ch R = 1 ,2273    ,500,500,500
BEGIN DESCRIPTION:
UNT 1016 IN LATR 5.0
END DESCRIPTION:
XS GIS Cut Line= 4
      2970725.55     10062102.99      2971007.65     10062402.45
      2971020.67     10062662.86      2971888.76     10062888.57
#Sta/Elev= 30
  4442.2 1082.89  4463.9 1080.26  4491.4 1076.25  4586.2 1058.03  4649.7 1037.45
  4671.2 1026.64    4742 1007.09  4816.2  994.46    4915  984.07  5002.1  980.64
  5004.8  980.14  5008.1  980.64  5055.1  986.08  5137.8  989.68  5213.7  998.09
  5299.9 1002.52  5335.3 1008.26  5375.8 1011.48    5538 1021.96  5573.3  1031.6
  5587.4 1033.34  5680.4 1037.82  5711.4 1045.26    5763 1052.08  5897.6 1061.78
  5927.8 1068.69    5933 1067.71    5939 1070.49  5968.4 1076.91  6011.3 1082.04
#Mann= 7 ,-1 , 0
  4442.2     .16       0  4463.9      .1       0  4491.4     .16       0
  4816.2      .1       0  5002.1     .07       0  5008.1      .1       0
    5939     .16       0
Bank Sta=5002.1,5008.1
XS Rating Curve= 0 ,0
Exp/Cntr=0.3,0.1

Type RM Length L Ch R = 1 ,1773    ,315,315,315
BEGIN DESCRIPTION:
UNT 1016 IN LATR 4.0
END DESCRIPTION:
XS GIS Cut Line= 4
       2970222.1     10062845.16      2970621.36     10062931.96
      2971107.47     10062767.03      2971923.46     10062931.96
#Sta/Elev= 30
  4355.2 1081.17  4418.5 1068.09  4494.7 1057.15  4555.7 1042.47  4597.1 1037.59
  4653.9 1021.56    4703 1017.25  4781.8  1003.8  4932.2  990.07  4950.8  985.04
  4963.6  978.88  4971.9   971.6  4982.5  967.43  5000.6  965.65  5003.4  965.15
  5006.6  965.65  5083.9  980.28  5204.2   984.3  5284.5  995.45  5400.6  1000.9
  5487.4 1011.03  5538.2 1013.39  5639.7 1024.98  5665.8 1032.71  5757.6 1036.94
  5837.5 1051.48  5893.4 1054.61  5996.1 1067.29  6040.5 1077.97  6109.6 1084.75
#Mann= 4 ,-1 , 0
  4355.2      .1       0  5000.6     .07       0  5006.6      .1       0
  5996.1     .16       0
Bank Sta=5000.6,5006.6
XS Rating Curve= 0 ,0
Exp/Cntr=0.3,0.1

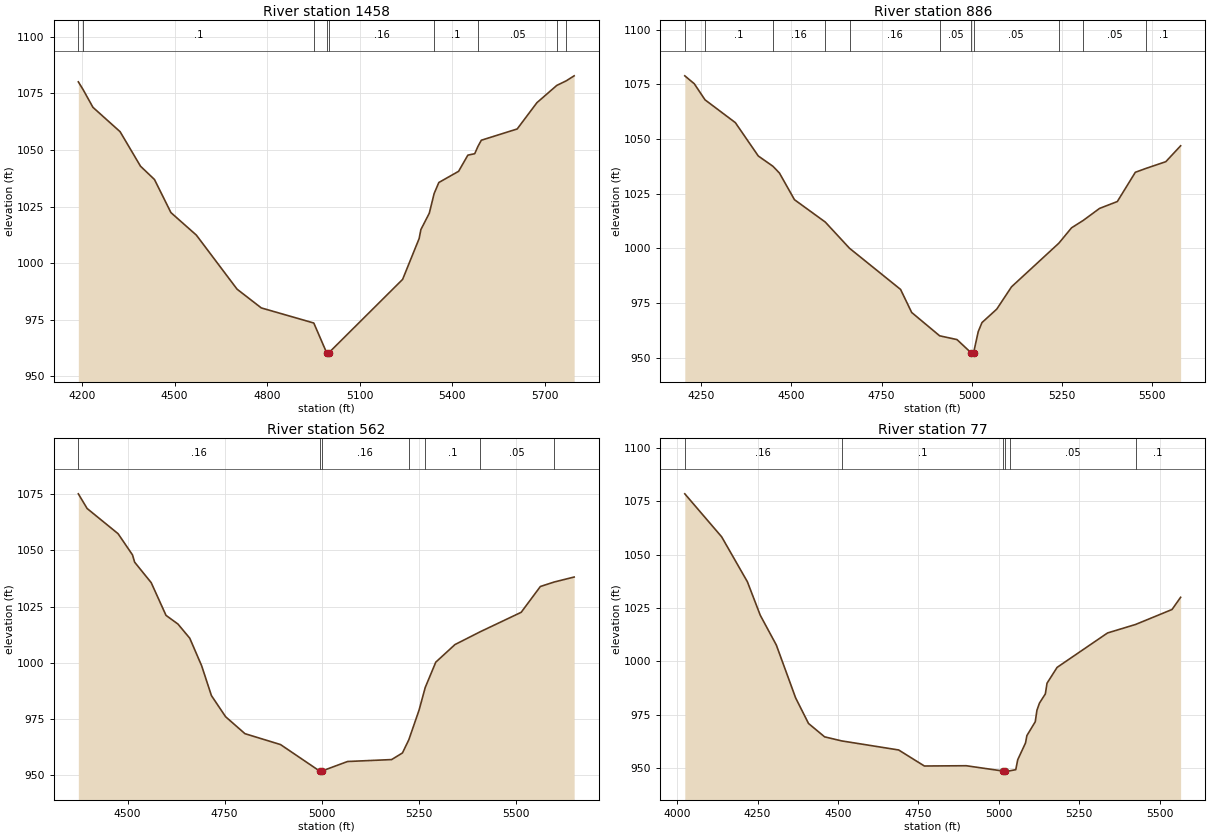
Type RM Length L Ch R = 1 ,1458    ,572,572,572
BEGIN DESCRIPTION:
UNT 1016 IN LATR 3.0
END DESCRIPTION:
XS GIS Cut Line= 4
      2970200.31     10062897.22      2970725.53     10063175.02
      2971233.34     10063122.93      2971663.05     10063383.36
#Sta/Elev= 30
  4188.2 1080.13  4203.4 1076.77  4235.6 1068.86  4323.6 1058.09  4389.7 1042.85
    4435 1036.96  4488.4 1022.32  4570.7 1012.39  4702.8  988.47  4781.2   980.2
  4951.4  973.52  4993.4  960.27  4996.2  959.77  4999.4  960.27  5239.3  992.81
  5292.8 1010.84  5298.5 1014.82  5325.7 1022.04  5341.5 1030.77  5356.7 1035.63
  5420.7 1040.58  5450.8 1047.73    5473 1048.36  5483.5 1051.61  5494.4 1054.32
  5610.7  1059.3  5674.7 1070.93  5739.1 1078.56  5769.4 1080.56  5795.3 1082.79
#Mann= 9 ,-1 , 0
  4188.2     .16       0  4203.4      .1       0  4951.4     .16       0
  4993.4     .07       0  4999.4     .16       0  5341.5      .1       0
  5483.5     .05       0  5739.1      .1       0  5769.4     .05       0
Bank Sta=4993.4,4999.4
XS Rating Curve= 0 ,0
Exp/Cntr=0.3,0.1

Type RM Length L Ch R = 1 ,886     ,324,324,324
BEGIN DESCRIPTION:
UNT 1016 IN LATR 2.0
END DESCRIPTION:
XS GIS Cut Line= 4
      2970165.63     10062940.64      2970608.34     10063266.16
      2970712.51     10063721.89      2970954.48     10063985.47
#Sta/Elev= 30
  4204.2 1078.85  4230.5 1075.23  4260.3 1067.87  4344.3 1057.46    4408 1042.18
  4448.6 1037.49  4466.6 1034.39  4508.3  1022.2  4593.7 1011.97  4660.9  999.99
  4802.5  981.16  4833.3  970.62  4910.8  959.95  4958.9  958.22  4998.8  952.07
  5001.6  951.57  5004.8  952.07  5017.9   961.9  5028.2  965.99  5069.2  972.16
  5110.2  982.37  5241.4 1002.31  5276.5 1009.33  5308.7 1012.69  5354.2 1018.21
  5403.5 1021.36  5453.4 1034.73  5482.9 1036.51  5537.9 1039.58    5579 1046.85
#Mann= 11 ,-1 , 0
  4204.2     .16       0  4260.3      .1       0  4448.6     .16       0
  4593.7      .1       0  4660.9     .16       0  4910.8     .05       0
  4998.8    .035       0  5004.8     .05       0  5241.4      .1       0
  5308.7     .05       0  5482.9      .1       0
Bank Sta=4998.8,5004.8
XS Rating Curve= 0 ,0
Exp/Cntr=0.3,0.1

Type RM Length L Ch R = 1 ,562     ,485,485,485
BEGIN DESCRIPTION:
Mapping XS 44f96279
END DESCRIPTION:
XS GIS Cut Line= 3
      2970135.62     10062997.52       2970399.5     10063719.72
      2970788.39     10064046.11
#Sta/Elev= 30
  4373.4 1075.08  4396.1 1068.55  4475.8 1057.35  4512.9 1047.93  4518.4  1044.7
    4561 1035.61  4599.2 1021.05  4629.8 1017.22  4660.3 1010.91  4690.9  998.66
  4716.1   985.4  4752.6  976.01  4802.4  968.48    4894  963.64  4994.5  951.89
  4997.3  951.39  5000.5  951.89  5066.6  956.11  5180.1  956.97  5207.9  959.91
  5224.3  965.77  5250.8  979.01  5266.6  989.03  5293.7 1000.26  5343.1 1008.08
  5408.2 1013.78  5513.6 1022.42    5563 1033.89  5598.3 1035.87    5650  1038.1
#Mann= 7 ,-1 , 0
  4373.4     .16       0  4994.5     .07       0  5000.5     .16       0
  5224.3     .05       0  5266.6      .1       0  5408.2     .05       0
  5598.3      .1       0
Bank Sta=4994.5,5000.5
XS Rating Curve= 0 ,0
Exp/Cntr=0.3,0.1

Type RM Length L Ch R = 1 ,77      ,0,0,0
BEGIN DESCRIPTION:
UNT 1016 IN LATR 1.0
END DESCRIPTION:
XS GIS Cut Line= 4
      2970054.02     10062999.27      2970073.11     10063941.94
      2970135.61     10064037.43      2970593.74     10064193.61
#Sta/Elev= 30
  4023.9 1078.49  4138.4 1058.34  4218.4 1037.27  4258.4 1021.57  4308.4 1007.58
  4368.4  982.79  4408.4  970.81  4458.4  964.54  4511.1  962.64  4688.5  958.38
  4768.5  950.86  4898.5  950.99  5013.5  948.49  5016.2  947.99  5019.5  948.49
  5033.5  948.59  5052.6  949.14  5058.6   953.8  5082.9  961.68  5087.1  965.12
  5113.1  971.61  5118.4  977.05  5126.2  980.36  5144.5  984.68  5149.7  989.69
  5181.1  997.12  5337.8 1013.25  5424.7 1017.22  5538.2 1024.25  5564.9 1029.97
#Mann= 6 ,-1 , 0
  4023.9     .16       0  4511.1      .1       0  5013.5     .07       0
  5019.5      .1       0  5033.5     .05       0  5424.7      .1       0
Bank Sta=5013.5,5019.5
XS Rating Curve= 0 ,0
Exp/Cntr=0.3,0.1

Chan Stop Cuts=-1
Use User Specified Reach Order=0
Composite Channel Slope=5