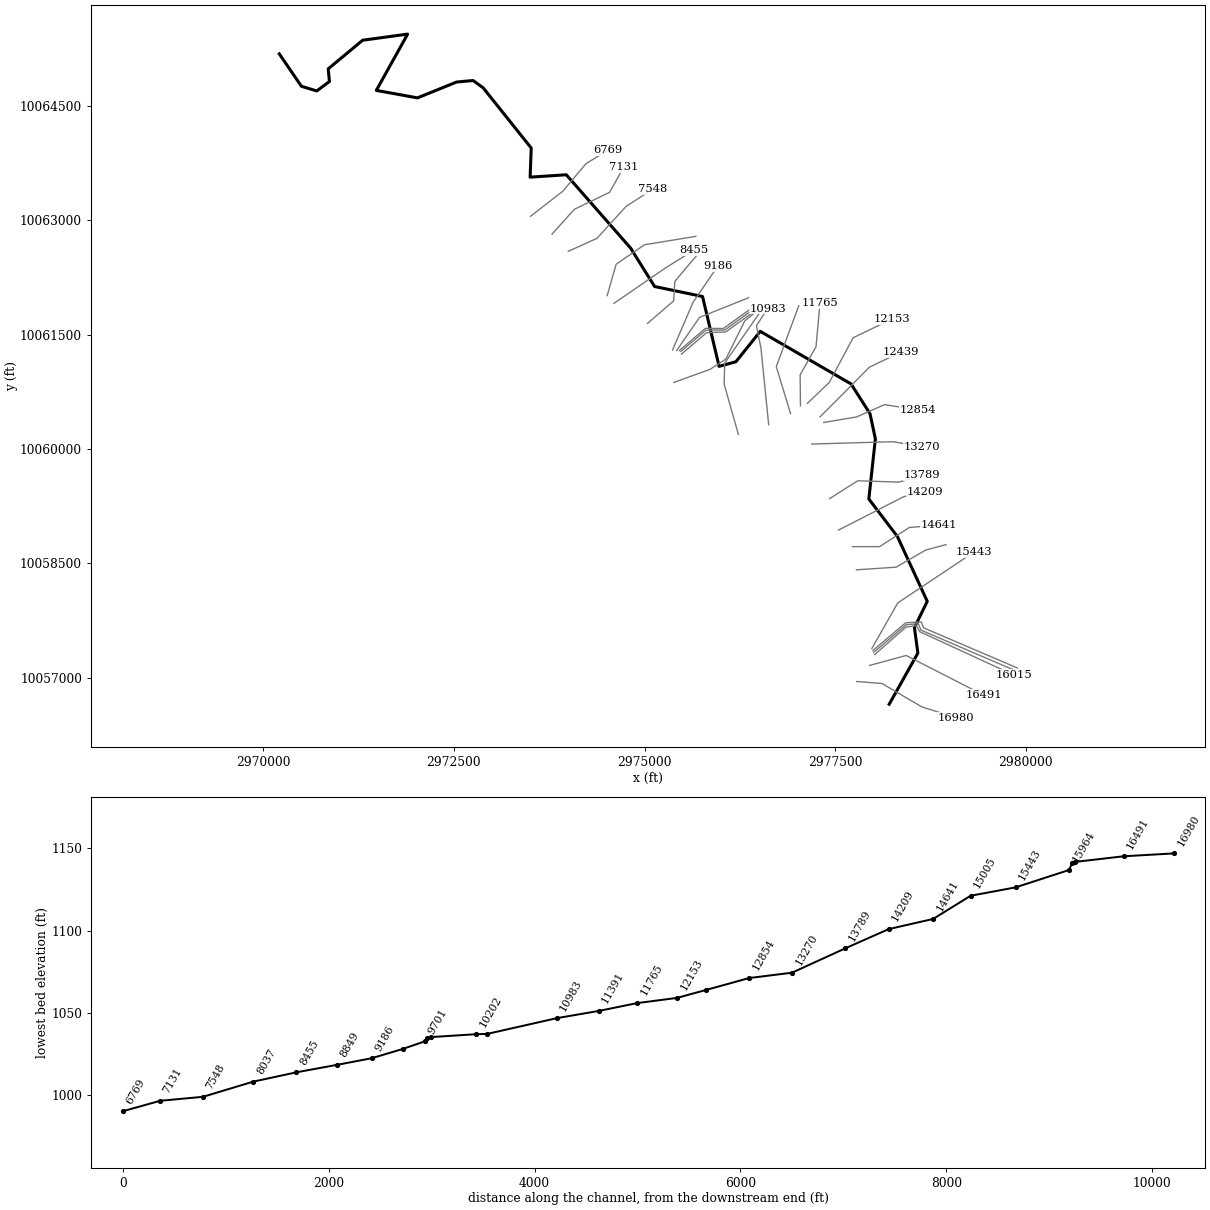
--- UNT 1018 IN LATR.prj (project) ---

Proj Title=UNT 1018 IN LATR Base Level Engineering
Current Plan=p01
Default Exp/Contr=0.3,0.1
English Units
Geom File=g01
Flow File=f01
Plan File=p01
Y Axis Title=Elevation
X Axis Title(PF)=Main Channel Distance
X Axis Title(XS)=Station
BEGIN DESCRIPTION:
UNT 1018 IN LATR
END DESCRIPTION:
DSS Export Rating Curves= 0
DSS Export Rating Curve Sorted= 0
DSS Export Volume Flow Curves= 0
DXF OffsetX= 0
DXF OffsetY= 0
DXF ScaleX= 1
DXF ScaleY= 10

--- UNT 1018 IN LATR.p01 (plan) ---

Plan Title=Multiple Run
Short Identifier=Multiple
Geom File=g01
Flow File=f01
Subcritical Flow
K Sum by GR= 0
Std Step Tol= 0.01
Critical Tol= 0.01
Num of Std Step Trials= 20
Max Error Tol= 0.3
Flow Tol Ratio= 0.001
Split Flow NTrial= 30
Split Flow Tol= 0.02
Split Flow Ratio= 0.02
Log Output Level= 0
Friction Slope Method= 1
Unsteady Friction Slope Method= 2
Unsteady Bridges Friction Slope Method= 1
Parabolic Critical Depth
Global Vel Dist=  1 , 1 , 1
Global Log Level= 0
CheckData=True
Encroach Param= -1, 0, 0, 0
BEGIN DESCRIPTION:
Multiple Run
END DESCRIPTION:

--- UNT 1018 IN LATR.f01 (steady flow) ---

Flow Title=Multiple
Number of Profiles=7
Profile Names=10-year,25-year,50-year,1pct_min,100-year,1pct_plu,500-year
River Rch & RM= UNT 1018 IN LATR,Reach-1,16980
     927    1348    1715    1599    2162    2924    3448
River Rch & RM= UNT 1018 IN LATR,Reach-1,15005
    1620    2426    3148    2988    4040    5464    6681
River Rch & RM= UNT 1018 IN LATR,Reach-1,11765
    1879    2825    3674    3491    4721    6385    7828
River Rch & RM= UNT 1018 IN LATR,Reach-1,4897
    2218    3352    4376    4170    5639    7626    9405
Boundary for River Rch & Prof#=UNT 1018 IN LATR,Reach-1,1
Up Type=0
Dn Type=3
Dn Slope=0.005
Boundary for River Rch & Prof#=UNT 1018 IN LATR,Reach-1,2
Up Type=0
Dn Type=3
Dn Slope=0.005
Boundary for River Rch & Prof#=UNT 1018 IN LATR,Reach-1,3
Up Type=0
Dn Type=3
Dn Slope=0.005
Boundary for River Rch & Prof#=UNT 1018 IN LATR,Reach-1,4
Up Type=0
Dn Type=3
Dn Slope=0.005
Boundary for River Rch & Prof#=UNT 1018 IN LATR,Reach-1,5
Up Type=0
Dn Type=3
Dn Slope=0.005
Boundary for River Rch & Prof#=UNT 1018 IN LATR,Reach-1,6
Up Type=0
Dn Type=3
Dn Slope=0.005
Boundary for River Rch & Prof#=UNT 1018 IN LATR,Reach-1,7
Up Type=0
Dn Type=3
Dn Slope=0.005

--- UNT 1018 IN LATR.g01 (geometry) ---

Geom Title=Existing Conditions
Program Version=4.10

River Reach=UNT 1018 IN LATR,Reach-1
Reach XY= 30
      2978208.47     10056653.73      2978584.45     10057324.78
      2978539.18     10057658.53      2978707.55     10058003.14
       2978316.1     10058852.82       2977941.4     10059344.99
      2978027.14     10060133.17      2977957.17     10060462.27
      2977708.47     10060853.73      2976517.77     10061543.06
      2976199.01     10061144.81      2975978.12     10061084.01
       2975760.9      10062000.1      2975132.13     10062131.17
      2974819.14     10062633.18      2973974.75     10063596.23
      2973500.45     10063565.01      2973514.58      10063946.9
      2972884.64     10064735.91       2972752.6     10064832.05
      2972536.28      10064812.3      2972023.31      10064604.4
      2971483.67     10064702.39      2971894.13     10065440.52
      2971305.12     10065360.42      2970853.25     10064985.45
      2970868.74     10064818.88      2970702.73     10064695.39
      2970501.64     10064756.18       2970211.4     10065181.28

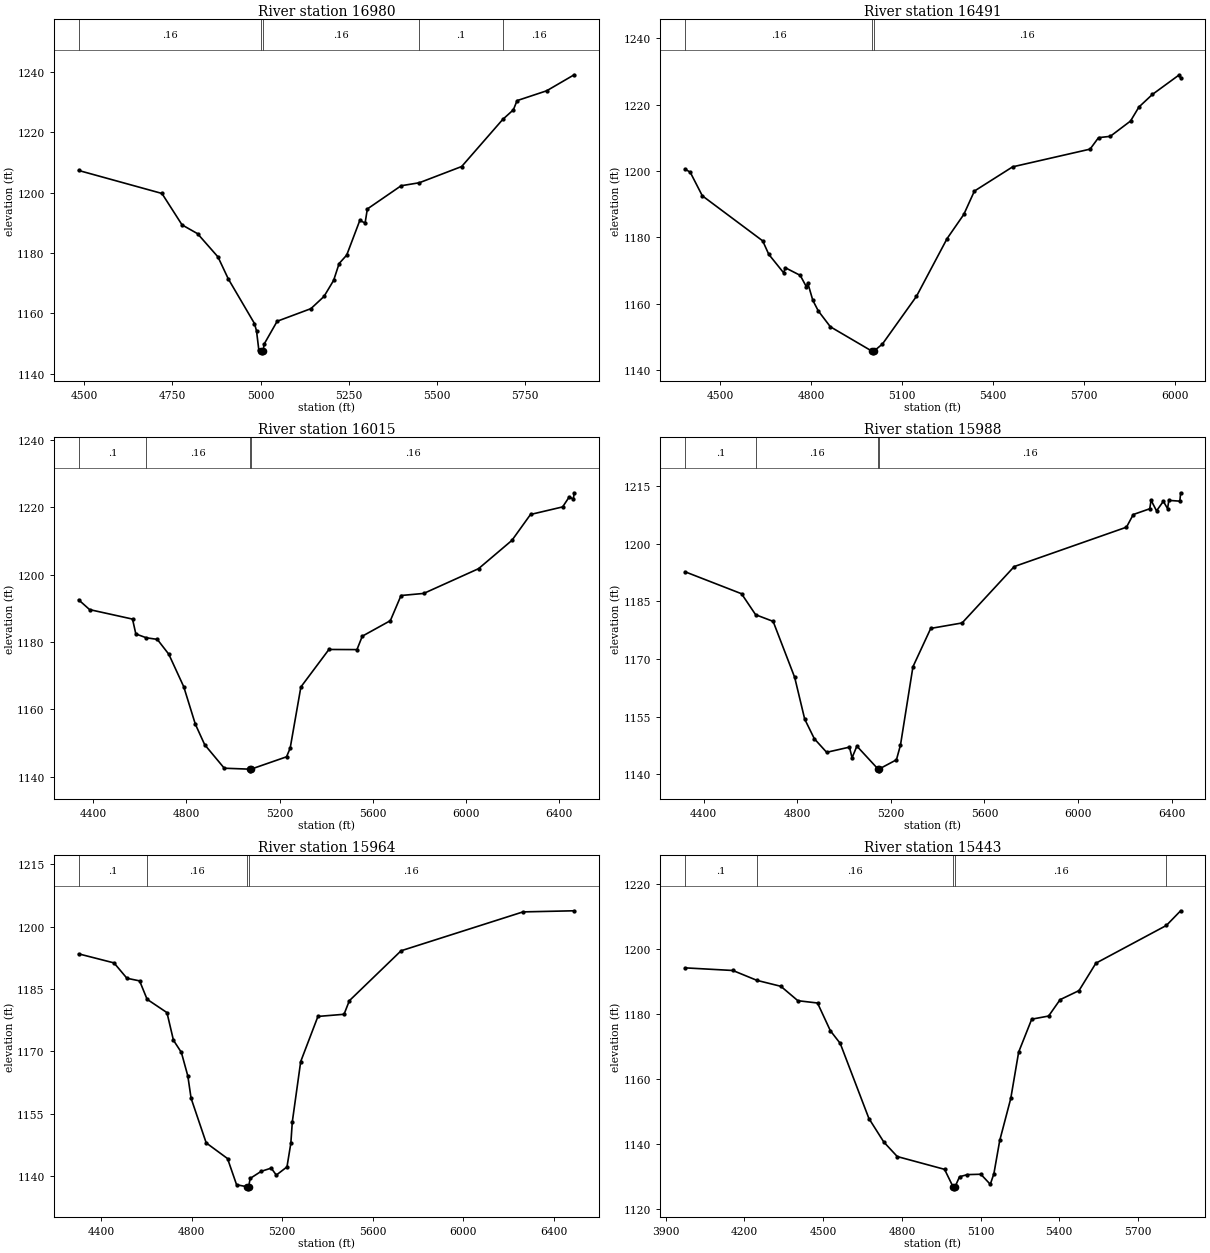
Type RM Length L Ch R = 1 ,16980   ,489,489,489
BEGIN DESCRIPTION:
UNT 1018 IN LATR 37.0
END DESCRIPTION:
XS GIS Cut Line= 4
      2977782.81     10056951.93      2978113.55     10056925.88
      2978636.99     10056618.59      2979082.98     10056478.57
#Sta/Elev= 30
  4483.9 1207.35  4720.3 1199.73  4777.4 1189.31  4821.4  1186.4  4879.3  1178.7
  4908.6 1171.41  4982.9 1156.62  4988.7 1154.17  4995.3  1147.8  5001.3 1147.41
  5004.1 1146.91  5007.3 1147.41  5010.1 1149.76  5047.3 1157.38    5143 1161.55
  5180.2  1165.6  5207.5 1170.92  5223.1 1176.51  5244.6  1179.3  5281.8 1190.79
  5296.8 1189.94  5303.2 1194.59    5399 1202.28  5450.7 1203.28  5570.9 1208.66
  5687.5 1224.28  5717.5 1227.44  5728.1  1230.5    5812 1233.75  5890.1 1239.06
#Mann= 5 ,-1 , 0
  4483.9     .16       0  5001.3     .07       0  5007.3     .16       0
  5450.7      .1       0  5687.5     .16       0
Bank Sta=5001.3,5007.3
XS Rating Curve= 0 ,0
Exp/Cntr=0.3,0.1

Type RM Length L Ch R = 1 ,16491   ,476,476,476
BEGIN DESCRIPTION:
UNT 1018 IN LATR 36.0
END DESCRIPTION:
XS GIS Cut Line= 3
      2977952.14     10057162.88      2978431.26     10057293.07
      2979443.86     10056775.06
#Sta/Elev= 30
  4384.7 1200.59  4401.6 1199.64  4441.5 1192.53  4640.5 1178.94  4660.7 1174.86
  4709.7 1169.29  4714.9 1170.84  4764.3 1168.53  4784.1 1165.17  4789.3 1166.19
  4805.8 1161.01  4823.9  1157.8  4863.7 1153.02  5000.9 1145.66  5003.6 1145.16
  5006.9 1145.66  5035.3 1147.81  5147.6 1162.21  5248.7 1179.65  5303.6  1186.9
  5338.6 1193.96  5464.7 1201.27    5720 1206.61  5747.8 1210.07  5786.6 1210.47
  5853.3 1215.08  5881.1 1219.32  5925.5 1223.11  6014.3 1229.04  6018.6 1228.06
#Mann= 3 ,-1 , 0
  4384.7     .16       0  5000.9     .07       0  5006.9     .16       0
Bank Sta=5000.9,5006.9
XS Rating Curve= 0 ,0
Exp/Cntr=0.3,0.1

Type RM Length L Ch R = 1 ,16015   ,27,27,27
BEGIN DESCRIPTION:
Mapping XS 84b04a42
END DESCRIPTION:
XS GIS Cut Line= 5
       2978019.8     10057306.09      2978428.65     10057665.47
      2978564.07      10057683.7      2978608.34     10057605.57
      2979839.13     10057038.32
#Sta/Elev= 30
  4337.6 1192.54  4384.7 1189.63  4568.8 1186.81    4583  1182.4  4627.7 1181.26
  4675.1 1180.78  4724.4 1176.37  4788.5 1166.71  4838.3 1155.57  4878.5 1149.46
  4962.5 1142.48  5071.2  1142.2    5074  1141.7  5077.2  1142.2  5229.6 1145.87
  5245.2 1148.46  5291.1 1166.63  5411.4 1177.78  5531.7 1177.74  5554.6 1181.73
  5674.9 1186.34  5720.8 1193.82  5818.1 1194.44  6053.2 1201.79  6196.5 1210.21
  6276.3 1217.91  6414.1 1220.16  6442.5 1223.14    6460 1222.46  6463.6 1224.36
#Mann= 4 ,-1 , 0
  4337.6      .1       0  4627.7     .16       0  5071.2     .07       0
  5077.2     .16       0
Bank Sta=5071.2,5077.2
XS Rating Curve= 0 ,0
Exp/Cntr=0.3,0.1

Type RM Length L Ch R = 1 ,15988   ,24,24,24
BEGIN DESCRIPTION:
Mapping XS 667b7250
END DESCRIPTION:
XS GIS Cut Line= 5
       2978006.8     10057334.76      2978431.26     10057696.72
      2978590.11     10057709.74      2978623.97      10057626.4
      2979829.01     10057108.47
#Sta/Elev= 30
  4320.1 1192.69  4561.4 1186.98  4621.7 1181.52  4696.5 1179.79  4788.7 1165.21
  4831.5 1154.35  4872.8 1149.24  4925.3 1145.72  5022.8 1147.07    5034  1144.3
  5054.6 1147.33  5144.6  1141.4  5147.3  1140.9  5150.6  1141.4  5223.7 1143.77
    5241  1147.6  5294.3 1167.98  5370.4 1177.96  5504.5 1179.38  5727.3 1194.05
  6207.3  1204.3  6236.3 1207.59  6306.9 1209.09  6312.4 1211.32  6335.9 1208.54
  6364.9 1211.03    6383 1209.13  6388.5 1211.27  6435.6 1211.07  6438.9 1213.25
#Mann= 4 ,-1 , 0
  4320.1      .1       0  4621.7     .16       0  5144.6     .07       0
  5150.6     .16       0
Bank Sta=5144.6,5150.6
XS Rating Curve= 0 ,0
Exp/Cntr=0.3,0.1

Type RM Length L Ch R = 1 ,15964   ,521,521,521
BEGIN DESCRIPTION:
UNT 1018 IN LATR 35.0
END DESCRIPTION:
XS GIS Cut Line= 5
      2977993.75     10057358.17      2978426.05     10057722.76
      2978629.17     10057733.18      2978660.42     10057655.05
      2979889.63     10057128.99
#Sta/Elev= 30
  4300.9 1193.46  4457.2 1191.28  4514.4 1187.58  4570.4 1186.95  4603.5 1182.52
  4691.3 1179.31  4719.9 1172.67    4755 1169.72  4783.6 1164.03  4797.9 1158.69
  4864.7 1147.94    4959 1144.17    4999 1137.86  5046.1 1137.38  5048.8 1136.88
  5052.1 1137.38  5059.1 1139.39  5107.6 1141.09    5152 1141.87  5174.5 1140.19
  5221.7 1142.16  5238.8 1147.87  5245.3 1153.03  5282.4 1167.53  5358.5 1178.39
  5473.9 1178.91  5497.4 1182.18    5726  1194.2  6264.8 1203.56    6491 1203.83
#Mann= 4 ,-1 , 0
  4300.9      .1       0  4603.5     .16       0  5046.1     .07       0
  5052.1     .16       0
Bank Sta=5046.1,5052.1
XS Rating Curve= 0 ,0
Exp/Cntr=0.3,0.1

Type RM Length L Ch R = 1 ,15443   ,438,438,438
BEGIN DESCRIPTION:
UNT 1018 IN LATR 34.0
END DESCRIPTION:
XS GIS Cut Line= 3
      2977980.72     10057385.06      2978321.02     10057982.31
      2979320.82     10058648.84
#Sta/Elev= 30
  3973.6  1194.3  4155.7 1193.49  4247.5 1190.45  4338.7 1188.62  4403.5 1184.19
  4478.4 1183.48  4527.4 1174.94  4564.9 1171.05  4674.3 1147.93  4731.4 1140.65
  4782.4 1136.22  4962.7 1132.28  4995.8 1126.78  4998.5 1126.28  5001.8 1126.78
  5019.8    1130  5049.8 1130.66  5100.9 1130.77    5137 1127.67  5150.7 1130.93
    5173 1141.17  5215.1 1154.12  5245.1 1168.37  5294.9  1178.5  5359.3 1179.47
  5403.1 1184.51  5475.2  1187.3  5539.6 1195.74  5808.1 1207.35  5862.6 1211.87
#Mann= 5 ,-1 , 0
  3973.6      .1       0  4247.5     .16       0  4995.8     .07       0
  5001.8     .16       0  5808.1      .1       0
Bank Sta=4995.8,5001.8
XS Rating Curve= 0 ,0
Exp/Cntr=0.3,0.1

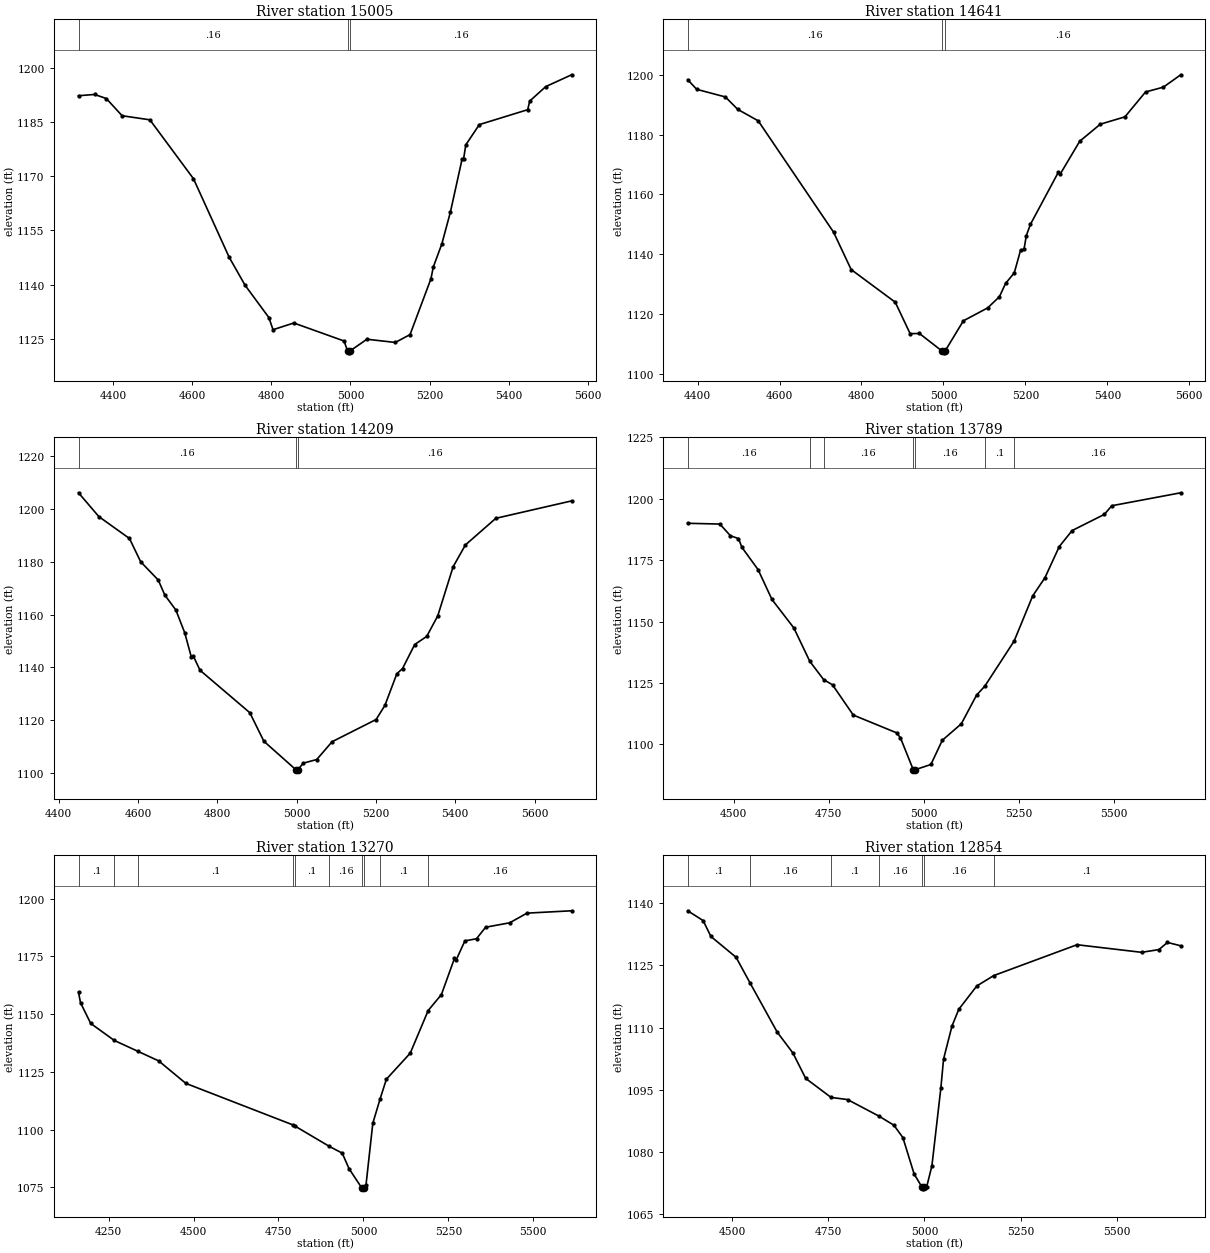
Type RM Length L Ch R = 1 ,15005   ,364,364,364
BEGIN DESCRIPTION:
UNT 1018 IN LATR 33.0
END DESCRIPTION:
XS GIS Cut Line= 4
      2977778.47     10058416.33      2978299.31     10058451.06
      2978689.94     10058676.75      2978954.07     10058746.03
#Sta/Elev= 30
  4312.7 1192.23  4353.3 1192.58  4382.9 1191.46  4422.9  1186.7  4493.1 1185.57
  4603.3 1169.28  4693.5 1147.58  4733.6 1139.86  4793.8 1130.92  4804.3 1127.56
  4856.8 1129.42  4983.9 1124.44  4992.6 1121.67  4995.3 1121.17  4998.6 1121.67
  5041.6 1124.93  5113.3 1124.04  5150.6 1126.21  5203.3  1141.6  5209.5 1144.94
    5231 1151.29  5252.5 1160.04  5282.1 1174.71  5285.8 1174.71  5291.6 1178.67
  5325.7 1184.25  5447.9 1188.37  5453.1 1190.76  5493.5 1194.75  5558.9 1198.02
#Mann= 3 ,-1 , 0
  4312.7     .16       0  4992.6     .07       0  4998.6     .16       0
Bank Sta=4992.6,4998.6
XS Rating Curve= 0 ,0
Exp/Cntr=0.3,0.1

Type RM Length L Ch R = 1 ,14641   ,432,432,432
BEGIN DESCRIPTION:
UNT 1018 IN LATR 32.0
END DESCRIPTION:
XS GIS Cut Line= 4
      2977726.39     10058720.15       2978082.3     10058720.15
      2978472.92     10058971.89       2978854.2     10059002.22
#Sta/Elev= 30
  4375.9 1198.31    4398 1195.09    4468 1192.54    4498  1188.4    4548 1184.57
  4731.8  1147.4  4774.8 1134.89  4882.4 1123.98  4918.7 1113.48  4941.4 1113.53
  4997.5 1107.57  5000.3 1107.07  5003.5 1107.57  5048.7 1117.78  5107.9 1122.08
  5136.5 1125.81  5151.7 1130.28  5172.8 1133.78    5188 1141.29  5196.5 1141.61
  5202.1 1146.17  5212.1 1149.96  5280.1 1167.33  5285.1 1166.83  5332.5 1177.75
  5382.7 1183.44  5442.8  1185.9    5493  1194.2  5536.6 1195.82    5579 1199.95
#Mann= 3 ,-1 , 0
  4375.9     .16       0  4997.5     .07       0  5003.5     .16       0
Bank Sta=4997.5,5003.5
XS Rating Curve= 0 ,0
Exp/Cntr=0.3,0.1

Type RM Length L Ch R = 1 ,14209   ,420,420,420
BEGIN DESCRIPTION:
UNT 1018 IN LATR 31.0
END DESCRIPTION:
XS GIS Cut Line= 3
      2977544.13     10058937.18      2978399.14     10059375.54
      2978675.18     10059435.92
#Sta/Elev= 30
    4450 1206.07  4501.3 1197.06  4578.5 1188.78  4606.7 1179.99  4651.1 1173.06
  4667.7 1167.36  4695.5 1161.72  4717.7 1153.18  4734.3 1144.04  4739.9 1144.18
  4756.5 1138.93  4881.9  1122.9  4917.5 1112.08  4997.6  1101.4  5000.4  1100.9
  5003.6  1101.4  5016.8 1103.81  5050.7 1105.17  5089.4 1111.91  5200.4 1120.31
  5222.6 1125.64  5252.7 1137.62    5267 1139.57  5297.7 1148.67    5328 1151.74
  5355.8 1159.49  5394.6 1178.08  5425.6 1186.34  5502.3 1196.41  5693.4    1203
#Mann= 3 ,-1 , 0
    4450     .16       0  4997.6     .07       0  5003.6     .16       0
Bank Sta=4997.6,5003.6
XS Rating Curve= 0 ,0
Exp/Cntr=0.3,0.1

Type RM Length L Ch R = 1 ,13789   ,519,519,519
BEGIN DESCRIPTION:
UNT 1018 IN LATR 30.0
END DESCRIPTION:
XS GIS Cut Line= 4
      2977426.91     10059349.49      2977795.84     10059583.87
      2978338.38     10059566.51      2978642.21     10059657.66
#Sta/Elev= 30
  4379.4 1189.98  4464.2 1189.66  4491.8 1184.91    4513 1183.76  4522.3 1180.14
  4564.7 1171.11  4601.1 1158.98  4658.7  1147.4  4700.7  1133.8  4737.1 1126.37
  4760.4 1124.25  4815.1 1111.94  4929.2 1104.71  4939.2 1102.66  4972.7 1089.75
  4975.4 1089.25  4978.7 1089.75  5019.2 1091.83  5049.2 1101.68  5099.3 1108.39
  5139.3 1120.04  5161.1 1123.72  5238.2 1142.06  5287.1 1160.46  5319.4 1167.87
  5356.8 1180.48  5390.7 1187.01  5475.4 1193.59  5495.1 1197.12  5676.5 1202.39
#Mann= 7 ,-1 , 0
  4379.4     .16       0  4700.7      .1       0  4737.1     .16       0
  4972.7     .07       0  4978.7     .16       0  5161.1      .1       0
  5238.2     .16       0
Bank Sta=4972.7,4978.7
XS Rating Curve= 0 ,0
Exp/Cntr=0.3,0.1

Type RM Length L Ch R = 1 ,13270   ,416,416,416
BEGIN DESCRIPTION:
UNT 1018 IN LATR 29.0
END DESCRIPTION:
XS GIS Cut Line= 3
      2977192.58     10060065.64      2978260.25     10060096.02
      2978637.88     10060030.91
#Sta/Elev= 30
  4161.4 1159.45  4167.3 1154.96  4197.3    1146  4266.6 1138.64  4335.6 1133.97
  4397.4 1129.78  4477.4 1120.04  4793.3 1102.03  4799.1 1101.52  4899.7 1092.78
  4937.6 1089.85  4957.6 1083.14  4994.6 1074.91  4997.4 1074.41  5000.6 1074.91
  5007.6 1076.13  5027.6 1102.79  5049.2  1113.4  5067.6 1121.87  5137.7 1133.11
  5190.6 1151.59  5229.5 1158.48  5267.8  1174.1  5272.9 1173.46  5298.7 1181.73
  5332.8 1182.64  5359.6 1187.63  5430.6 1189.55  5481.4 1193.73  5612.7 1194.75
#Mann= 10 ,-1 , 0
  4161.4      .1       0  4266.6     .05       0  4335.6      .1       0
  4793.3     .16       0  4799.1      .1       0  4899.7     .16       0
  4994.6     .07       0  5000.6     .16       0  5049.2      .1       0
  5190.6     .16       0
Bank Sta=4994.6,5000.6
XS Rating Curve= 0 ,0
Exp/Cntr=0.3,0.1

Type RM Length L Ch R = 1 ,12854   ,415,415,415
BEGIN DESCRIPTION:
UNT 1018 IN LATR 28.0
END DESCRIPTION:
XS GIS Cut Line= 4
      2977348.83     10060347.77      2977782.82     10060421.54
       2978147.4     10060582.13      2978584.65     10060512.87
#Sta/Elev= 30
  4384.6 1138.17  4424.8 1135.81    4445 1131.98  4510.4 1126.96  4546.1 1120.88
  4617.5  1108.9  4658.1  1103.9  4691.2 1097.79  4757.2  1093.2  4800.1 1092.68
  4881.5  1088.7  4920.5  1086.5  4943.8 1083.53    4973 1074.76  4992.9 1071.67
  4995.7 1071.17  4998.9 1071.67  5005.8 1071.69  5019.3 1076.74  5042.6 1095.53
  5049.5 1102.42  5071.4 1110.39  5089.2 1114.44  5135.9 1120.05  5179.8 1122.55
  5396.4 1129.99    5564 1128.16    5609 1128.81  5631.4 1130.54  5665.9 1129.73
#Mann= 7 ,-1 , 0
  4384.6      .1       0  4546.1     .16       0  4757.2      .1       0
  4881.5     .16       0  4992.9     .07       0  4998.9     .16       0
  5179.8      .1       0
Bank Sta=4992.9,4998.9
XS Rating Curve= 0 ,0
Exp/Cntr=0.3,0.1

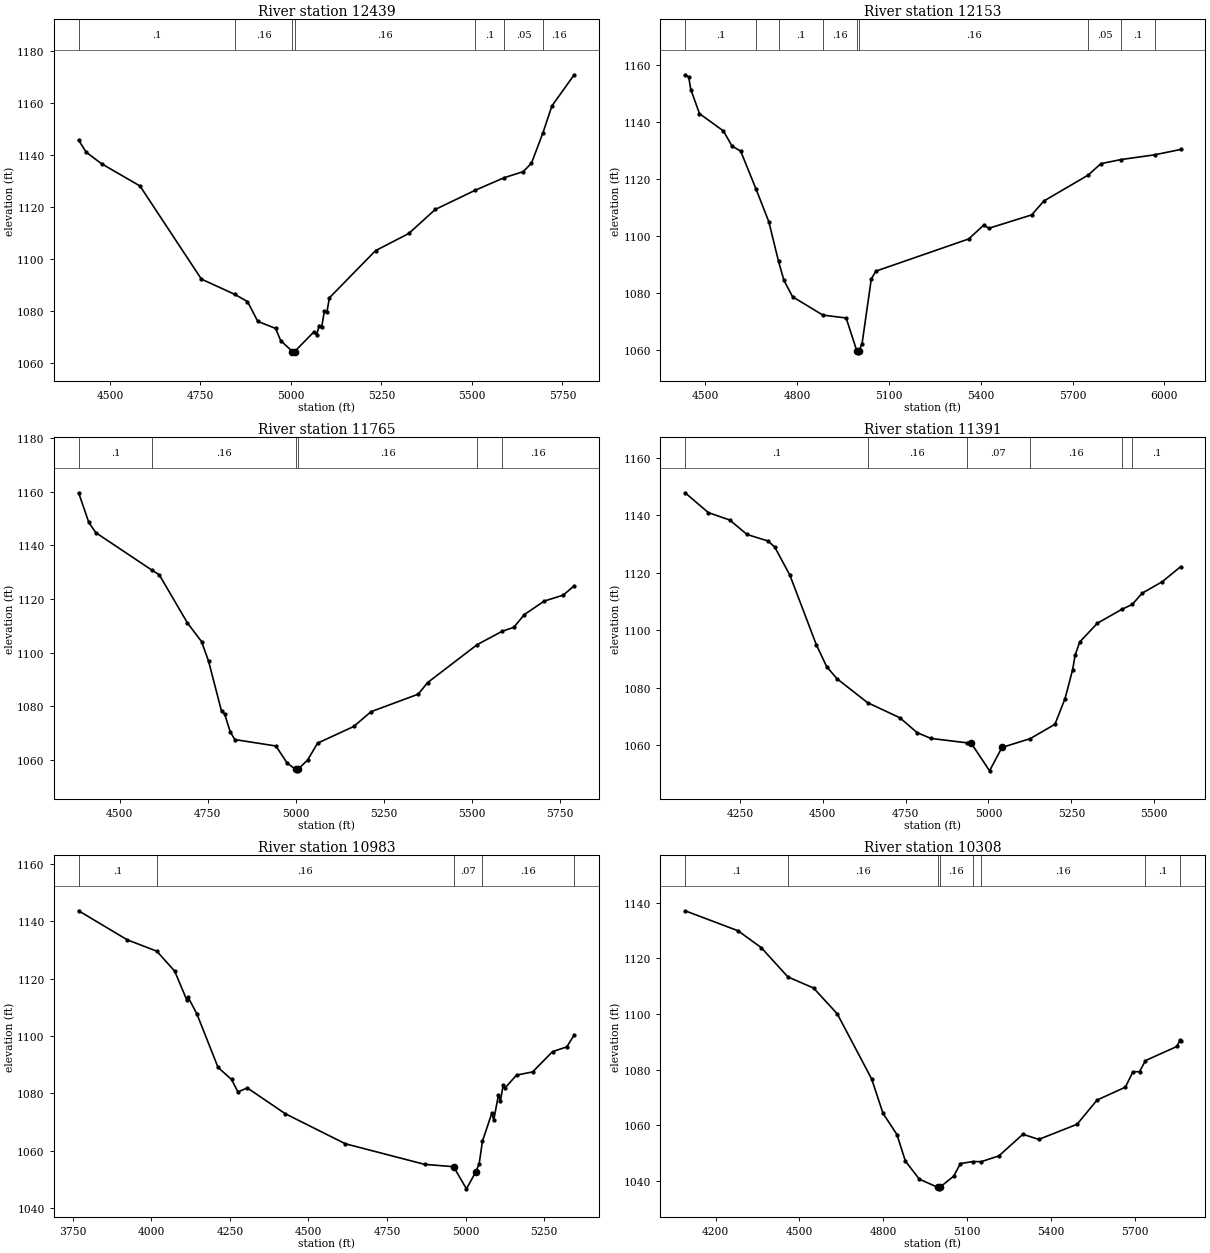
Type RM Length L Ch R = 1 ,12439   ,286,286,286
BEGIN DESCRIPTION:
UNT 1018 IN LATR 27.0
END DESCRIPTION:
XS GIS Cut Line= 4
      2977301.05     10060421.54      2977617.89     10060738.38
      2977947.75     10061072.59      2978354.58     10061267.34
#Sta/Elev= 30
  4413.6 1145.82  4434.5 1141.18    4477 1136.73    4583 1128.19  4752.7 1092.35
  4844.7  1086.5    4880 1083.71  4908.3 1076.11  4957.8 1073.36  4971.9 1068.64
  5004.3 1064.49  5007.1 1063.99  5010.3 1064.49  5063.9 1072.12  5070.9 1070.89
    5078  1074.5  5085.1 1074.06  5092.2 1079.98  5099.2 1079.53  5106.3 1085.17
  5233.6  1103.3  5325.5  1109.9  5398.6 1119.15  5508.1 1126.48  5588.9 1131.37
  5641.7  1133.7  5664.4 1136.96  5696.1 1148.65  5720.8 1158.98  5782.3 1170.96
#Mann= 7 ,-1 , 0
  4413.6      .1       0  4844.7     .16       0  5004.3     .07       0
  5010.3     .16       0  5508.1      .1       0  5588.9     .05       0
  5696.1     .16       0
Bank Sta=5004.3,5010.3
XS Rating Curve= 0 ,0
Exp/Cntr=0.3,0.1

Type RM Length L Ch R = 1 ,12153   ,388,388,388
BEGIN DESCRIPTION:
UNT 1018 IN LATR 26.0
END DESCRIPTION:
XS GIS Cut Line= 4
      2977136.11     10060599.48      2977422.58     10060872.93
      2977735.08     10061458.87      2978238.58     10061701.94
#Sta/Elev= 30
  4433.9 1156.65  4445.7 1155.84  4452.6 1151.46  4480.9 1143.02  4558.9 1136.96
  4587.2 1131.66  4615.5 1129.87  4666.2 1116.41  4707.4 1105.12  4739.2 1091.21
  4756.7 1084.56    4785 1078.79  4884.1 1072.34  4960.2 1071.32  4995.5  1059.6
  4998.2  1059.1  5001.5  1059.6  5012.2 1062.36  5042.4 1085.08  5057.5 1087.77
  5360.5 1099.05    5410 1103.94  5426.3 1102.79  5566.3 1107.49    5606 1112.35
  5750.8 1121.45  5792.4 1125.46  5858.2 1126.91  5967.7 1128.56  6053.1 1130.45
#Mann= 9 ,-1 , 0
  4433.9      .1       0  4666.2     .16       0  4739.2      .1       0
  4884.1     .16       0  4995.5     .07       0  5001.5     .16       0
  5750.8     .05       0  5858.2      .1       0  5967.7     .08       0
Bank Sta=4995.5,5001.5
XS Rating Curve= 0 ,0
Exp/Cntr=0.3,0.1

Type RM Length L Ch R = 1 ,11765   ,374,374,374
BEGIN DESCRIPTION:
Mapping XS 51cf6a29
END DESCRIPTION:
XS GIS Cut Line= 4
      2977044.97     10060564.82      2977040.63     10060972.76
      2977248.97     10061341.68      2977301.05     10061914.57
#Sta/Elev= 30
  4383.6  1159.6  4412.5 1148.53  4432.5 1144.71  4592.4 1130.69  4612.5 1129.03
  4692.5 1111.07  4732.5 1104.14  4752.5 1096.83  4789.5 1078.07  4797.9  1077.2
  4813.8 1070.54  4827.1 1067.59  4943.7 1065.19  4975.5 1058.85  4999.9 1056.43
  5002.7 1055.93  5005.9 1056.43  5033.9    1060  5062.1 1066.26  5164.7 1072.47
  5213.6 1077.97  5347.8 1084.52  5374.2 1088.81  5514.9 1102.96  5586.8 1108.01
    5619 1109.43  5649.1 1114.19  5705.5 1119.22  5759.5 1121.44  5790.5 1124.92
#Mann= 6 ,-1 , 0
  4383.6      .1       0  4592.4     .16       0  4999.9     .07       0
  5005.9     .16       0  5514.9      .1       0  5586.8     .16       0
Bank Sta=4999.9,5005.9
XS Rating Curve= 0 ,0
Exp/Cntr=0.3,0.1

Type RM Length L Ch R = 1 ,11391   ,408,408,408
BEGIN DESCRIPTION:
UNT 1018 IN LATR 25.0
END DESCRIPTION:
XS GIS Cut Line= 3
      2976914.76     10060464.97      2976728.13     10061081.27
      2977023.05     10061879.28
#Sta/Elev= 30
  4084.9 1147.86  4154.9 1140.97  4219.4 1138.39  4271.7 1133.36  4335.2 1131.08
  4355.3 1128.99  4401.1 1119.17  4480.7 1095.02    4512 1087.39  4543.3 1083.17
  4635.2 1074.88  4732.8 1069.61  4784.8 1064.44  4826.4 1062.43    4934 1060.92
  4948.1 1060.73  5003.3 1051.16  5040.6 1059.29  5125.9 1062.36  5200.5 1067.35
  5230.9 1076.28  5253.9 1086.37  5261.3 1091.38  5275.2 1095.96  5328.5  1102.5
  5401.8  1107.3  5433.6 1109.02  5463.6 1112.94  5524.4 1116.95  5579.6 1122.16
#Mann= 6 ,-1 , 0
  4084.9      .1       0  4635.2     .16       0    4934     .07       0
  5125.9     .16       0  5401.8     .05       0  5433.6      .1       0
Bank Sta=4948.1,5040.6
XS Rating Curve= 0 ,0
Exp/Cntr=0.3,0.1

Type RM Length L Ch R = 1 ,10983   ,675,675,675
BEGIN DESCRIPTION:
UNT 1018 IN LATR 24.0
END DESCRIPTION:
XS GIS Cut Line= 4
       2976628.3     10060319.58      2976526.31     10061328.66
      2976467.72     10061617.29      2976614.36     10061841.57
#Sta/Elev= 30
  3768.8  1143.7  3923.7 1133.56  4017.5 1129.62  4074.5 1122.64  4112.4 1112.73
  4117.5 1113.48  4144.9 1107.79  4212.4 1089.09  4255.4 1084.89  4275.5 1080.56
  4305.7 1081.93  4426.3 1072.95  4617.3 1062.48  4869.8 1055.29  4961.7 1054.48
  5002.7 1046.76  5033.1 1052.78  5043.3 1055.54  5053.6 1063.36  5083.7 1073.19
  5089.6 1070.69  5104.7 1079.59  5110.7 1077.32  5119.8    1083  5125.8 1081.96
    5162 1086.41  5213.3 1087.52  5276.6  1094.6  5321.9 1096.24  5345.5  1100.4
#Mann= 5 ,-1 , 0
  3768.8      .1       0  4017.5     .16       0  4961.7     .07       0
  5053.6     .16       0  5345.5     .16       0
Bank Sta=4961.7,5033.1
XS Rating Curve= 0 ,0
Exp/Cntr=0.3,0.1

Type RM Length L Ch R = 1 ,10308   ,106,106,106
BEGIN DESCRIPTION:
UNT 1018 IN LATR 23.0
END DESCRIPTION:
XS GIS Cut Line= 4
      2976231.18     10060191.46      2976044.54     10060849.06
      2976051.05     10061126.84      2976514.47     10061793.82
#Sta/Elev= 30
    4091 1137.04  4280.5 1129.86  4363.6 1123.81  4458.8  1113.3  4550.7 1109.31
  4635.6 1100.04  4758.6 1076.68  4799.3 1064.33  4849.3 1056.67  4879.3 1047.19
  4929.3 1040.68  4996.3  1037.7  4999.1  1037.2  5002.3  1037.7  5052.4 1041.77
  5076.6 1046.29  5121.9    1047  5150.7 1046.95  5213.7 1049.01  5300.1 1056.79
  5356.9 1054.95    5494 1060.39  5565.5 1069.08  5666.8 1073.71    5694 1079.24
  5717.5 1079.27  5738.8 1083.26  5852.3 1088.37  5862.2 1090.67  5864.6 1090.36
#Mann= 8 ,-1 , 0
    4091      .1       0  4458.8     .16       0  4996.3     .07       0
  5002.3     .16       0  5121.9      .1       0  5150.7     .16       0
  5738.8      .1       0  5862.2     .16       0
Bank Sta=4996.3,5002.3
XS Rating Curve= 0 ,0
Exp/Cntr=0.3,0.1

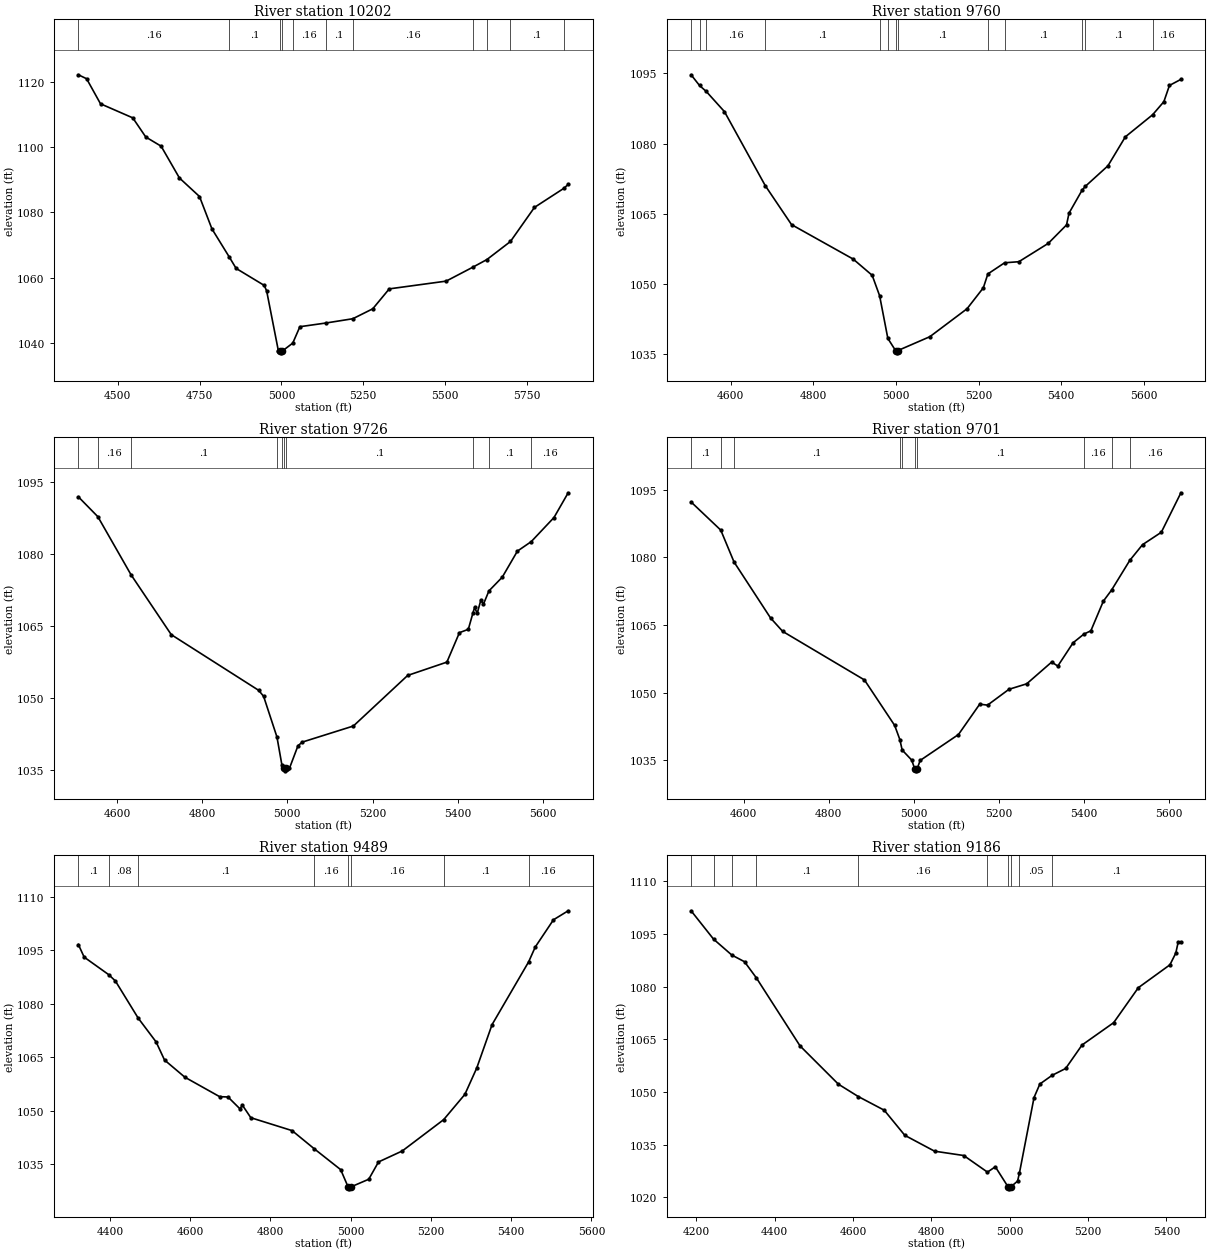
Type RM Length L Ch R = 1 ,10202   ,442,442,442
BEGIN DESCRIPTION:
UNT 1018 IN LATR 22.0
END DESCRIPTION:
XS GIS Cut Line= 5
      2975384.79     10060872.92      2975857.91     10061044.37
      2976066.24     10061178.92      2976313.64     10061678.05
      2976459.02     10061797.39
#Sta/Elev= 30
  4379.7 1122.15  4404.9 1120.94  4447.4 1113.27    4546 1108.96  4585.7  1103.1
  4632.6 1100.29  4688.5 1090.56  4749.8 1084.89  4787.8 1074.98  4841.2  1066.3
  4861.7 1062.88  4947.7 1057.67    4955 1055.97  4990.7 1037.69  4996.1 1037.54
  4998.9 1037.04  5002.1 1037.54  5034.7 1040.02  5056.5 1045.04  5135.4 1046.16
  5218.2 1047.48  5279.1 1050.52  5329.5 1056.62  5503.3 1058.99  5583.9 1063.21
  5627.6 1065.58  5699.7 1071.12  5773.1 1081.56  5863.1 1087.41  5876.1 1088.61
#Mann= 11 ,-1 , 0
  4379.7     .16       0  4841.2      .1       0  4996.1     .07       0
  5002.1      .1       0  5034.7     .16       0  5135.4      .1       0
  5218.2     .16       0  5583.9      .1       0  5627.6     .16       0
  5699.7      .1       0  5863.1     .16       0
Bank Sta=4996.1,5002.1
XS Rating Curve= 0 ,0
Exp/Cntr=0.3,0.1

Type RM Length L Ch R = 1 ,9760    ,34,34,34
BEGIN DESCRIPTION:
Mapping XS 33858dc0
END DESCRIPTION:
XS GIS Cut Line= 4
      2975484.66     10061244.04       2975814.5     10061526.14
      2976064.07     10061534.82      2976472.03     10061827.78
#Sta/Elev= 30
  4504.1 1094.71  4524.5 1092.42  4540.8 1091.15  4584.9 1086.83  4683.7 1071.01
  4747.3 1062.68  4896.6 1055.31  4942.6 1051.84  4960.6 1047.47  4980.5 1038.35
  4999.1 1035.77  5001.9 1035.27  5005.1 1035.77  5082.2 1038.72  5172.2 1044.69
  5211.7 1049.17  5222.7 1052.14  5263.2 1054.52  5297.7 1054.75  5368.9 1058.67
  5413.1 1062.61  5419.2 1065.14  5450.8 1070.04  5458.5 1070.85  5513.4 1075.25
  5555.5 1081.44  5621.5 1086.16  5648.8 1088.96  5662.3 1092.43  5690.1 1093.73
#Mann= 13 ,-1 , 0
  4504.1     .16       0  4524.5      .1       0  4540.8     .16       0
  4683.7      .1       0  4960.6     .16       0  4980.5      .1       0
  4999.1     .07       0  5005.1      .1       0  5222.7     .16       0
  5263.2      .1       0  5450.8     .16       0  5458.5      .1       0
  5621.5     .16       0
Bank Sta=4999.1,5005.1
XS Rating Curve= 0 ,0
Exp/Cntr=0.3,0.1

Type RM Length L Ch R = 1 ,9726    ,25,25,25
BEGIN DESCRIPTION:
Mapping XS 801c47a1
END DESCRIPTION:
XS GIS Cut Line= 4
      2975475.95     10061278.74      2975805.82      10061558.7
      2976053.22     10061560.87      2976432.99     10061836.47
#Sta/Elev= 30
  4509.6 1091.92  4555.4 1087.78  4633.1 1075.71  4727.6 1063.23    4933 1051.62
  4944.3 1050.38  4975.6 1041.92  4987.1 1036.15  4991.9 1035.38  4994.7 1034.88
  4997.9 1035.38  5004.9 1035.41  5024.9  1040.1  5034.9 1040.86  5154.9 1044.21
  5282.3 1054.74  5374.3 1057.51  5403.7 1063.64  5424.6 1064.34  5435.1 1067.64
  5439.3 1068.89  5445.4 1067.67  5453.9 1070.38  5460.1 1069.57  5472.9 1072.33
  5504.2 1075.19  5539.8 1080.62  5572.2 1082.59  5625.6 1087.61  5658.9 1092.76
#Mann= 10 ,-1 , 0
  4509.6      .1       0  4555.4     .16       0  4633.1      .1       0
  4975.6     .16       0  4987.1      .1       0  4991.9     .07       0
  4997.9      .1       0  5435.1     .16       0  5472.9      .1       0
  5572.2     .16       0
Bank Sta=4991.9,4997.9
XS Rating Curve= 0 ,0
Exp/Cntr=0.3,0.1

Type RM Length L Ch R = 1 ,9701    ,212,212,212
BEGIN DESCRIPTION:
Mapping XS e2c3846d
END DESCRIPTION:
XS GIS Cut Line= 4
       2975456.4     10061291.74      2975799.31     10061582.57
      2976033.69      10061580.4      2976413.47     10061853.84
#Sta/Elev= 30
  4476.7 1092.27  4546.5 1086.03  4577.7 1078.96  4663.6 1066.54  4692.1 1063.57
  4884.4  1052.8  4955.5 1042.71  4967.7 1039.57  4973.1 1037.26  4995.5 1035.03
  5002.5 1033.14  5005.2 1032.64  5008.5 1033.14  5015.5 1034.95  5105.5 1040.69
  5155.5 1047.43  5173.9 1047.21  5224.2 1050.72    5266 1051.94  5324.8 1056.77
  5339.1 1055.87  5375.1 1061.04  5400.4 1062.96  5416.9  1063.7  5446.3 1070.28
  5465.6 1072.73  5508.4 1079.31  5538.4  1082.8  5582.6 1085.55  5628.7 1094.31
#Mann= 10 ,-1 , 0
  4476.7      .1       0  4546.5     .16       0  4577.7      .1       0
  4967.7     .16       0  4973.1      .1       0  5002.5     .07       0
  5008.5      .1       0  5400.4     .16       0  5465.6      .1       0
  5508.4     .16       0
Bank Sta=5002.5,5008.5
XS Rating Curve= 0 ,0
Exp/Cntr=0.3,0.1

Type RM Length L Ch R = 1 ,9489    ,303,303,303
BEGIN DESCRIPTION:
UNT 1018 IN LATR 21.0
END DESCRIPTION:
XS GIS Cut Line= 3
      2975421.72     10061291.78      2975721.19      10061725.8
      2976364.56     10061983.58
#Sta/Elev= 30
  4321.6 1096.61  4336.1 1093.07  4397.4 1088.14  4413.9 1086.38  4470.6 1075.98
  4515.3 1069.29  4536.3 1064.21    4587 1059.39  4673.5 1053.94  4694.5 1053.84
  4724.2 1050.52  4730.3 1051.55  4751.3 1048.03  4854.1 1044.41  4909.7 1039.28
  4975.2 1033.46  4993.8 1028.58  4996.5 1028.08  4999.8 1028.58  5045.1 1030.77
  5069.4 1035.62  5128.6  1038.7  5231.7 1047.48  5284.6 1054.57  5314.2 1061.97
  5352.3 1074.13  5443.5 1091.75    5460 1095.92  5505.3 1103.54    5542 1106.07
#Mann= 8 ,-1 , 0
  4321.6      .1       0  4397.4     .08       0  4470.6      .1       0
  4909.7     .16       0  4993.8     .07       0  4999.8     .16       0
  5231.7      .1       0  5443.5     .16       0
Bank Sta=4993.8,4999.8
XS Rating Curve= 0 ,0
Exp/Cntr=0.3,0.1

Type RM Length L Ch R = 1 ,9186    ,337,337,337
BEGIN DESCRIPTION:
UNT 1018 IN LATR 20.0
END DESCRIPTION:
XS GIS Cut Line= 3
      2975367.45     10061298.26      2975636.55     10061923.28
      2975957.73     10062394.19
#Sta/Elev= 30
  4186.5  1101.6  4243.9 1093.52  4290.4    1089  4322.9 1087.09    4353 1082.52
  4464.6 1063.13  4562.6 1052.22  4613.2 1048.71  4679.6 1044.81  4732.1 1037.66
  4808.1 1033.14  4882.5 1031.91  4943.1 1027.18  4963.2  1028.7  4996.1 1022.92
  4998.8 1022.42  5002.1 1022.92    5020 1024.63  5024.8 1026.96    5062 1048.42
  5076.9 1052.27    5108 1054.73  5142.7 1056.69  5184.6 1063.38  5265.3 1069.74
  5328.3  1079.7  5408.9 1086.21  5423.9 1089.55  5429.9 1092.62    5437 1092.68
#Mann= 10 ,-1 , 0
  4186.5     .08       0  4243.9     .16       0  4290.4     .08       0
    4353      .1       0  4613.2     .16       0  4943.1      .1       0
  4996.1     .07       0  5002.1      .1       0  5024.8     .05       0
    5108      .1       0
Bank Sta=4996.1,5002.1
XS Rating Curve= 0 ,0
Exp/Cntr=0.3,0.1

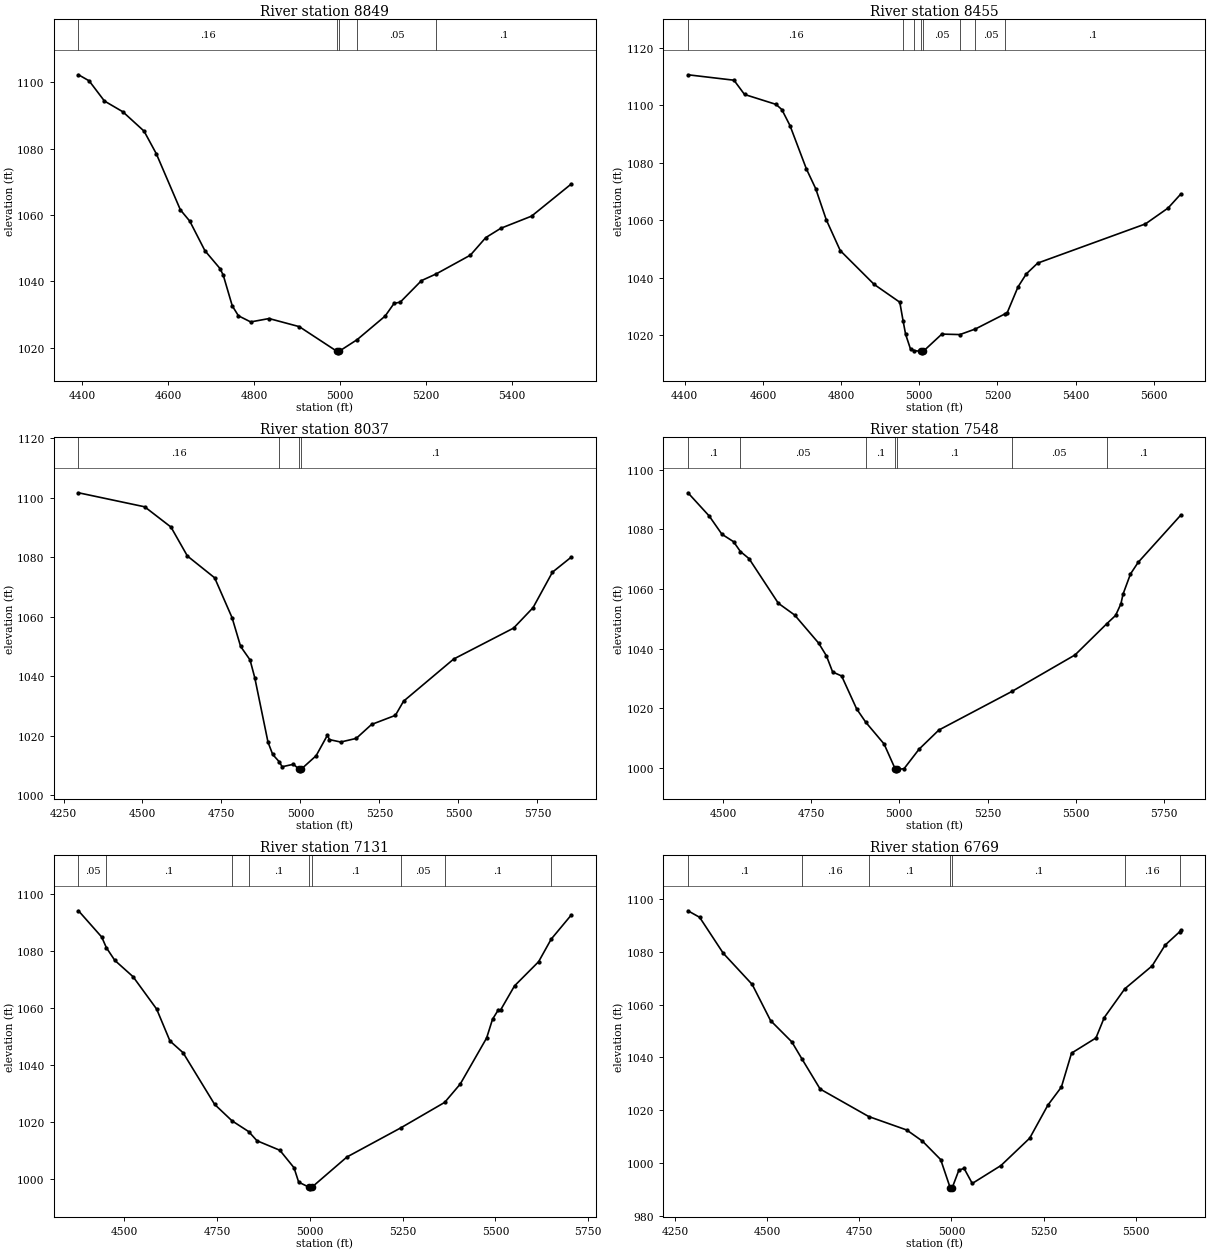
Type RM Length L Ch R = 1 ,8849    ,394,394,394
BEGIN DESCRIPTION:
UNT 1018 IN LATR 19.0
END DESCRIPTION:
XS GIS Cut Line= 4
      2975039.74     10061647.65      2975382.65     10061942.81
      2975397.84     10062198.89      2975679.94     10062533.06
#Sta/Elev= 30
  4391.3 1102.24    4416 1100.42  4451.6 1094.33  4494.4 1091.09  4543.8 1085.25
  4572.3 1078.43  4628.3 1061.51  4650.2  1058.1  4685.4 1049.19  4720.5 1043.81
  4728.1 1041.78    4749 1032.56  4763.3 1029.57  4791.8 1027.72  4834.6 1028.74
  4904.8  1026.3  4991.9  1018.9  4994.7  1018.4  4997.9  1018.9  5039.3 1022.36
  5104.6 1029.49  5125.4 1033.32  5139.7 1033.68  5189.1 1040.18  5223.5 1042.21
  5302.9 1047.86  5338.6 1053.14  5373.7 1055.96  5445.2 1059.62  5537.6 1069.32
#Mann= 5 ,-1 , 0
  4391.3     .16       0  4991.9     .07       0  4997.9     .16       0
  5039.3     .05       0  5223.5      .1       0
Bank Sta=4991.9,4997.9
XS Rating Curve= 0 ,0
Exp/Cntr=0.3,0.1

Type RM Length L Ch R = 1 ,8455    ,418,418,418
BEGIN DESCRIPTION:
UNT 1018 IN LATR 18.0
END DESCRIPTION:
XS GIS Cut Line= 3
      2974599.19     10061910.23      2975271.97      10062372.5
      2975649.56     10062606.86
#Sta/Elev= 30
  4408.3 1110.56    4526 1108.67    4553 1103.72  4633.5 1100.27  4648.4 1098.48
  4669.4 1092.87  4711.3 1077.81    4735 1070.99  4762.1 1060.15  4797.9 1049.42
  4884.6 1037.67  4950.2 1031.47  4958.7 1024.93  4965.1 1020.31  4977.7 1015.14
  4987.7 1014.65    5004 1014.37  5006.8 1013.87    5010 1014.37  5057.8 1020.39
    5104 1020.22  5143.8 1022.18  5220.4 1027.49  5224.6 1027.69  5252.6 1036.79
  5273.9 1041.33  5302.9 1045.07  5578.6  1058.7  5636.5 1064.22    5669 1069.08
#Mann= 8 ,-1 , 0
  4408.3     .16       0  4958.7      .1       0  4987.7     .05       0
    5004    .035       0    5010     .05       0    5104      .1       0
  5143.8     .05       0  5220.4      .1       0
Bank Sta=5004,5010
XS Rating Curve= 0 ,0
Exp/Cntr=0.3,0.1

Type RM Length L Ch R = 1 ,8037    ,489,489,489
BEGIN DESCRIPTION:
UNT 1018 IN LATR 17.0
END DESCRIPTION:
XS GIS Cut Line= 4
      2974511.11     10062012.22      2974628.31     10062423.71
       2975000.7     10062678.92      2975672.55     10062788.29
#Sta/Elev= 30
  4297.4 1101.59  4506.9 1096.88  4590.1 1090.08  4642.1 1080.36  4728.4 1073.04
  4783.6 1059.64  4810.6    1050  4840.4 1045.48  4855.4 1039.49  4897.3 1017.85
  4912.2 1013.72  4932.9 1011.27    4942  1009.6  4977.9 1010.44  4995.8 1008.73
  4998.6 1008.23  5001.8 1008.73  5049.6  1013.3  5085.5 1020.22  5091.6 1018.72
  5127.4  1017.9  5176.5 1019.12  5225.1  1023.8  5300.5 1026.86  5326.4 1031.61
  5485.1 1045.77  5674.7 1056.16  5736.2    1063  5797.7 1074.93  5857.4    1080
#Mann= 4 ,-1 , 0
  4297.4     .16       0  4932.9      .1       0  4995.8     .07       0
  5001.8      .1       0
Bank Sta=4995.8,5001.8
XS Rating Curve= 0 ,0
Exp/Cntr=0.3,0.1

Type RM Length L Ch R = 1 ,7548    ,417,417,417
BEGIN DESCRIPTION:
UNT 1018 IN LATR 16.0
END DESCRIPTION:
XS GIS Cut Line= 4
      2974000.66     10062592.96       2974375.7     10062762.26
      2974758.52     10063181.53       2975110.1     10063408.11
#Sta/Elev= 30
  4400.5 1092.28  4460.8 1084.48  4496.8 1078.37  4529.8 1075.87  4549.3 1072.56
  4573.6  1070.2  4656.8 1055.21    4703 1051.27  4771.1 1041.84  4793.1 1037.58
  4810.8 1032.15  4836.3 1030.81  4878.9 1019.76  4904.9 1015.27  4956.6 1008.01
  4988.7  999.49  4991.5  998.99  4994.7  999.49  5013.3  999.71  5055.9 1006.26
    5112 1012.68  5319.3 1025.64  5498.2 1037.88  5587.7 1048.29  5613.1 1051.12
  5628.3 1055.04  5634.2 1058.25  5655.4 1065.04  5677.1 1068.93    5798 1084.78
#Mann= 7 ,-1 , 0
  4400.5      .1       0  4549.3     .05       0  4904.9      .1       0
  4988.7     .07       0  4994.7      .1       0  5319.3     .05       0
  5587.7      .1       0
Bank Sta=4988.7,4994.7
XS Rating Curve= 0 ,0
Exp/Cntr=0.3,0.1

Type RM Length L Ch R = 1 ,7131    ,362,362,362
BEGIN DESCRIPTION:
UNT 1018 IN LATR 15.0
END DESCRIPTION:
XS GIS Cut Line= 4
      2973787.17     10062816.95      2974078.83     10063142.46
      2974542.37     10063366.42      2974727.26     10063694.54
#Sta/Elev= 30
    4376 1094.12  4438.7 1084.89  4451.2 1081.15  4473.9 1076.72  4523.2 1070.98
  4586.7 1059.63  4622.6 1048.43  4657.8 1044.34    4743 1026.19  4789.8 1020.43
  4834.9 1016.63  4857.1 1013.44  4918.8 1010.09    4957 1003.96  4969.5  998.92
  4998.5  997.06  5001.2  996.56  5004.5  997.06  5099.6 1007.73  5244.5 1017.93
  5363.1 1026.89  5405.1 1033.33  5476.2 1049.48  5492.1 1056.06  5508.1 1059.43
  5513.8 1059.29  5551.4 1067.77  5616.4 1076.26  5650.3 1084.18  5704.5 1092.65
#Mann= 9 ,-1 , 0
    4376     .05       0  4451.2      .1       0  4789.8     .16       0
  4834.9      .1       0  4998.5     .07       0  5004.5      .1       0
  5244.5     .05       0  5363.1      .1       0  5650.3     .16       0
Bank Sta=4998.5,5004.5
XS Rating Curve= 0 ,0
Exp/Cntr=0.3,0.1

Type RM Length L Ch R = 1 ,6769    ,593,593,593
BEGIN DESCRIPTION:
UNT 1018 IN LATR 14.0
END DESCRIPTION:
XS GIS Cut Line= 4
      2973505.88     10063051.29      2973930.39     10063382.05
      2974232.47     10063741.42      2974514.86       10063915.
#Sta/Elev= 30
  4283.9 1095.57  4315.6  1093.1  4379.8 1079.48  4458.5 1067.65  4508.3 1053.98
  4566.1  1045.9  4593.2 1039.54  4643.1 1028.03  4775.1 1017.61  4878.2 1012.52
  4921.2 1008.28  4970.6  1001.3  4996.2  990.72    4999  990.22  5002.2  990.72
  5020.2  997.36  5034.3  997.94  5056.4  992.26  5134.5  999.06  5212.5 1009.42
  5261.9 1021.94  5298.6 1028.78  5326.2 1041.64  5392.5 1047.38  5415.1 1055.12
  5470.9 1066.01  5545.1 1074.68  5580.3 1082.54  5620.1 1087.63    5623 1088.18
#Mann= 7 ,-1 , 0
  4283.9      .1       0  4593.2     .16       0  4775.1      .1       0
  4996.2     .07       0  5002.2      .1       0  5470.9     .16       0
  5620.1      .1       0
Bank Sta=4996.2,5002.2
XS Rating Curve= 0 ,0
Exp/Cntr=0.3,0.1