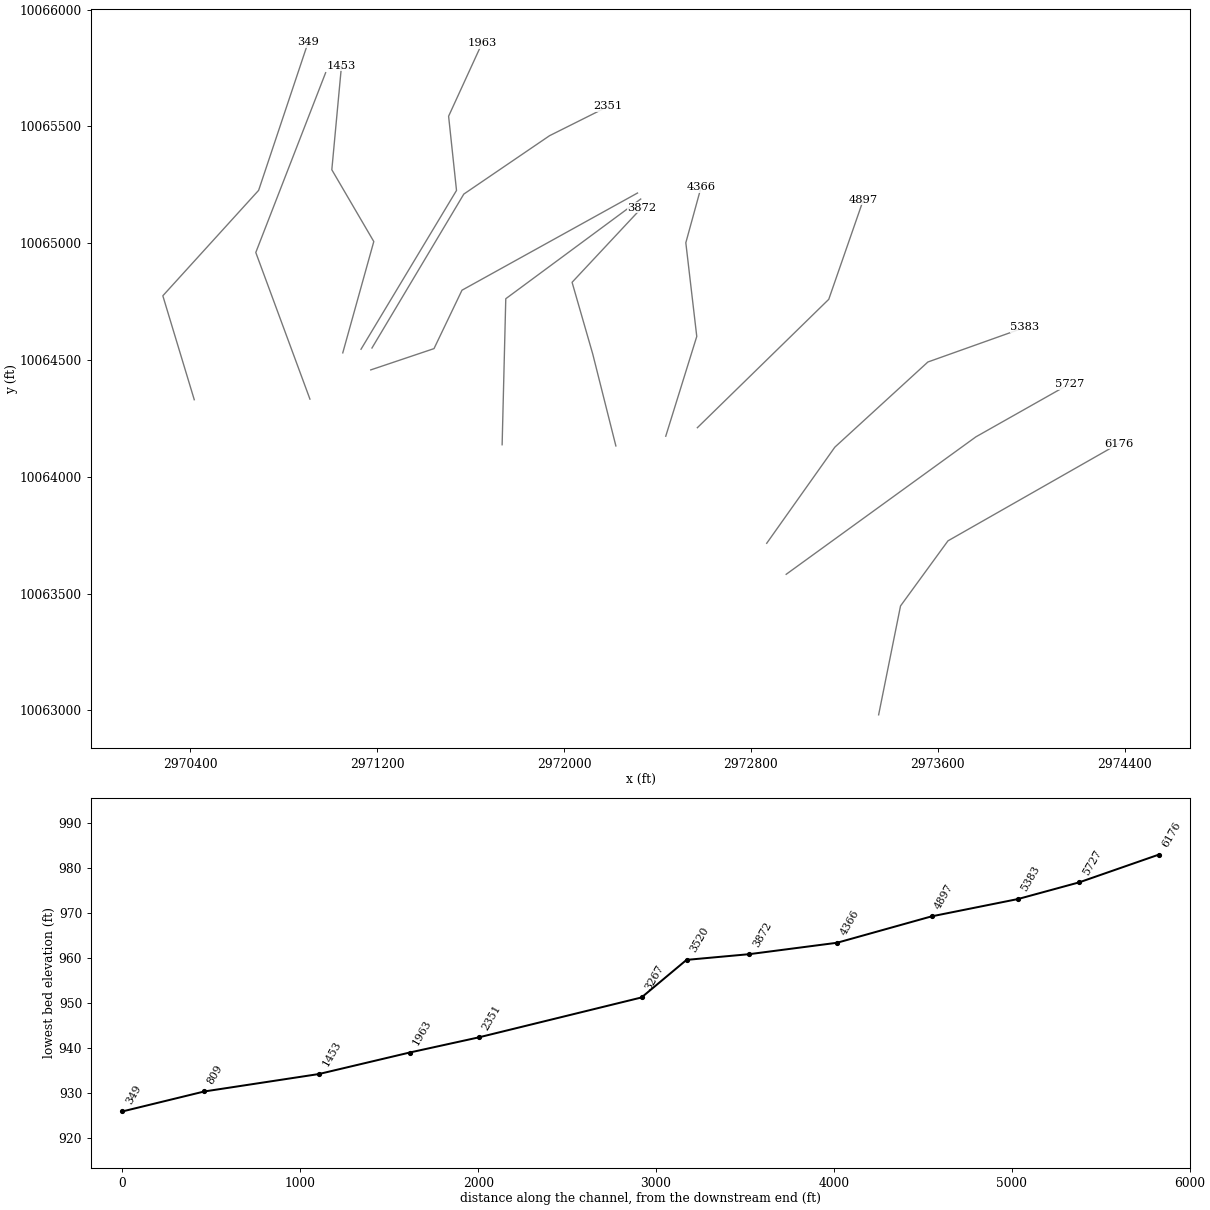
HEC-RAS study UNT 1018 IN LATR.prj: UNT 1018 IN LATR Base Level Engineering

--- UNT 1018 IN LATR.g01 (geometry) --- (continued)

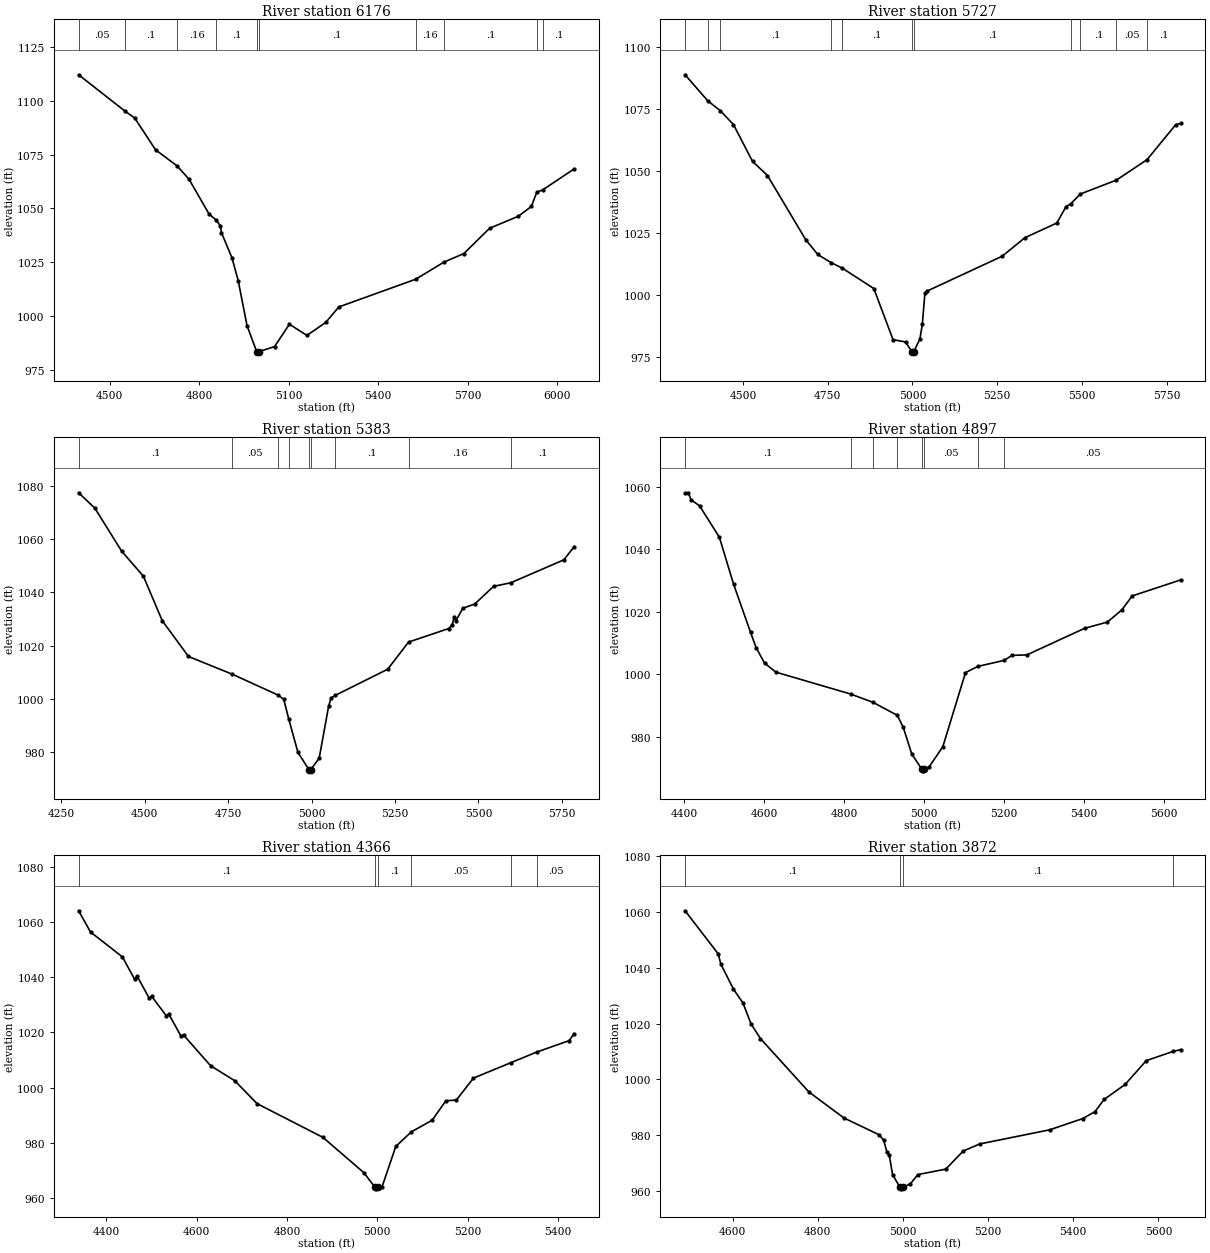
Type RM Length L Ch R = 1 ,6176    ,449,449,449
BEGIN DESCRIPTION:
UNT 1018 IN LATR 13.0
END DESCRIPTION:
XS GIS Cut Line= 4
      2973347.07     10062981.05      2973440.81     10063447.15
      2973643.93      10063725.8      2974374.63     10064141.85
#Sta/Elev= 30
  4395.5 1112.04  4552.2 1095.03  4583.5 1091.98  4653.2 1077.23  4725.1 1069.79
  4765.4 1063.59  4832.7 1047.39  4855.8 1044.68  4870.9 1041.87  4874.2 1038.75
  4909.7 1027.02  4930.6 1016.37  4959.9  995.63  4992.5  983.47  4995.2  982.97
  4998.5  983.47  5052.3  985.88  5102.1  996.24  5160.8  991.05  5224.2  997.12
  5267.4 1004.25  5525.2 1017.13  5619.6 1025.03  5686.8 1029.06  5773.3 1040.81
  5869.8 1046.39    5913  1050.9  5931.4 1057.55  5952.1 1058.68  6056.6 1068.36
#Mann= 10 ,-1 , 0
  4395.5     .05       0  4552.2      .1       0  4725.1     .16       0
  4855.8      .1       0  4992.5     .07       0  4998.5      .1       0
  5525.2     .16       0  5619.6      .1       0  5931.4     .16       0
  5952.1      .1       0
Bank Sta=4992.5,4998.5
XS Rating Curve= 0 ,0
Exp/Cntr=0.3,0.1

Type RM Length L Ch R = 1 ,5727    ,344,344,344
BEGIN DESCRIPTION:
UNT 1018 IN LATR 12.0
END DESCRIPTION:
XS GIS Cut Line= 3
      2972951.26     10063582.59      2973763.72     10064171.11
      2974164.13     10064397.31
#Sta/Elev= 30
  4328.6  1088.9  4395.3 1078.43    4432 1074.48  4471.3 1068.84  4527.7 1053.99
  4571.8 1048.28  4684.7  1022.4  4720.3 1016.45  4759.9 1013.13  4792.1 1010.98
  4885.8 1002.71  4942.5   982.1  4979.6  981.17    4998  977.28  5000.7  976.78
    5004  977.28  5021.9  982.41    5029  988.24  5036.6 1000.73  5042.7 1001.67
  5264.7 1015.73  5331.7 1023.19    5426 1029.12  5453.4 1035.77  5467.5 1036.91
  5495.3 1040.81  5602.1 1046.43  5692.5 1054.68  5776.9 1068.75  5791.7 1069.29
#Mann= 11 ,-1 , 0
  4328.6      .1       0  4395.3     .05       0    4432      .1       0
  4759.9     .05       0  4792.1      .1       0    4998     .07       0
    5004      .1       0  5467.5     .16       0  5495.3      .1       0
  5602.1     .05       0  5692.5      .1       0
Bank Sta=4998,5004
XS Rating Curve= 0 ,0
Exp/Cntr=0.3,0.1

Type RM Length L Ch R = 1 ,5383    ,486,486,486
BEGIN DESCRIPTION:
UNT 1018 IN LATR 11.0
END DESCRIPTION:
XS GIS Cut Line= 4
      2972867.87     10063715.35      2973159.56     10064126.84
      2973557.99     10064491.42      2973972.53      10064639.1
#Sta/Elev= 30
  4302.3 1077.42    4351 1071.63    4431 1055.54  4496.2 1046.12  4552.8 1029.41
  4631.3 1015.99  4763.1  1009.3  4899.8  1001.5  4916.8  999.87  4931.7  992.54
  4959.3  979.97    4992  973.57  4994.7  973.07    4998  973.57  5022.9   977.8
  5051.2  997.31  5058.6 1000.43  5071.3 1001.41  5228.2  1011.2  5290.6 1021.39
  5410.9 1026.47  5421.6 1027.91  5427.5 1030.96  5432.8 1029.43    5453 1034.06
  5489.1 1035.69  5545.5 1042.32  5596.9 1043.64  5755.9 1052.26  5786.8 1057.19
#Mann= 9 ,-1 , 0
  4302.3      .1       0  4763.1     .05       0  4899.8      .1       0
  4931.7     .05       0    4992    .035       0    4998     .05       0
  5071.3      .1       0  5290.6     .16       0  5596.9      .1       0
Bank Sta=4992,4998
XS Rating Curve= 0 ,0
Exp/Cntr=0.3,0.1

Type RM Length L Ch R = 1 ,4897    ,531,531,531
BEGIN DESCRIPTION:
UNT 1018 IN LATR 10.0
END DESCRIPTION:
XS GIS Cut Line= 3
      2972570.99     10064210.15      2973133.52     10064759.65
      2973281.95     10065186.72
#Sta/Elev= 30
  4402.8 1057.97  4410.7 1058.07  4417.7 1055.84    4439 1053.89  4488.4 1043.89
  4523.8 1028.92  4566.3 1013.49  4580.4 1008.54  4601.5 1003.64  4629.8 1000.74
  4816.2  993.77  4872.8  991.08  4933.3  986.93    4948  983.12  4969.3  974.59
  4994.6  969.71  4997.4  969.21  5000.6  969.71  5011.8   970.3    5047  976.94
  5103.6  1000.6  5134.7  1002.6  5200.5 1004.51  5219.7 1006.11    5257 1006.26
  5401.1 1014.75    5458 1016.74  5494.4 1020.64  5520.2 1025.11  5641.3 1030.21
#Mann= 8 ,-1 , 0
  4402.8      .1       0  4816.2     .05       0  4872.8      .1       0
  4933.3     .05       0  4994.6    .035       0  5000.6     .05       0
  5134.7      .1       0  5200.5     .05       0
Bank Sta=4994.6,5000.6
XS Rating Curve= 0 ,0
Exp/Cntr=0.3,0.1

Type RM Length L Ch R = 1 ,4366    ,494,494,494
BEGIN DESCRIPTION:
UNT 1018 IN LATR 9.0
END DESCRIPTION:
XS GIS Cut Line= 4
       2972435.6     10064173.73      2972568.41      10064600.8
      2972521.54     10065001.84      2972586.62     10065238.75
#Sta/Elev= 30
  4339.1 1064.03  4365.4 1056.34  4435.8 1047.35  4463.1 1039.23  4468.3 1040.41
  4495.6 1032.31  4500.9 1033.03  4533.4 1025.93  4538.6 1026.64  4565.9 1018.56
  4571.2 1019.05    4631 1007.94  4684.7 1002.48  4733.9  994.21  4879.9  981.96
  4970.5  969.17  4995.4  963.84  4998.2  963.34  5001.4  963.84  5010.8  964.15
    5041  978.69  5075.3  983.96  5121.5  988.18  5151.7  995.21  5175.2  995.51
  5212.8 1003.43  5294.9 1008.97  5353.4  1012.9  5424.6    1017  5435.8 1019.55
#Mann= 6 ,-1 , 0
  4339.1      .1       0  4995.4     .07       0  5001.4      .1       0
  5075.3     .05       0  5294.9      .1       0  5353.4     .05       0
Bank Sta=4995.4,5001.4
XS Rating Curve= 0 ,0
Exp/Cntr=0.3,0.1

Type RM Length L Ch R = 1 ,3872    ,352,352,352
BEGIN DESCRIPTION:
UNT 1018 IN LATR 8.0
END DESCRIPTION:
XS GIS Cut Line= 4
      2972222.06     10064132.05       2972123.1     10064525.28
      2972034.56     10064832.57      2972333.77      10065152.6
#Sta/Elev= 30
  4488.6  1060.4  4566.2    1045  4572.8 1041.21  4602.2 1032.32  4624.4  1027.4
  4643.3 1019.93  4665.6  1014.6  4779.1  995.52  4861.6  986.17  4944.5  980.14
  4954.9  978.17  4962.6  973.86  4967.8     973  4975.7   965.9  4993.2   961.3
    4996   960.8  4999.2   961.3  5017.4   962.6  5035.1  965.91  5100.6  967.86
  5141.3  974.32  5180.2  976.87  5344.8  981.95  5422.5  985.99  5450.8  988.44
  5472.3  992.81  5521.6  998.18  5571.4 1006.73  5634.7 1010.04    5652 1010.67
#Mann= 4 ,-1 , 0
  4488.6      .1       0  4993.2     .07       0  4999.2      .1       0
  5634.7     .05       0
Bank Sta=4993.2,4999.2
XS Rating Curve= 0 ,0
Exp/Cntr=0.3,0.1

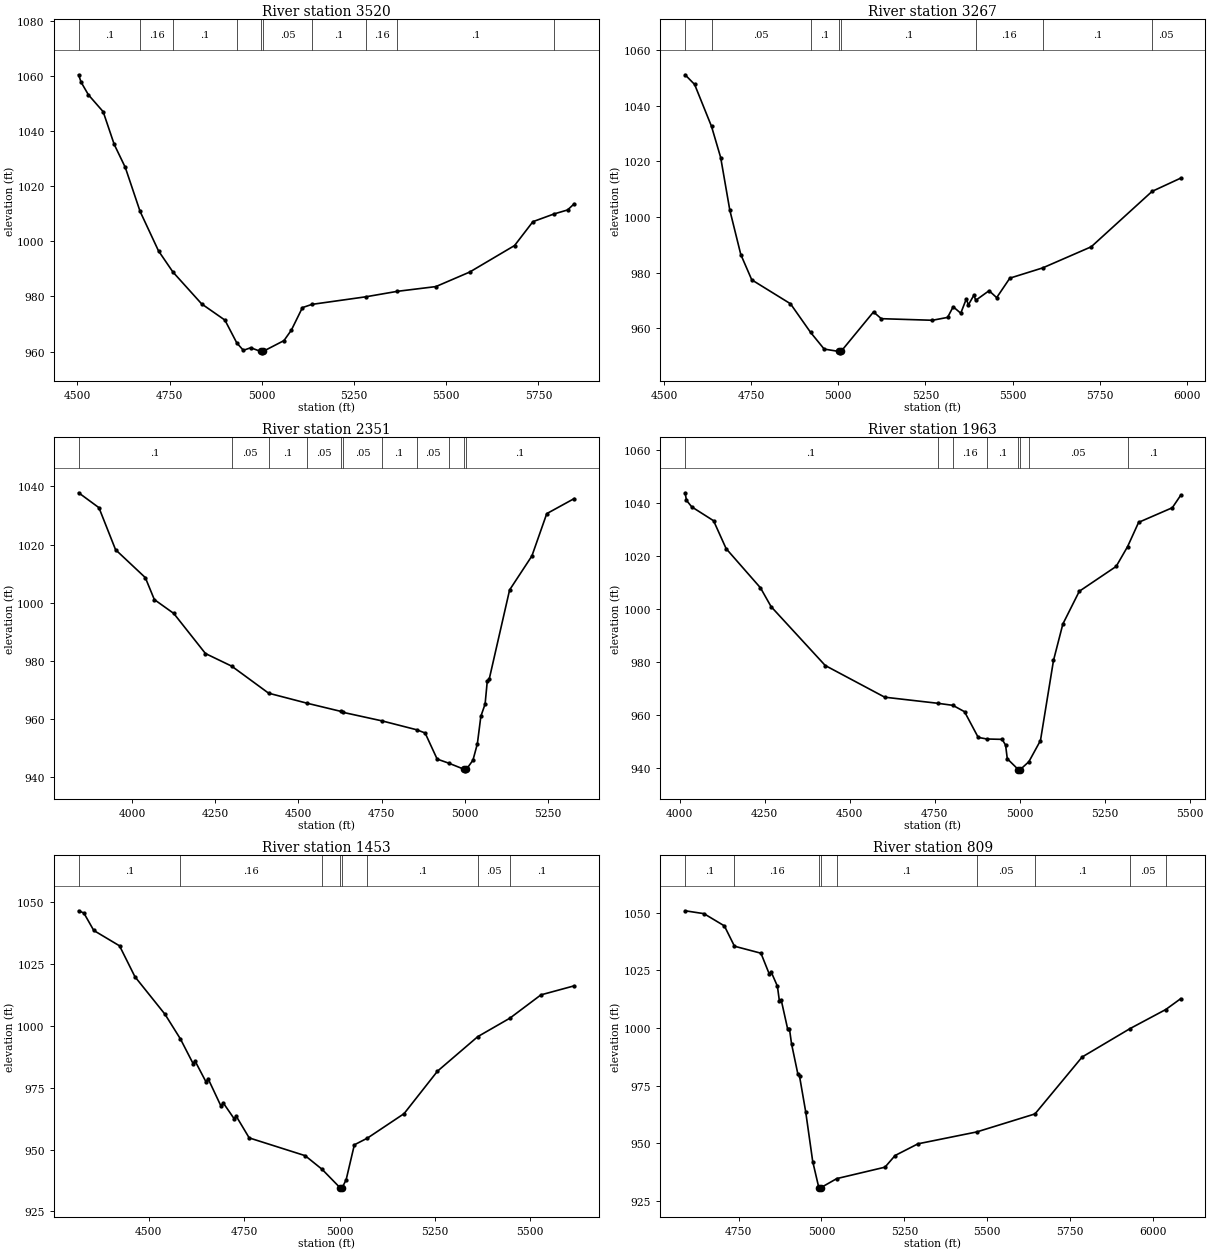
Type RM Length L Ch R = 1 ,3520    ,253,253,253
BEGIN DESCRIPTION:
UNT 1018 IN LATR 7.0
END DESCRIPTION:
XS GIS Cut Line= 3
      2971735.08     10064137.23       2971750.7     10064762.26
      2972328.44     10065189.05
#Sta/Elev= 30
  4503.3 1060.44  4509.8  1057.8  4529.8 1053.17  4569.8 1047.04  4599.8 1035.16
  4629.8 1026.82  4669.9 1010.86  4719.9  996.52    4759  988.85  4836.9  977.28
  4899.9  971.41  4932.1  963.13  4949.9  960.44  4969.9  961.38    4997  960.03
  4999.7  959.53    5003  960.03    5060  963.97    5080  967.76    5110  975.94
  5135.9  977.12  5281.6  979.86  5367.7  981.86  5471.8  983.57  5563.6  988.85
  5685.2  998.47  5734.9 1007.13  5792.2 1009.93  5828.8 1011.38  5846.8  1013.6
#Mann= 10 ,-1 , 0
  4503.3      .1       0  4669.9     .16       0    4759      .1       0
  4932.1     .05       0    4997    .035       0    5003     .05       0
  5135.9      .1       0  5281.6     .16       0  5367.7      .1       0
  5792.2     .05       0
Bank Sta=4997,5003
XS Rating Curve= 0 ,0
Exp/Cntr=0.3,0.1

Type RM Length L Ch R = 1 ,3267    ,916,916,916
BEGIN DESCRIPTION:
UNT 1018 IN LATR 6.0
END DESCRIPTION:
XS GIS Cut Line= 4
      2971172.59     10064457.57      2971443.41     10064548.71
       2971563.2     10064798.71      2972314.66     10065214.74
#Sta/Elev= 30
  4560.4 1051.14  4587.7 1047.67  4636.2 1032.59  4662.5 1021.38  4688.7 1002.47
  4720.2  986.52  4751.7  977.41  4862.8  968.81  4920.5  958.52  4959.5  952.52
  5001.8  951.67  5004.6  951.17  5007.8  951.67    5101  965.87  5123.4  963.45
  5270.1  962.88  5313.6  963.91  5329.6  967.74  5351.4  965.41  5367.4  970.59
  5373.1  968.38  5389.2  971.93  5394.3  970.05  5432.7  973.51  5454.4  971.01
  5492.2  978.02  5586.5  981.71  5725.8   989.3  5900.4 1009.22  5982.3 1013.97
#Mann= 8 ,-1 , 0
  4560.4      .1       0  4636.2     .05       0  4920.5      .1       0
  5001.8     .07       0  5007.8      .1       0  5394.3     .16       0
  5586.5      .1       0  5900.4     .05       0
Bank Sta=5001.8,5007.8
XS Rating Curve= 0 ,0
Exp/Cntr=0.3,0.1

Type RM Length L Ch R = 1 ,2351    ,388,388,388
BEGIN DESCRIPTION:
UNT 1018 IN LATR 5.0
END DESCRIPTION:
XS GIS Cut Line= 4
      2971177.77     10064551.29      2971571.02     10065210.17
       2971938.2     10065460.17      2972188.17     10065585.16
#Sta/Elev= 30
  3838.7 1037.83  3899.8 1032.71  3949.8 1018.27  4039.3 1008.68  4066.5 1001.13
  4124.9  996.37  4220.3  982.59  4299.3  978.25  4410.4  968.96  4527.3  965.48
  4628.5  962.69  4635.4  962.35  4751.4  959.45  4855.3  956.41  4881.2  955.29
  4917.4  946.32  4951.8  944.94  4999.2  942.78  5001.9  942.28  5005.2  942.78
  5025.1  945.92  5038.4  951.56  5048.9  961.01  5061.7  965.23  5068.3   973.2
  5073.9   973.7  5135.4 1004.44  5202.5 1016.12  5247.2 1030.66  5329.7 1035.83
#Mann= 11 ,-1 , 0
  3838.7      .1       0  4299.3     .05       0  4410.4      .1       0
  4527.3     .05       0  4628.5     .16       0  4635.4     .05       0
  4751.4      .1       0  4855.3     .05       0  4951.8      .1       0
  4999.2     .07       0  5005.2      .1       0
Bank Sta=4999.2,5005.2
XS Rating Curve= 0 ,0
Exp/Cntr=0.3,0.1

Type RM Length L Ch R = 1 ,1963    ,510,510,510
BEGIN DESCRIPTION:
UNT 1018 IN LATR 4.0
END DESCRIPTION:
XS GIS Cut Line= 4
      2971130.91      10064546.1      2971539.77      10065225.8
      2971505.91     10065543.51      2971649.16     10065856.04
#Sta/Elev= 30
  4016.3 1043.95  4020.3  1041.1  4035.9 1038.62    4100 1033.39  4136.9 1022.85
  4237.9 1008.03    4269 1000.95  4428.2   978.7  4603.1  966.73  4758.2  964.44
  4803.4  963.65  4837.6  961.25  4877.8  951.55  4902.9  950.94  4948.2   950.8
  4958.3  948.62  4963.3  943.47  4995.5  939.41  4998.2  938.91  5001.5  939.41
  5026.8  942.37  5060.8  950.36  5099.1  980.62  5126.6  994.37  5174.9 1006.74
  5283.3 1016.13  5316.9 1023.62  5349.3 1032.78  5448.3  1038.3  5472.8 1042.97
#Mann= 8 ,-1 , 0
  4016.3      .1       0  4758.2     .05       0  4803.4     .16       0
  4902.9      .1       0  4995.5     .07       0  5001.5      .1       0
  5026.8     .05       0  5316.9      .1       0
Bank Sta=4995.5,5001.5
XS Rating Curve= 0 ,0
Exp/Cntr=0.3,0.1

Type RM Length L Ch R = 1 ,1453    ,644,644,644
BEGIN DESCRIPTION:
UNT 1018 IN LATR 3.0
END DESCRIPTION:
XS GIS Cut Line= 4
      2971052.79     10064530.51       2971185.6     10065007.05
      2971005.91     10065314.34      2971047.41     10065760.45
#Sta/Elev= 30
  4316.3 1046.52    4330 1045.61    4356 1038.56  4423.5 1032.35  4463.8 1019.88
  4542.6  1004.7  4583.1  994.71  4616.2  984.78  4621.3  985.84  4650.3   977.3
  4655.5  978.69  4689.7  967.46  4694.9  968.96  4723.9  962.46  4729.1  963.56
  4763.3  954.72  4909.9  947.54  4954.3  942.03  5001.1  934.63  5003.8  934.13
  5007.1  934.63  5017.4   937.8  5038.9  951.92  5073.1  954.63  5169.2  964.52
  5256.7  981.68  5362.3  995.64  5446.5 1003.11  5527.9 1012.53    5615 1016.18
#Mann= 8 ,-1 , 0
  4316.3      .1       0  4583.1     .16       0  4954.3     .05       0
  5001.1    .035       0  5007.1     .05       0  5073.1      .1       0
  5362.3     .05       0  5446.5      .1       0
Bank Sta=5001.1,5007.1
XS Rating Curve= 0 ,0
Exp/Cntr=0.3,0.1

Type RM Length L Ch R = 1 ,809     ,460,460,460
BEGIN DESCRIPTION:
UNT 1018 IN LATR 2.0
END DESCRIPTION:
XS GIS Cut Line= 3
      2970912.17     10064332.54      2970680.39     10064960.17
      2970979.43     10065729.86
#Sta/Elev= 30
  4588.7 1050.76  4645.6 1049.51  4707.2 1044.21  4737.6  1035.4  4817.5 1032.37
  4842.6 1023.35  4847.9 1024.38  4867.1  1018.1    4873 1011.84  4878.4 1012.25
  4898.1  999.51  4903.5  999.58  4909.8  993.08  4928.6  980.19  4933.9  979.06
  4952.4  963.72  4973.7  942.07  4992.1  930.75  4994.8  930.25  4998.1  930.75
  5046.1  934.68  5191.7  939.64  5222.1  944.69  5291.1  949.76  5468.1   954.9
  5644.1  962.72  5786.4  987.39  5931.4  999.74  6038.7 1007.97  6083.5 1012.64
#Mann= 9 ,-1 , 0
  4588.7      .1       0  4737.6     .16       0  4992.1     .07       0
  4998.1     .16       0  5046.1      .1       0  5468.1     .05       0
  5644.1      .1       0  5931.4     .05       0  6038.7      .1       0
Bank Sta=4992.1,4998.1
XS Rating Curve= 0 ,0
Exp/Cntr=0.3,0.1

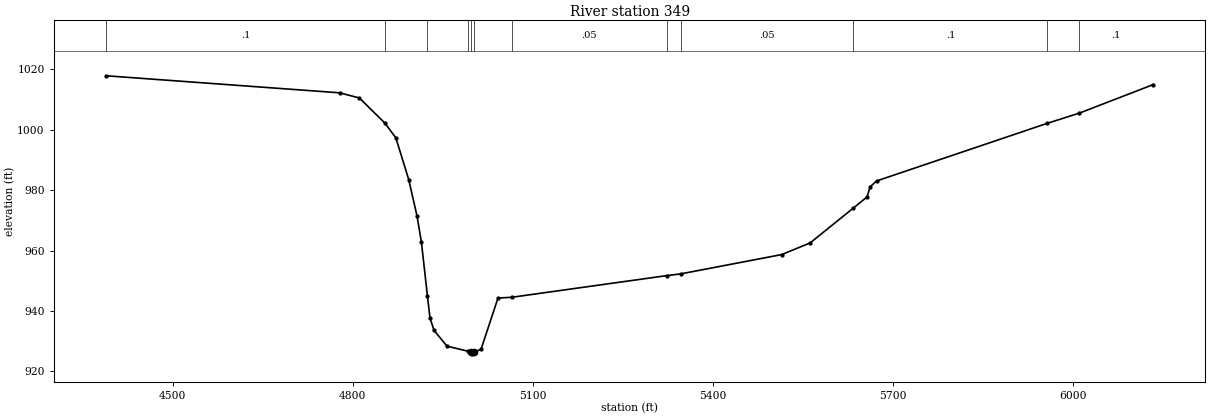
Type RM Length L Ch R = 1 ,349     ,0,0,0
BEGIN DESCRIPTION:
UNT 1018 IN LATR 1.0
END DESCRIPTION:
XS GIS Cut Line= 4
      2970416.94     10064329.95      2970282.39     10064774.84
      2970692.54     10065226.23      2970904.65      10065860.4
#Sta/Elev= 30
  4389.3 1017.88  4777.9 1012.24  4810.9 1010.54  4853.4 1002.23  4871.7  997.32
  4893.1  983.52  4906.9  971.49  4914.3   962.7  4924.2  945.08  4928.5  937.72
  4935.2  933.59  4956.9  928.35  4991.3   926.7  4996.4  926.31  4999.2  925.81
  5002.4  926.31  5013.6  927.36  5041.8  944.29  5064.4  944.53  5322.5   951.7
  5346.2  952.29  5514.1  958.67  5561.5  962.52  5633.8  974.11  5656.3  977.75
  5661.7  981.14  5672.3  983.06  5956.6 1002.14    6010 1005.52  6132.7 1014.95
#Mann= 12 ,-1 , 0
  4389.3      .1       0  4853.4     .16       0  4924.2     .05       0
  4991.3      .1       0  4996.4     .07       0  5002.4      .1       0
  5064.4     .05       0  5322.5      .1       0  5346.2     .05       0
  5633.8      .1       0  5956.6     .05       0    6010      .1       0
Bank Sta=4996.4,5002.4
XS Rating Curve= 0 ,0
Exp/Cntr=0.3,0.1

Chan Stop Cuts=-1
Use User Specified Reach Order=0
Composite Channel Slope=5