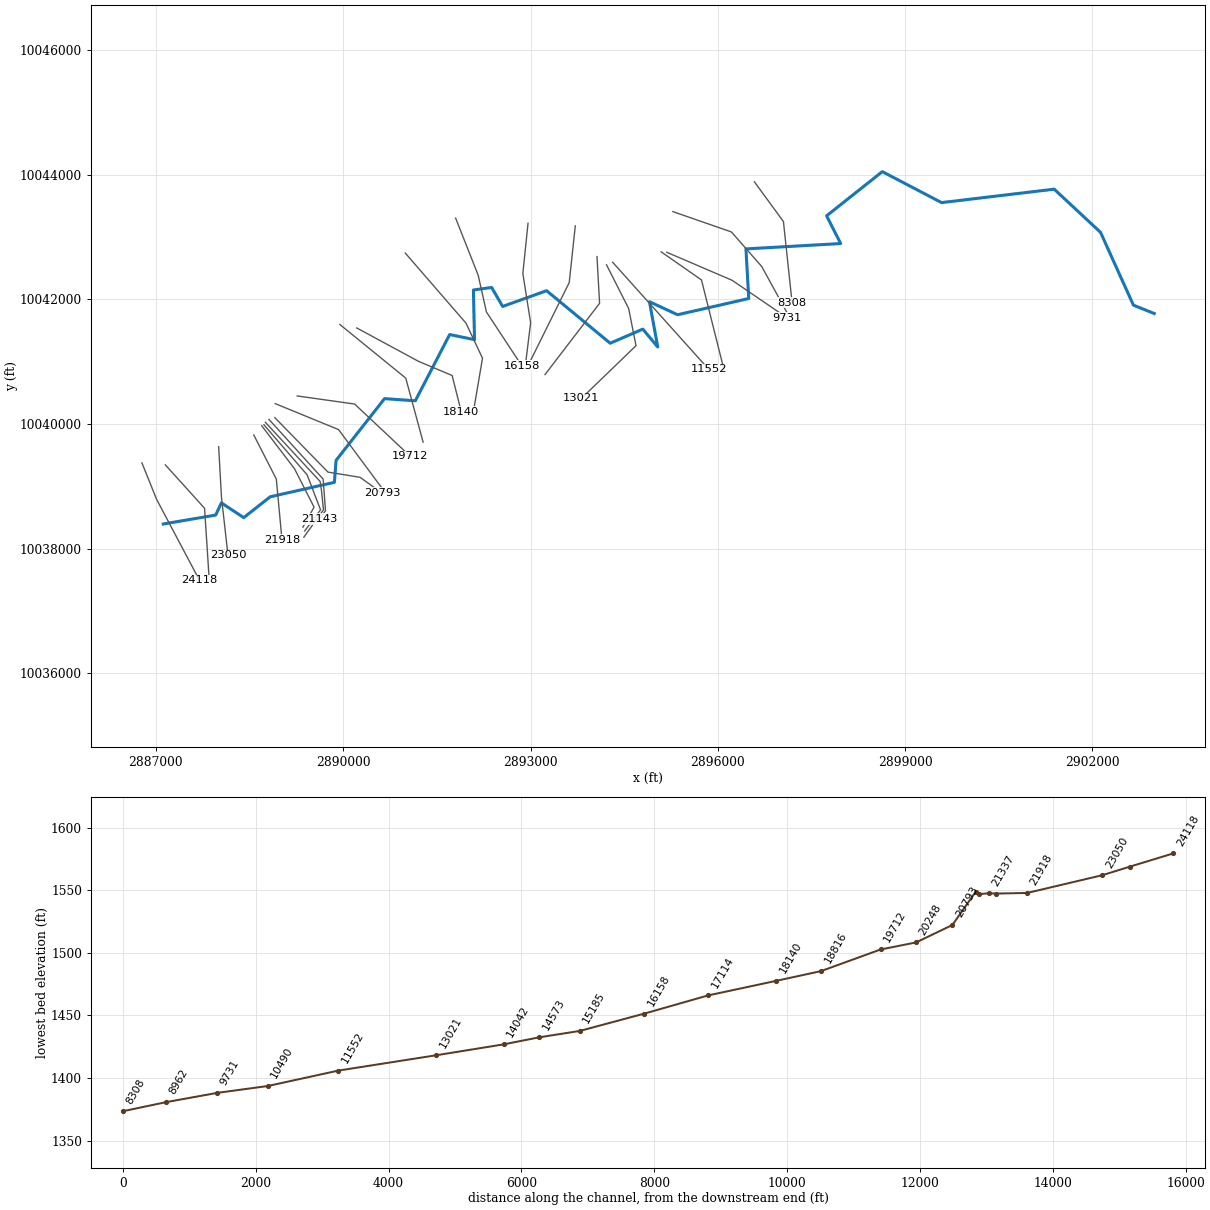
--- UNT 1023 IN LATR.prj (project) ---

Proj Title=UNT 1023 IN LATR Base Level Engineering
Current Plan=p01
Default Exp/Contr=0.3,0.1
English Units
Geom File=g01
Flow File=f01
Plan File=p01
Y Axis Title=Elevation
X Axis Title(PF)=Main Channel Distance
X Axis Title(XS)=Station
BEGIN DESCRIPTION:
UNT 1023 IN LATR
END DESCRIPTION:
DSS Export Rating Curves= 0
DSS Export Rating Curve Sorted= 0
DSS Export Volume Flow Curves= 0
DXF OffsetX= 0
DXF OffsetY= 0
DXF ScaleX= 1
DXF ScaleY= 10

--- UNT 1023 IN LATR.p01 (plan) ---

Plan Title=Multiple Run
Short Identifier=Multiple
Geom File=g01
Flow File=f01
Subcritical Flow
K Sum by GR= 0
Std Step Tol= 0.01
Critical Tol= 0.01
Num of Std Step Trials= 20
Max Error Tol= 0.3
Flow Tol Ratio= 0.001
Split Flow NTrial= 30
Split Flow Tol= 0.02
Split Flow Ratio= 0.02
Log Output Level= 0
Friction Slope Method= 1
Unsteady Friction Slope Method= 2
Unsteady Bridges Friction Slope Method= 1
Parabolic Critical Depth
Global Vel Dist=  1 , 1 , 1
Global Log Level= 0
CheckData=True
Encroach Param= -1, 0, 0, 0
BEGIN DESCRIPTION:
Multiple Run
END DESCRIPTION:

--- UNT 1023 IN LATR.f01 (steady flow) ---

Flow Title=Multiple
Program Version=4.10
Number of Profiles= 7
Profile Names=10-year,25-year,50-year,1pct_min,100-year,1pct_plu,500-year
River Rch & RM=UNT 1023 IN LATR,Reach-1         ,24118
    1154    1703    2189    2061    2787    3769    4532
River Rch & RM=UNT 1023 IN LATR,Reach-1         ,20793
    1696    2550    3319    3158    4271    5777    7102
River Rch & RM=UNT 1023 IN LATR,Reach-1         ,16158
    2062    3111    4056    3861    5222    7062    8693
River Rch & RM=UNT 1023 IN LATR,Reach-1         ,5257
    3612    5576    7385    7130    9642   13040   16509
Boundary for River Rch & Prof#=UNT 1023 IN LATR,Reach-1         , 1
Up Type= 0
Dn Type= 3
Dn Slope=0.013
Boundary for River Rch & Prof#=UNT 1023 IN LATR,Reach-1         , 2
Up Type= 0
Dn Type= 3
Dn Slope=0.013
Boundary for River Rch & Prof#=UNT 1023 IN LATR,Reach-1         , 3
Up Type= 0
Dn Type= 3
Dn Slope=0.013
Boundary for River Rch & Prof#=UNT 1023 IN LATR,Reach-1         , 4
Up Type= 0
Dn Type= 3
Dn Slope=0.013
Boundary for River Rch & Prof#=UNT 1023 IN LATR,Reach-1         , 5
Up Type= 0
Dn Type= 3
Dn Slope=0.013
Boundary for River Rch & Prof#=UNT 1023 IN LATR,Reach-1         , 6
Up Type= 0
Dn Type= 3
Dn Slope=0.013
Boundary for River Rch & Prof#=UNT 1023 IN LATR,Reach-1         , 7
Up Type= 0
Dn Type= 3
Dn Slope=0.013
DSS Import GetInterval= 0
DSS Import GetPeak= 0
DSS Import FillOption= 0

--- UNT 1023 IN LATR.g01 (geometry) ---

Geom Title=Existing Conditions
Program Version=4.10

River Reach=UNT 1023 IN LATR,Reach-1
Reach XY= 30
      2887118.47     10038393.73      2887957.43     10038537.26
       2888048.8     10038732.75      2888407.28      10038496.1
      2888830.81     10038830.56      2889858.72     10039063.09
       2889886.1     10039416.06      2890661.79     10040407.05
      2891154.89     10040372.13      2891705.18     10041436.11
       2892103.1     10041353.73      2892085.43     10042151.76
      2892377.71     10042191.58      2892553.41     10041887.19
      2893256.89     10042140.24      2894276.11     10041296.57
      2894798.11     10041522.91      2895037.27     10041236.52
      2894904.89     10041963.24      2895355.16     10041753.73
      2896494.86     10042014.58      2896450.01     10042811.19
      2897967.62     10042897.16      2897741.75     10043342.43
      2898633.87     10044051.98      2899583.35     10043554.53
      2901387.08      10043770.4      2902128.44     10043077.72
      2902656.07      10041907.3      2902988.47     10041773.73

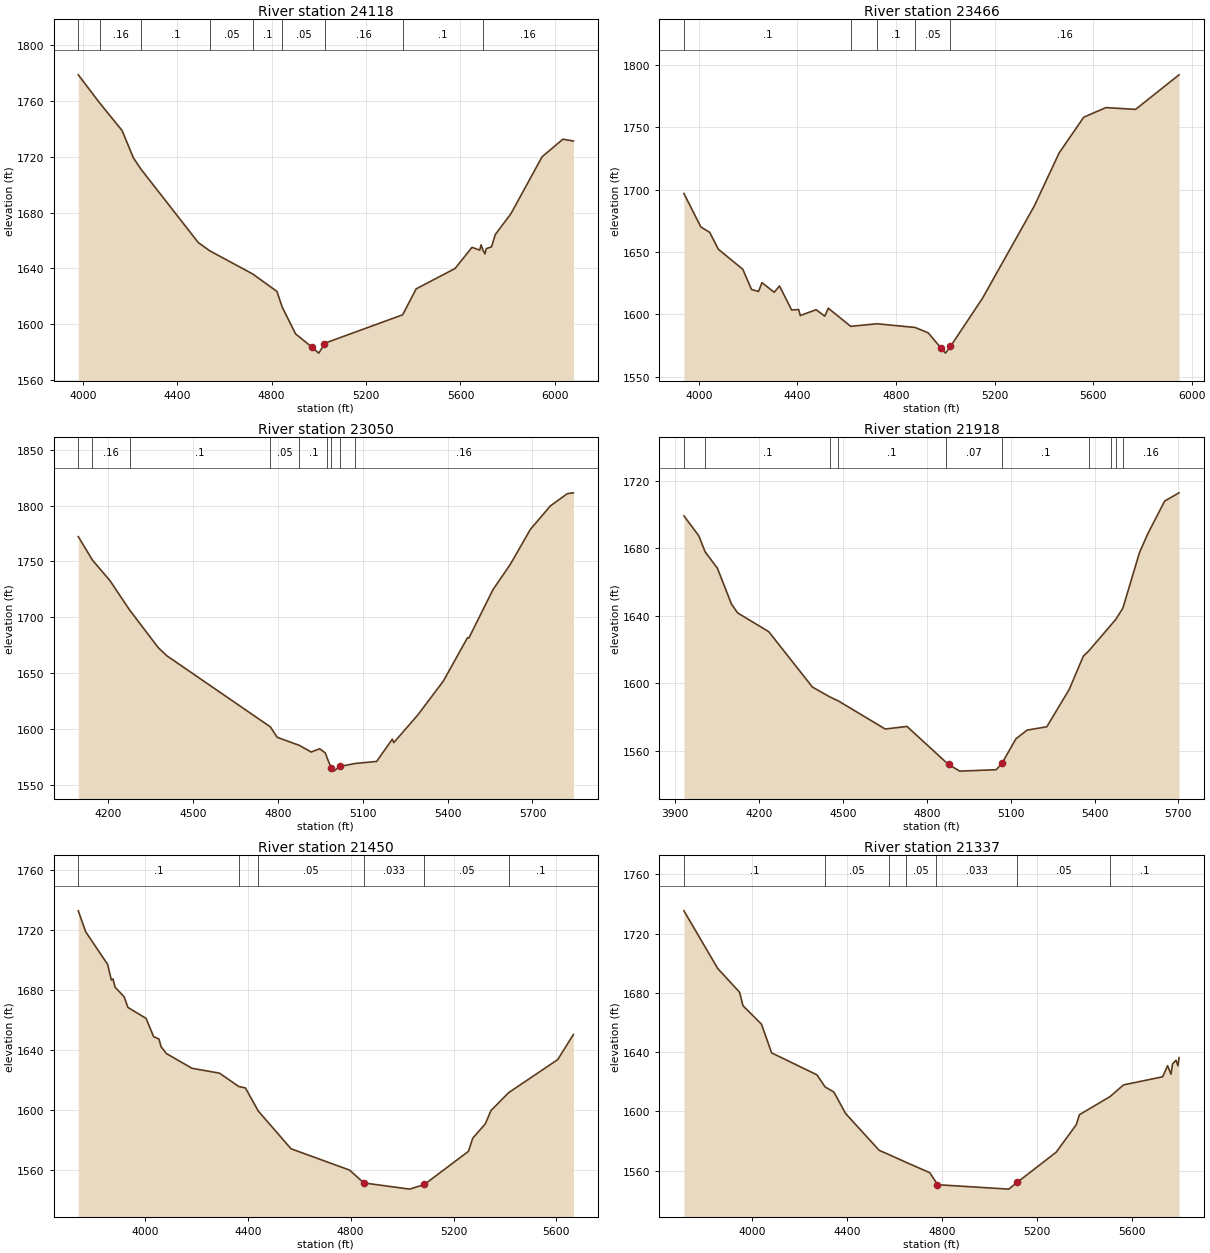
Type RM Length L Ch R = 1 ,24118   ,652,652,652
BEGIN DESCRIPTION:
UNT 1023 IN LATR 52.0
END DESCRIPTION:
XS GIS Cut Line= 3
      2886776.17     10039375.25       2887012.3     10038788.41
      2887696.31     10037493.31
#Sta/Elev= 30
    3981  1778.5  4072.4 1758.18  4166.3 1738.71  4214.6 1719.08    4247 1710.91
  4489.3 1658.51  4538.4 1652.58  4720.1 1636.04  4822.4 1623.57    4845 1612.29
  4901.6 1593.17  4969.4 1583.91  4999.3 1579.44  5023.9 1585.86  5027.3 1586.67
  5354.9 1606.85  5412.2  1625.4    5577 1639.98  5648.7  1655.1  5681.5 1653.11
  5687.1 1656.85  5696.5 1652.65  5703.5 1650.43  5709.1 1654.16  5731.2 1655.45
  5747.5 1664.28  5813.6 1679.16  5945.7 1719.91  6033.7 1732.45  6078.2 1731.17
#Mann= 9 ,-1 , 0
    3981      .1       0  4072.4     .16       0    4247      .1       0
  4538.4     .05       0  4720.1      .1       0    4845     .05       0
  5027.3     .16       0  5354.9      .1       0  5696.5     .16       0
Bank Sta=4969.4,5023.9
XS Rating Curve= 0 ,0
Exp/Cntr=0.3,0.1

Type RM Length L Ch R = 1 ,23466   ,416,416,416
BEGIN DESCRIPTION:
UNT 1023 IN LATR 51.0
END DESCRIPTION:
XS GIS Cut Line= 3
       2887151.2     10039343.95      2887779.66     10038646.05
      2887849.03     10037577.66
#Sta/Elev= 30
  3939.1 1696.91  4007.8 1670.09  4043.7 1665.75  4078.8 1652.21  4178.2  1636.1
  4213.4 1619.91  4241.8 1618.36    4256 1625.44  4305.3 1617.72    4327 1622.75
  4376.3 1603.48  4404.7 1603.89  4411.4 1599.04  4475.7 1603.72  4510.8 1598.56
    4525 1604.94    4616 1590.39  4722.6 1592.44  4877.4 1589.49  4930.7 1585.14
  4980.8  1573.4  5000.6 1568.89  5020.9 1574.25  5151.1 1612.93  5361.6    1687
  5461.8 1729.35    5562 1758.14  5652.2 1765.85  5772.5 1764.42  5948.9 1792.13
#Mann= 5 ,-1 , 0
  3939.1      .1       0    4616     .05       0  4722.6      .1       0
  4877.4     .05       0  5020.9     .16       0
Bank Sta=4980.8,5020.9
XS Rating Curve= 0 ,0
Exp/Cntr=0.3,0.1

Type RM Length L Ch R = 1 ,23050   ,1132,1132,1132
BEGIN DESCRIPTION:
UNT 1023 IN LATR 50.0
END DESCRIPTION:
XS GIS Cut Line= 3
      2888005.35     10039635.68      2888050.49     10038823.13
      2888154.66     10037892.55
#Sta/Elev= 30
  4094.5 1772.31  4144.4  1751.3  4206.6  1732.8  4275.6 1706.65  4376.9 1672.84
  4406.9 1665.59  4773.9 1601.65  4797.5 1592.37  4876.3 1585.12  4917.8 1579.17
    4948 1582.11  4968.1 1578.26  4974.7 1573.51  4988.2 1565.03    4998 1562.04
  5018.4 1566.19  5073.2 1568.91  5149.2 1570.72  5204.6 1590.73  5209.7 1587.59
  5294.9 1612.47  5385.1 1642.83  5470.3 1681.64  5475.3 1681.44  5560.5 1724.76
  5622.1 1747.59  5692.6 1778.78    5763 1799.77  5823.4 1810.84  5844.7 1811.57
#Mann= 9 ,-1 , 0
  4094.5      .1       0  4144.4     .16       0  4275.6      .1       0
  4773.9     .05       0  4876.3      .1       0  4974.7     .05       0
  4988.2    .035       0  5018.4     .05       0  5073.2     .16       0
Bank Sta=4988.2,5018.4
XS Rating Curve= 0 ,0
Exp/Cntr=0.3,0.1

Type RM Length L Ch R = 1 ,21918   ,468,468,468
BEGIN DESCRIPTION:
UNT 1023 IN LATR 49.0
END DESCRIPTION:
XS GIS Cut Line= 3
      2888567.84     10039823.15      2888928.96      10039114.8
      2889019.24     10038142.58
#Sta/Elev= 30
    3931 1699.13  3984.1 1687.35  4006.7 1677.85  4050.8 1668.08  4100.9 1646.91
  4123.2  1641.6  4234.3 1630.52  4390.6 1597.69  4452.7 1591.86  4483.7 1589.44
  4651.1  1572.8  4729.1 1574.34  4867.8 1553.22  4877.8 1551.79  4917.7 1547.84
  5048.5 1548.69  5068.6 1552.39  5118.8 1566.99    5159 1572.16  5229.3 1574.13
  5309.7 1596.32  5359.9 1615.97    5380 1619.19  5460.3 1634.71  5476.1  1637.8
  5501.4 1644.38  5560.7 1677.26  5590.9 1688.62  5651.1 1707.94  5702.5  1712.8
#Mann= 10 ,-1 , 0
    3931     .16       0  4006.7      .1       0  4452.7     .05       0
  4483.7      .1       0  4867.8     .07       0  5068.6      .1       0
    5380     .16       0  5460.3     .16       0  5476.1      .1       0
  5501.4     .16       0
Bank Sta=4877.8,5068.6
XS Rating Curve= 0 ,0
Exp/Cntr=0.3,0.1

Type RM Length L Ch R = 1 ,21450   ,113,113,113
BEGIN DESCRIPTION:
Mapping XS c78f4f3a
END DESCRIPTION:
XS GIS Cut Line= 4
      2888695.43     10039970.87      2889220.59     10039280.79
      2889533.09     10038664.47      2889355.13     10038343.27
#Sta/Elev= 30
  3740.8 1732.86  3769.6  1718.9  3854.9 1697.15  3869.4 1686.74  3875.7 1687.51
  3883.9 1681.98  3919.3 1675.51  3933.8 1668.49  4004.6 1661.14  4033.6 1649.04
  4054.5 1647.38  4062.7  1642.3  4083.5 1637.73  4183.4 1627.88  4290.1 1624.66
  4364.8 1615.77  4390.7 1614.82  4440.9  1599.4    4568 1574.27  4796.1 1560.03
  4851.3 1551.48  5029.6 1547.36  5086.8 1550.46  5258.1 1572.55  5274.8 1581.33
  5323.6 1590.86  5345.6 1599.69  5414.2 1611.64  5605.3  1633.7  5666.2 1650.43
#Mann= 6 ,-1 , 0
  3740.8      .1       0  4364.8     .05       0  4440.9     .05       0
  4851.3    .033       0  5086.8     .05       0  5414.2      .1       0
Bank Sta=4851.3,5086.8
XS Rating Curve= 0 ,0
Exp/Cntr=0.3,0.1

Type RM Length L Ch R = 1 ,21337   ,146,146,146
BEGIN DESCRIPTION:
Mapping XS 0e97c42a
END DESCRIPTION:
XS GIS Cut Line= 4
      2888730.65     10039986.42      2889421.59     10039184.37
      2889636.87     10038621.87      2889383.41     10038281.61
#Sta/Elev= 30
  3712.5 1735.45  3854.7 1696.56  3946.8  1680.5  3961.1 1671.41    4039 1658.95
  4081.8 1639.56  4272.7 1624.74    4307 1616.58    4344 1613.12  4393.4 1598.62
  4534.9 1573.77  4575.3 1570.96    4649 1565.63  4747.8 1558.69  4773.7 1552.38
  4776.8 1550.62  5080.3  1547.6  5115.9 1552.15  5280.2 1572.53    5365 1591.14
  5378.2 1597.85  5507.5 1610.11  5563.8 1617.96  5728.6 1623.43  5749.4 1630.92
    5764 1625.16  5770.2 1632.08  5784.8 1634.59  5793.2 1630.88  5797.7 1636.37
#Mann= 7 ,-1 , 0
  3712.5      .1       0    4307     .05       0  4575.3      .1       0
    4649     .05       0  4773.7    .033       0  5115.9     .05       0
  5507.5      .1       0
Bank Sta=4776.8,5115.9
XS Rating Curve= 0 ,0
Exp/Cntr=0.3,0.1

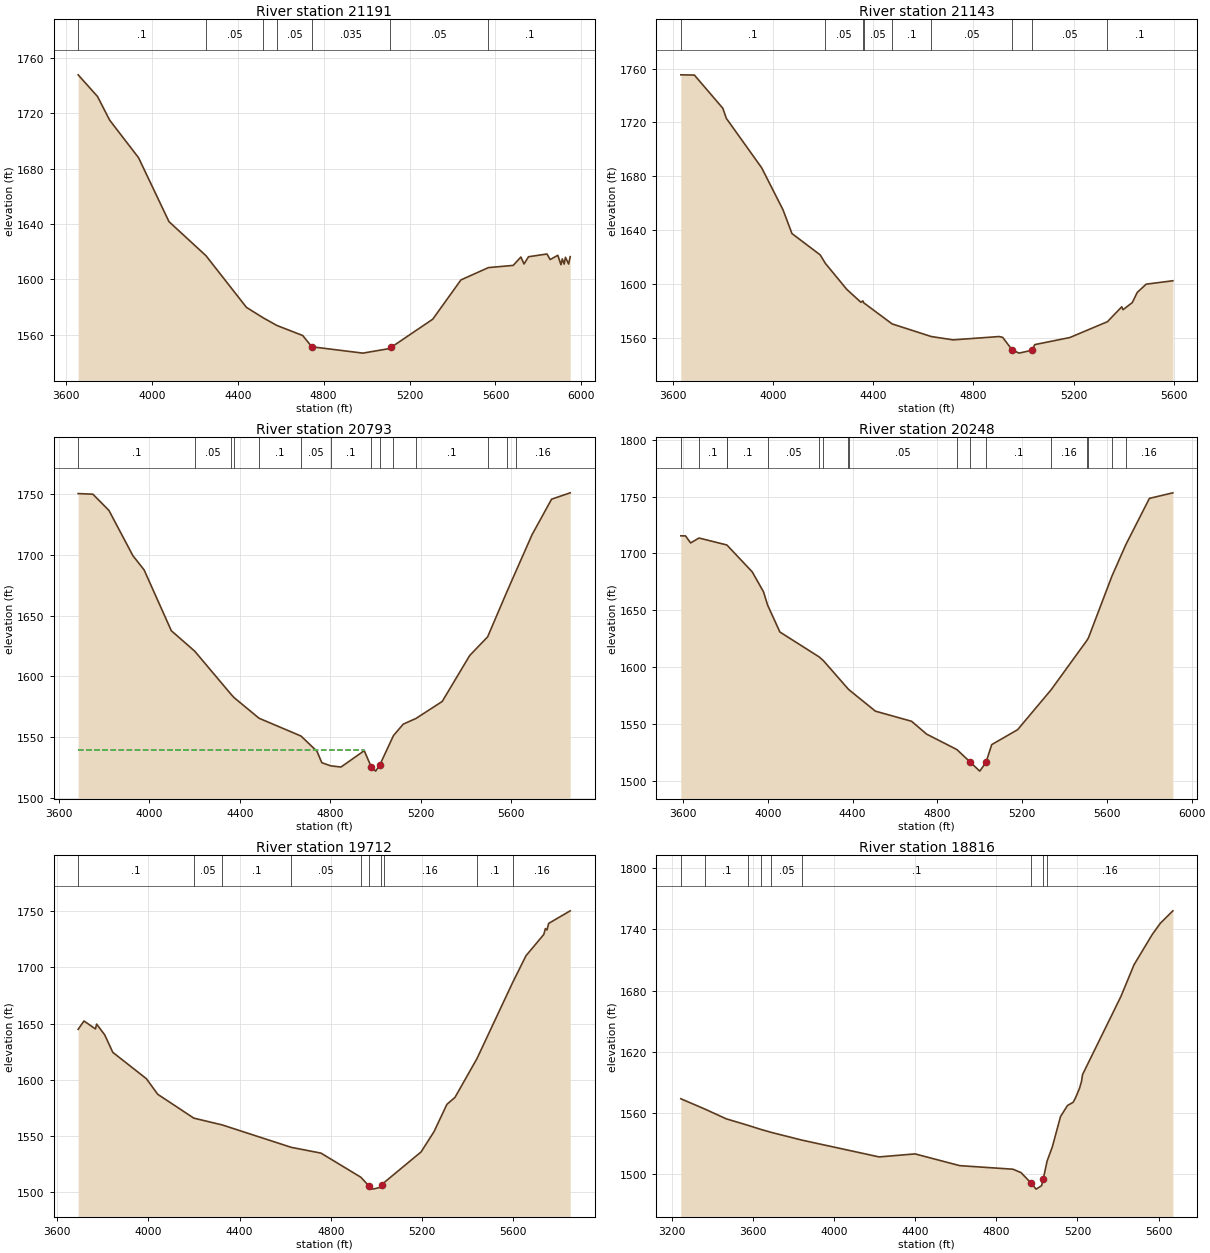
Type RM Length L Ch R = 1 ,21191   ,48,48,48
BEGIN DESCRIPTION:
UNT 1023 IN LATR 48.0
END DESCRIPTION:
XS GIS Cut Line= 5
      2888753.61     10040026.41      2889631.18     10039075.93
      2889655.45     10038903.48      2889683.66     10038621.36
      2889369.75     10038182.02
#Sta/Elev= 30
  3656.7 1747.54  3746.9 1731.93  3803.6 1714.84    3938 1687.78  4079.7 1641.69
  4252.2 1617.09  4440.4 1579.88  4518.5 1572.33  4582.1 1566.83  4702.3 1559.58
  4744.9 1551.46  4982.6 1546.88  5109.7 1550.26  5114.7  1551.1  5307.9 1571.34
  5439.3 1599.68  5567.1 1608.54  5682.6 1610.14  5718.3 1616.19    5733 1611.17
  5753.9 1616.38  5839.9 1618.36  5854.7 1614.34  5890.3 1617.43    5905 1610.64
  5911.2 1614.82  5919.8 1611.07  5925.9 1615.99  5940.7 1611.11    5948 1616.42
#Mann= 7 ,-1 , 0
  3656.7      .1       0  4252.2     .05       0  4518.5      .1       0
  4582.1     .05       0  4744.9    .035       0  5109.7     .05       0
  5567.1      .1       0
Bank Sta=4744.9,5114.7
XS Rating Curve= 0 ,0
Exp/Cntr=0.3,0.1

Type RM Length L Ch R = 1 ,21143   ,350,350,350
BEGIN DESCRIPTION:
UNT 1023 IN LATR 47.0
END DESCRIPTION:
XS GIS Cut Line= 4
       2888810.9     10040073.14      2889678.96      10039114.8
      2889716.21     10038607.25      2889619.64     10038473.78
#Sta/Elev= 30
  3630.4 1755.39  3684.6 1755.21  3798.2  1730.6  3812.4 1723.03  3953.6 1686.32
  4038.8 1655.16  4074.6 1637.51  4187.4 1621.68  4208.1 1615.38  4293.6 1596.08
  4350.3 1586.46  4358.1 1587.52  4361.2 1586.12    4475  1570.4  4631.7 1561.02
  4718.7 1558.56  4902.5 1561.02  4916.7 1560.43  4954.6 1551.14  4982.1 1548.71
  5034.8 1550.89  5044.8 1555.03  5185.2 1560.29  5335.6 1572.06  5392.8 1583.13
  5397.8 1580.95  5434.7 1586.24  5454.7 1593.78  5490.2 1599.92  5597.1 1602.45
#Mann= 9 ,-1 , 0
  3630.4      .1       0  4208.1     .05       0  4358.1      .1       0
  4361.2     .05       0    4475      .1       0  4631.7     .05       0
  4954.6    .035       0  5034.8     .05       0  5335.6      .1       0
Bank Sta=4954.6,5034.8
XS Rating Curve= 0 ,0
Exp/Cntr=0.3,0.1

Type RM Length L Ch R = 1 ,20793   ,545,545,545
BEGIN DESCRIPTION:
UNT 1023 IN LATR 46.0
END DESCRIPTION:
XS GIS Cut Line= 4
      2888904.58       10040102.      2889756.18     10039226.97
       2890269.2     10039143.64      2890620.78     10038891.02
#Sta/Elev= 30
  3686.3  1750.1  3751.5 1749.58  3822.3 1736.29  3928.3 1699.08  3977.7 1687.45
    4098 1637.51    4201 1620.79  4362.6 1585.15  4375.6 1582.55  4485.4 1565.69
    4671 1551.04  4741.6 1538.48  4762.7 1529.17  4802.2 1526.59  4847.6 1525.63
  4950.2 1539.06  4980.6 1525.95  5000.6 1522.26  5018.5 1527.16  5079.2 1551.42
  5122.4 1560.84  5178.4 1565.47  5294.6 1579.45  5416.2 1617.21  5495.3  1632.5
  5581.4 1669.96  5620.6  1686.5  5691.7 1716.43  5777.7 1745.49    5860 1750.71
#Mann= 14 ,-1 , 0
  3686.3      .1       0    4201     .05       0  4362.6      .1       0
  4375.6     .05       0  4485.4      .1       0    4671     .05       0
  4802.2      .1       0  4980.6     .07       0  5018.5      .1       0
  5079.2     .16       0  5178.4      .1       0  5495.3     .05       0
  5581.4      .1       0  5620.6     .16       0
#XS Ineff= 2 , 0
         4949.85 1539.62
Permanent Ineff=
       T       T
Bank Sta=4980.6,5018.5
XS Rating Curve= 0 ,0
Exp/Cntr=0.3,0.1

Type RM Length L Ch R = 1 ,20248   ,536,536,536
BEGIN DESCRIPTION:
UNT 1023 IN LATR 44.0
END DESCRIPTION:
XS GIS Cut Line= 3
      2888911.62      10040326.6      2889925.49     10039909.94
      2890654.08     10038924.61
#Sta/Elev= 30
  3589.9 1715.45  3612.1 1715.39    3636  1709.2  3675.8 1713.53  3805.7 1707.47
  3807.9 1707.26  3926.7 1683.77    3980 1666.19  3999.4 1654.48  4057.3  1630.8
  4242.6 1608.87  4262.3 1605.64  4378.9 1580.77  4385.3 1579.65    4508 1561.12
  4678.5 1552.23  4749.8 1540.89  4892.2 1527.35  4956.5  1516.1  5000.1 1508.34
  5029.6 1515.95  5056.7 1531.68  5178.8 1544.79    5337 1579.95  5505.4 1623.28
  5513.1 1625.66    5624 1680.04  5689.2 1707.56  5800.7 1748.42  5911.5 1753.31
#Mann= 17 ,-1 , 0
  3589.9     .16       0  3675.8      .1       0  3805.7     .16       0
  3807.9      .1       0  3999.4     .05       0  4242.6      .1       0
  4262.3     .05       0  4378.9      .1       0  4385.3     .05       0
  4892.2      .1       0  4956.5     .07       0  5029.6      .1       0
    5337     .16       0  5505.4      .1       0  5513.1     .05       0
    5624      .1       0  5689.2     .16       0
Bank Sta=4956.5,5029.6
XS Rating Curve= 0 ,0
Exp/Cntr=0.3,0.1

Type RM Length L Ch R = 1 ,19712   ,896,896,896
BEGIN DESCRIPTION:
Mapping XS 85743bd5
END DESCRIPTION:
XS GIS Cut Line= 3
      2889263.13     10040450.06      2890183.26     10040319.85
      2891076.87     10039478.29
#Sta/Elev= 30
  3692.7 1644.81  3718.3 1652.27  3768.6 1645.19  3773.7 1649.48  3809.2  1639.9
  3844.7 1624.35  3991.8 1600.93  4041.5 1587.05  4199.7 1565.84  4324.1  1559.8
  4626.8 1539.86  4757.3  1534.7  4931.6 1513.29  4969.7 1505.05  4983.6 1502.68
    5019  1504.3  5026.3 1506.72  5032.2 1508.26  5195.8 1535.77  5252.5 1553.78
  5309.1 1578.13  5344.3 1584.24  5440.7 1618.75  5597.1 1686.42  5655.9 1710.37
  5733.6 1729.19  5740.8 1734.48  5747.7 1733.22    5755 1739.06  5849.5 1750.26
#Mann= 10 ,-1 , 0
  3692.7      .1       0  4199.7     .05       0  4324.1      .1       0
  4626.8     .05       0  4931.6      .1       0  4969.7     .07       0
    5019      .1       0  5032.2     .16       0  5440.7      .1       0
  5597.1     .16       0
Bank Sta=4969.7,5026.3
XS Rating Curve= 0 ,0
Exp/Cntr=0.3,0.1

Type RM Length L Ch R = 1 ,18816   ,676,676,676
BEGIN DESCRIPTION:
UNT 1023 IN LATR 41.0
END DESCRIPTION:
XS GIS Cut Line= 3
      2889946.31     10041597.45      2891001.88     10040736.33
      2891279.63     10039708.66
#Sta/Elev= 30
  3244.1 1574.02    3362 1563.97  3468.1 1554.35  3574.4 1548.03  3638.8 1543.97
  3689.8 1541.07  3840.6  1533.5  4222.1 1516.99  4399.4 1519.95  4619.4 1508.45
  4882.1 1504.94    4922 1501.61  4971.6 1491.31  4996.4 1485.41  5023.4  1488.8
  5031.3 1495.12  5050.5 1512.95  5076.4 1526.89  5116.6 1556.51    5151 1567.39
  5178.8 1570.53  5190.8    1575  5209.9    1584  5220.2 1590.96  5225.5  1597.8
  5414.6 1674.33  5479.2  1705.4  5568.9 1735.05  5608.8 1746.07  5670.9 1758.29
#Mann= 9 ,-1 , 0
  3244.1     .05       0    3362      .1       0  3574.4     .05       0
  3638.8      .1       0  3689.8     .05       0  3840.6      .1       0
  4971.6     .07       0  5031.3      .1       0  5050.5     .16       0
Bank Sta=4971.6,5031.3
XS Rating Curve= 0 ,0
Exp/Cntr=0.3,0.1

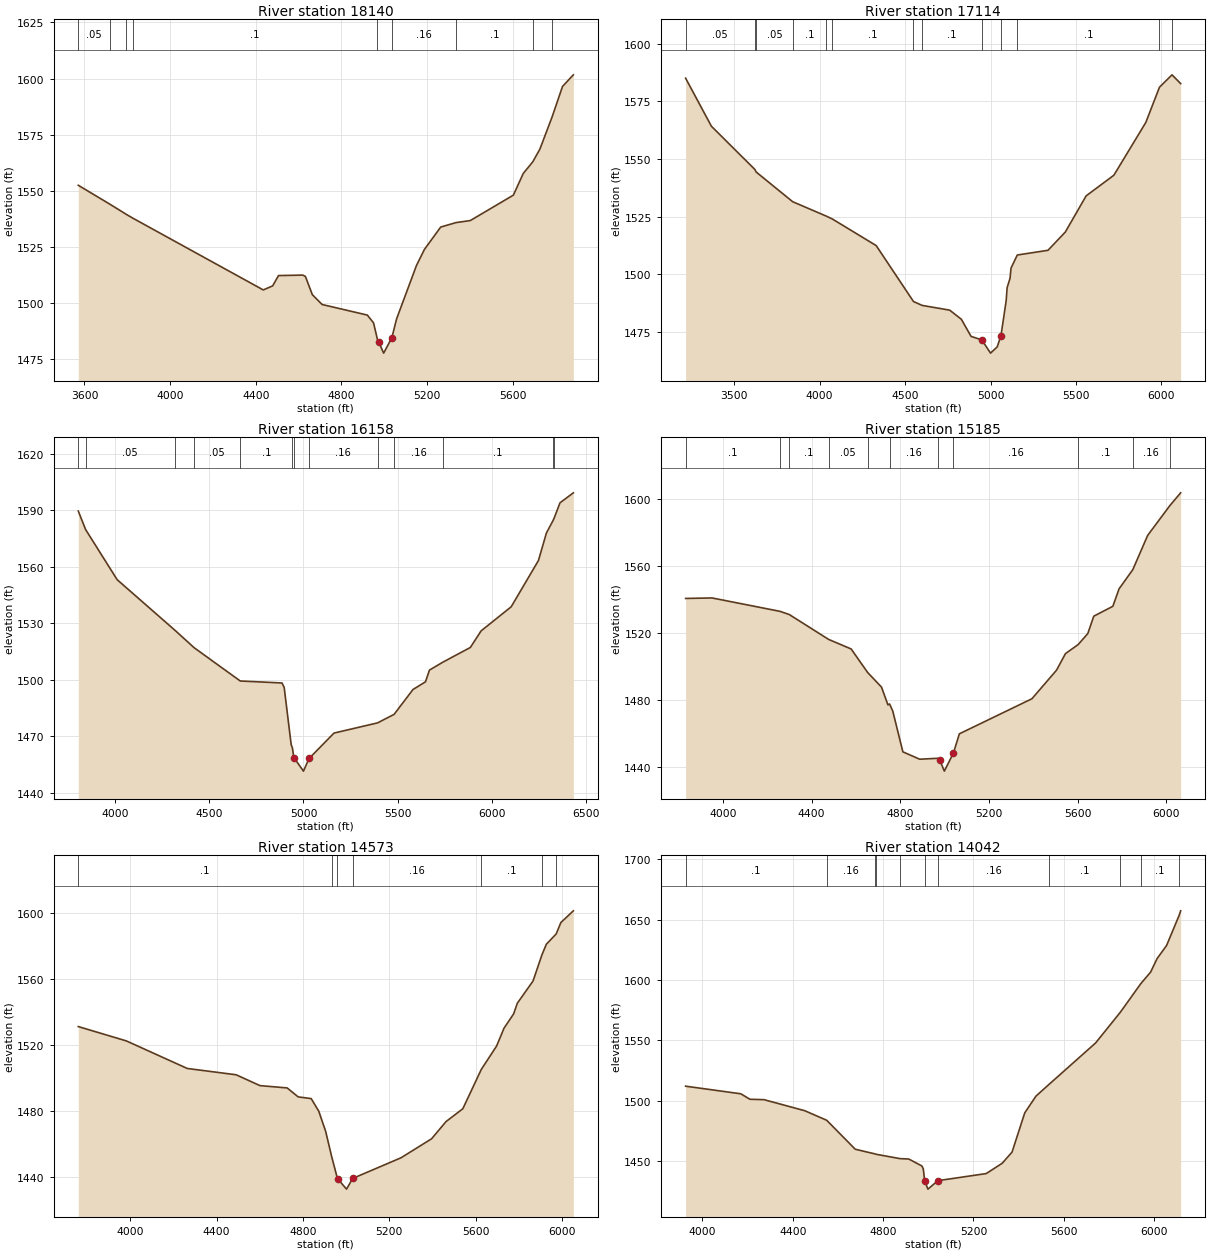
Type RM Length L Ch R = 1 ,18140   ,1026,1026,1026
BEGIN DESCRIPTION:
UNT 1023 IN LATR 39.0
END DESCRIPTION:
XS GIS Cut Line= 4
      2890217.16     10041541.88      2891203.27     10041007.16
      2891744.93       10040778.      2891890.77     10040194.66
#Sta/Elev= 30
  3571.2 1552.43    3717 1544.09  3795.6 1539.46  3825.3  1537.8  4434.7 1505.78
  4478.5 1507.58    4506 1512.18  4619.2 1512.39  4631.5  1511.8  4663.9 1503.67
  4709.3 1499.29  4920.6 1494.57  4949.7 1491.09  4967.9 1483.65  4973.4 1482.64
  4996.8 1477.61  5035.2  1484.5  5056.9 1492.79  5150.1  1516.7  5187.2 1523.84
  5263.2 1533.81    5335  1535.8  5401.4  1536.7  5602.4 1548.03  5648.8 1557.73
    5693 1562.88  5726.1 1568.51  5783.4 1582.93  5831.8 1596.47  5882.4 1601.66
#Mann= 9 ,-1 , 0
  3571.2     .05       0    3717      .1       0  3795.6     .05       0
  3825.3      .1       0  4967.9     .07       0  5035.2     .16       0
    5335      .1       0    5693     .16       0  5783.4      .1       0
Bank Sta=4973.4,5035.2
XS Rating Curve= 0 ,0
Exp/Cntr=0.3,0.1

Type RM Length L Ch R = 1 ,17114   ,956,956,956
BEGIN DESCRIPTION:
UNT 1023 IN LATR 37.0
END DESCRIPTION:
XS GIS Cut Line= 4
      2890994.94     10042743.27      2891967.16     10041618.27
      2892231.05     10041055.77      2892099.17     10040278.39
#Sta/Elev= 30
  3215.6    1585  3366.6 1564.19  3620.6 1545.49  3628.8 1544.35  3841.9 1531.52
  4038.3 1525.29  4074.7 1524.01  4330.8 1512.51    4549  1488.3  4599.7 1486.61
  4760.8 1484.56    4829 1480.62    4886 1473.19  4948.9 1471.68  4999.8 1465.95
  5038.9 1468.65    5061 1473.58  5091.3 1488.64  5096.8 1494.26  5114.1  1498.4
  5119.7 1502.76  5156.4 1508.43    5336 1510.47  5437.4 1518.38  5559.2 1534.04
  5721.4 1542.97  5908.2  1565.8  5988.4 1581.09  6061.7 1586.45  6112.3 1582.65
#Mann= 13 ,-1 , 0
  3215.6     .05       0  3620.6      .1       0  3628.8     .05       0
  3841.9      .1       0  4038.3     .05       0  4074.7      .1       0
    4549     .05       0  4599.7      .1       0  4948.9     .07       0
    5061     .16       0  5156.4      .1       0  5988.4     .16       0
  6061.7      .1       0
Bank Sta=4948.9,5061
XS Rating Curve= 0 ,0
Exp/Cntr=0.3,0.1

Type RM Length L Ch R = 1 ,16158   ,973,973,973
BEGIN DESCRIPTION:
UNT 1023 IN LATR 35.0
END DESCRIPTION:
XS GIS Cut Line= 4
      2891800.48      10043305.8       2892161.6     10042389.11
      2892293.55     10041798.83        2892863.     10040930.75
#Sta/Elev= 30
  3804.4 1589.64  3843.6 1579.78  4010.8 1553.19  4316.5 1526.42  4419.3 1517.07
  4664.4 1499.37  4886.1 1498.32  4897.6  1495.9  4934.6 1465.61  4941.2 1463.79
  4948.9  1458.7  4999.9 1451.49  5026.6 1457.58  5031.7 1458.41  5161.9  1471.7
  5393.3 1477.12  5481.1 1481.65  5581.3 1494.85  5647.7 1498.94  5668.8 1505.17
  5740.4  1509.4  5885.8 1517.18    5943    1526  6102.8 1538.81  6247.5 1563.39
  6289.6 1577.97  6322.3 1584.11  6329.4 1585.55    6362 1594.05  6432.7 1599.34
#Mann= 13 ,-1 , 0
  3804.4      .1       0  3843.6     .05       0  4316.5      .1       0
  4419.3     .05       0  4664.4      .1       0  4941.2     .16       0
  4948.9     .07       0  5026.6     .16       0  5393.3      .1       0
  5481.1     .16       0  5740.4      .1       0  6322.3     .16       0
  6329.4      .1       0
Bank Sta=4948.9,5031.7
XS Rating Curve= 0 ,0
Exp/Cntr=0.3,0.1

Type RM Length L Ch R = 1 ,15185   ,612,612,612
BEGIN DESCRIPTION:
UNT 1023 IN LATR 32.0
END DESCRIPTION:
XS GIS Cut Line= 4
      2892960.21     10043222.46      2892876.88     10042416.88
      2893001.88     10041625.22      2892925.59     10041007.96
#Sta/Elev= 30
  3831.7 1540.69  3951.1 1540.98  4257.9 1532.98  4299.3 1531.09  4477.1 1516.22
  4578.5 1510.53  4652.9 1496.49  4715.6 1487.73  4744.4 1477.16  4751.8  1477.7
  4766.3 1473.43  4811.9 1449.11  4887.7 1444.71  4968.7 1445.26  4978.9  1444.1
  4998.8  1437.6  5039.6 1448.31  5066.7 1459.87    5394 1480.81    5505 1497.85
  5545.3 1507.75  5602.6 1513.16  5646.1 1519.72    5673  1530.1  5759.1    1536
  5787.1 1546.41  5849.1 1557.88  5916.2 1578.33  6016.6 1596.18    6065 1603.74
#Mann= 11 ,-1 , 0
  3831.7      .1       0  4257.9     .05       0  4299.3      .1       0
  4477.1     .05       0  4652.9      .1       0  4751.8     .16       0
  4968.7     .07       0  5039.6     .16       0  5602.6      .1       0
  5849.1     .16       0  6016.6      .1       0
Bank Sta=4978.9,5039.6
XS Rating Curve= 0 ,0
Exp/Cntr=0.3,0.1

Type RM Length L Ch R = 1 ,14573   ,531,531,531
BEGIN DESCRIPTION:
UNT 1023 IN LATR 31.0
END DESCRIPTION:
XS GIS Cut Line= 3
      2893717.16     10043180.78      2893619.93     10042271.05
      2893008.84     10041034.97
#Sta/Elev= 30
  3759.4 1530.98  3982.5 1522.26  4264.5 1505.59  4490.6 1501.78  4601.2 1495.21
  4727.1 1493.81  4778.2 1488.38  4838.6 1487.34  4873.6 1479.73  4905.6 1467.52
  4933.2 1452.33  4957.7 1440.12  4963.3 1438.43  5002.4 1432.51  5030.6 1438.97
    5255 1451.51  5396.4 1463.01  5463.3 1473.43  5541.1 1481.19  5626.6 1504.99
  5697.6 1519.19  5731.8 1529.95  5776.6 1538.68  5793.5 1545.08  5866.4 1558.56
  5907.8 1574.46  5928.1 1580.84  5973.7 1587.09  5995.4 1593.98  6053.2 1601.08
#Mann= 7 ,-1 , 0
  3759.4      .1       0  4933.2     .16       0  4957.7     .07       0
  5030.6     .16       0  5626.6      .1       0  5907.8     .16       0
  5973.7      .1       0
Bank Sta=4963.3,5030.6
XS Rating Curve= 0 ,0
Exp/Cntr=0.3,0.1

Type RM Length L Ch R = 1 ,14042   ,1021,1021,1021
BEGIN DESCRIPTION:
UNT 1023 IN LATR 30.0
END DESCRIPTION:
XS GIS Cut Line= 3
      2894064.38     10042687.74      2894106.05     10041937.72
      2893232.26     10040793.47
#Sta/Elev= 30
  3926.1 1512.09  4170.5 1505.79  4210.5 1501.27  4272.9 1500.94  4453.2 1491.81
  4550.5  1483.9  4676.8 1459.92  4763.2  1456.1  4769.7 1455.74    4875 1452.15
  4913.6 1451.83  4971.7 1446.09    4978 1443.65  4984.3  1433.5  4998.6 1426.91
  5042.5 1433.91  5256.5 1439.78  5327.2 1448.31  5370.8 1457.56    5427 1490.01
  5476.8  1503.9  5535.3 1513.72  5740.8  1547.9  5850.1  1573.3  5941.5 1597.15
  5983.9 1606.45  6012.9 1617.74  6054.6 1628.47  6110.8 1653.68    6117 1657.19
#Mann= 11 ,-1 , 0
  3926.1      .1       0  4550.5     .16       0  4763.2      .1       0
  4769.7     .16       0    4875      .1       0  4984.3     .07       0
  5042.5     .16       0  5535.3      .1       0  5850.1     .16       0
  5941.5      .1       0  6110.8     .16       0
Bank Sta=4984.3,5042.5
XS Rating Curve= 0 ,0
Exp/Cntr=0.3,0.1

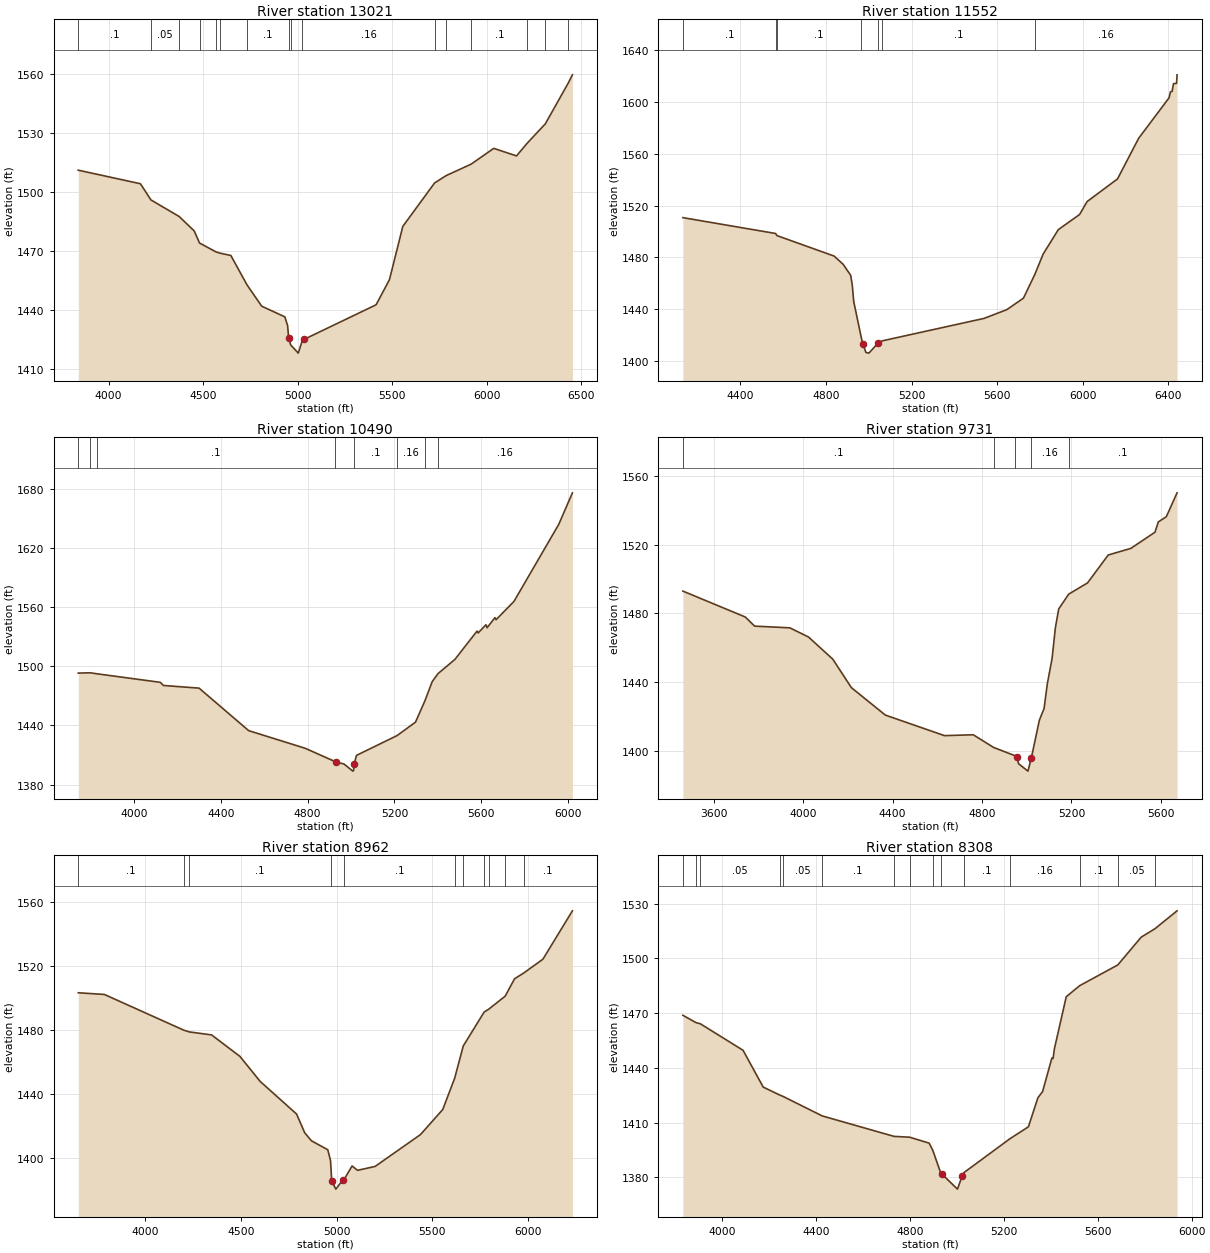
Type RM Length L Ch R = 1 ,13021   ,1469,1469,1469
BEGIN DESCRIPTION:
UNT 1023 IN LATR 28.0
END DESCRIPTION:
XS GIS Cut Line= 4
      2894217.16     10042555.77      2894571.32     10041854.38
      2894689.38     10041257.16      2893814.35     10040409.91
#Sta/Elev= 30
  3839.9 1511.04  4168.6 1504.15  4224.2 1495.94  4373.4 1487.52  4452.8 1480.21
  4481.3 1474.03  4568.7 1469.53  4589.1 1468.92  4646.7 1467.72  4732.2 1452.79
  4809.8 1441.98  4932.1 1436.57  4946.7 1432.12  4952.5 1425.78  4962.7 1422.36
  5003.2 1418.15  5023.8 1424.39    5034 1425.14  5414.4 1442.69  5485.1 1455.43
  5555.8  1482.5  5723.8 1504.56    5785 1508.29  5916.9  1514.1  6036.6 1522.11
  6156.8 1518.28  6214.4 1524.84  6309.1 1534.55  6430.9 1555.37  6452.4 1559.45
#Mann= 16 ,-1 , 0
  3839.9      .1       0  4224.2     .05       0  4373.4      .1       0
  4481.3     .16       0  4568.7      .1       0  4589.1     .16       0
  4732.2      .1       0  4952.5     .16       0  4962.7     .07       0
  5023.8     .16       0  5723.8      .1       0    5785     .05       0
  5916.9      .1       0  6214.4     .05       0  6309.1      .1       0
  6430.9     .16       0
Bank Sta=4952.5,5034
XS Rating Curve= 0 ,0
Exp/Cntr=0.3,0.1

Type RM Length L Ch R = 1 ,11552   ,1062,1062,1062
BEGIN DESCRIPTION:
UNT 1023 IN LATR 25.0
END DESCRIPTION:
XS GIS Cut Line= 2
      2894314.35     10042597.47      2895854.78     10040876.63
#Sta/Elev= 30
  4131.2 1510.72  4564.5 1498.46  4570.8 1496.83  4837.7 1481.01  4880.3 1474.63
  4915.4 1466.11  4922.9 1458.43  4929.7 1445.77  4965.6 1417.47  4972.3 1413.19
  4986.5 1406.47  5000.4 1405.93  5043.3 1413.65    5063 1415.42    5539  1432.8
  5645.2 1439.56  5722.9 1448.46    5776 1466.78  5814.9 1482.53  5885.9 1501.45
  5985.3 1513.16  6020.5 1523.17  6162.5 1540.67  6261.2 1572.06  6403.3 1603.37
    6410 1608.03  6417.5 1608.32  6424.2 1614.33  6438.4  1614.6  6440.8 1621.17
#Mann= 7 ,-1 , 0
  4131.2      .1       0  4564.5     .05       0  4570.8      .1       0
  4965.6     .07       0  5043.3     .16       0    5063      .1       0
    5776     .16       0
Bank Sta=4972.3,5043.3
XS Rating Curve= 0 ,0
Exp/Cntr=0.3,0.1

Type RM Length L Ch R = 1 ,10490   ,759,759,759
BEGIN DESCRIPTION:
UNT 1023 IN LATR 23.0
END DESCRIPTION:
XS GIS Cut Line= 3
      2895092.17      10042764.1      2895737.99     10042312.72
      2896099.05     10040868.49
#Sta/Elev= 30
  3743.5 1493.15  3798.7 1493.46  3829.3 1492.45  4121.4 1483.78  4136.2 1480.58
  4300.2 1477.87  4528.7 1434.72  4788.1 1416.88  4926.2 1403.37  4932.4 1402.65
  4967.4 1400.91  5008.4 1393.61  5011.6 1394.11  5014.8 1400.94  5025.2 1409.58
  5212.5 1429.73  5297.2 1443.34  5340.4 1464.93  5374.5 1484.62  5401.1 1492.64
  5478.7 1507.03  5580.7 1535.81  5585.9 1533.91  5621.9 1542.27  5627.1 1539.22
  5663.2 1549.46  5668.3 1547.36  5750.8 1565.92  5956.9 1644.07  6020.1 1676.19
#Mann= 8 ,-1 , 0
  3743.5      .1       0  3798.7     .05       0  3829.3      .1       0
  4926.2     .07       0  5014.8      .1       0  5212.5     .16       0
  5340.4      .1       0  5401.1     .16       0
Bank Sta=4932.4,5014.8
XS Rating Curve= 0 ,0
Exp/Cntr=0.3,0.1

Type RM Length L Ch R = 1 ,9731    ,769,769,769
BEGIN DESCRIPTION:
UNT 1023 IN LATR 21.0
END DESCRIPTION:
XS GIS Cut Line= 3
      2895182.43     10042757.16      2896231.05     10042305.77
      2897113.01     10041701.59
#Sta/Elev= 30
  3461.6 1492.99  3740.8 1477.89  3782.4 1472.59    3940 1471.59  4023.4 1466.26
  4132.3 1453.33  4215.2 1436.78  4367.2 1420.78  4631.9 1408.81  4760.5 1409.32
  4851.6 1401.94  4948.7 1397.04  4954.8 1396.55  4963.6 1392.41  5005.3 1388.14
  5020.5 1395.89  5056.4 1417.83  5077.3 1424.58  5092.2 1439.22  5113.2 1453.77
  5128.1 1471.79    5143  1482.6  5187.6 1491.23  5271.6 1497.73  5364.3    1514
  5465.9 1517.88  5573.5 1527.28  5588.4 1533.26  5624.3 1536.33  5672.3 1550.22
#Mann= 5 ,-1 , 0
  3461.6      .1       0  4851.6     .16       0  4948.7     .07       0
  5020.5     .16       0  5187.6      .1       0
Bank Sta=4954.8,5020.5
XS Rating Curve= 0 ,0
Exp/Cntr=0.3,0.1

Type RM Length L Ch R = 1 ,8962    ,654,654,654
BEGIN DESCRIPTION:
UNT 1023 IN LATR 20.0
END DESCRIPTION:
XS GIS Cut Line= 4
      2895279.69     10043409.93      2896217.16     10043083.55
      2896703.27       10042528.      2897112.81     10041778.33
#Sta/Elev= 30
  3648.9 1503.26  3785.3 1502.21  4201.9 1479.88  4230.2 1478.83  4346.5 1476.96
  4494.7 1463.57  4600.6 1447.94    4791  1427.6  4833.7  1415.9  4868.8 1410.91
  4954.2 1405.31  4968.5 1398.65  4975.1 1385.61  4996.7 1380.75    5032  1386.4
  5039.6 1386.75  5081.4 1395.19  5109.9 1392.48  5201.9 1394.92  5439.3 1414.79
  5555.5 1430.39  5618.2    1450    5663 1470.06  5772.5 1491.28  5795.2 1492.91
    5882 1501.12  5931.6 1512.01  5978.7 1515.53  6079.7 1524.21    6234 1554.38
#Mann= 11 ,-1 , 0
  3648.9      .1       0  4201.9     .05       0  4230.2      .1       0
  4968.5     .07       0  5039.6      .1       0  5618.2     .16       0
    5663      .1       0  5772.5     .05       0  5795.2      .1       0
    5882     .05       0  5978.7      .1       0
Bank Sta=4975.1,5032
XS Rating Curve= 0 ,0
Exp/Cntr=0.3,0.1

Type RM Length L Ch R = 1 ,8308    ,492,492,492
BEGIN DESCRIPTION:
UNT 1023 IN LATR 18.0
END DESCRIPTION:
XS GIS Cut Line= 3
      2896585.21     10043889.11      2897050.49     10043250.22
      2897189.38     10041944.65
#Sta/Elev= 30
  3834.7  1468.8  3890.6 1464.78  3909.4 1464.11  4090.7 1449.61  4176.5 1429.43
  4247.7 1425.01  4261.4 1424.29  4427.5 1413.62    4733  1402.4  4800.1 1401.93
    4883 1398.67  4898.5 1394.69  4932.5 1382.17  4937.5 1381.65  5003.4 1373.46
  5023.8 1380.91  5030.1 1382.44  5226.3 1401.06  5305.4 1407.65  5345.6 1423.54
  5365.7    1427  5405.2 1445.34  5410.2 1445.07    5416 1450.47  5466.3 1478.96
  5523.5 1485.04  5685.7  1496.4  5785.3 1511.64  5844.4 1516.32    5938 1526.09
#Mann= 15 ,-1 , 0
  3834.7     .05       0  3890.6      .1       0  3909.4     .05       0
  4247.7      .1       0  4261.4     .05       0  4427.5      .1       0
    4733     .05       0  4800.1      .1       0  4898.5     .05       0
  4932.5     .07       0  5030.1      .1       0  5226.3     .16       0
  5523.5      .1       0  5685.7     .05       0  5844.4      .1       0
Bank Sta=4937.5,5023.8
XS Rating Curve= 0 ,0
Exp/Cntr=0.3,0.1