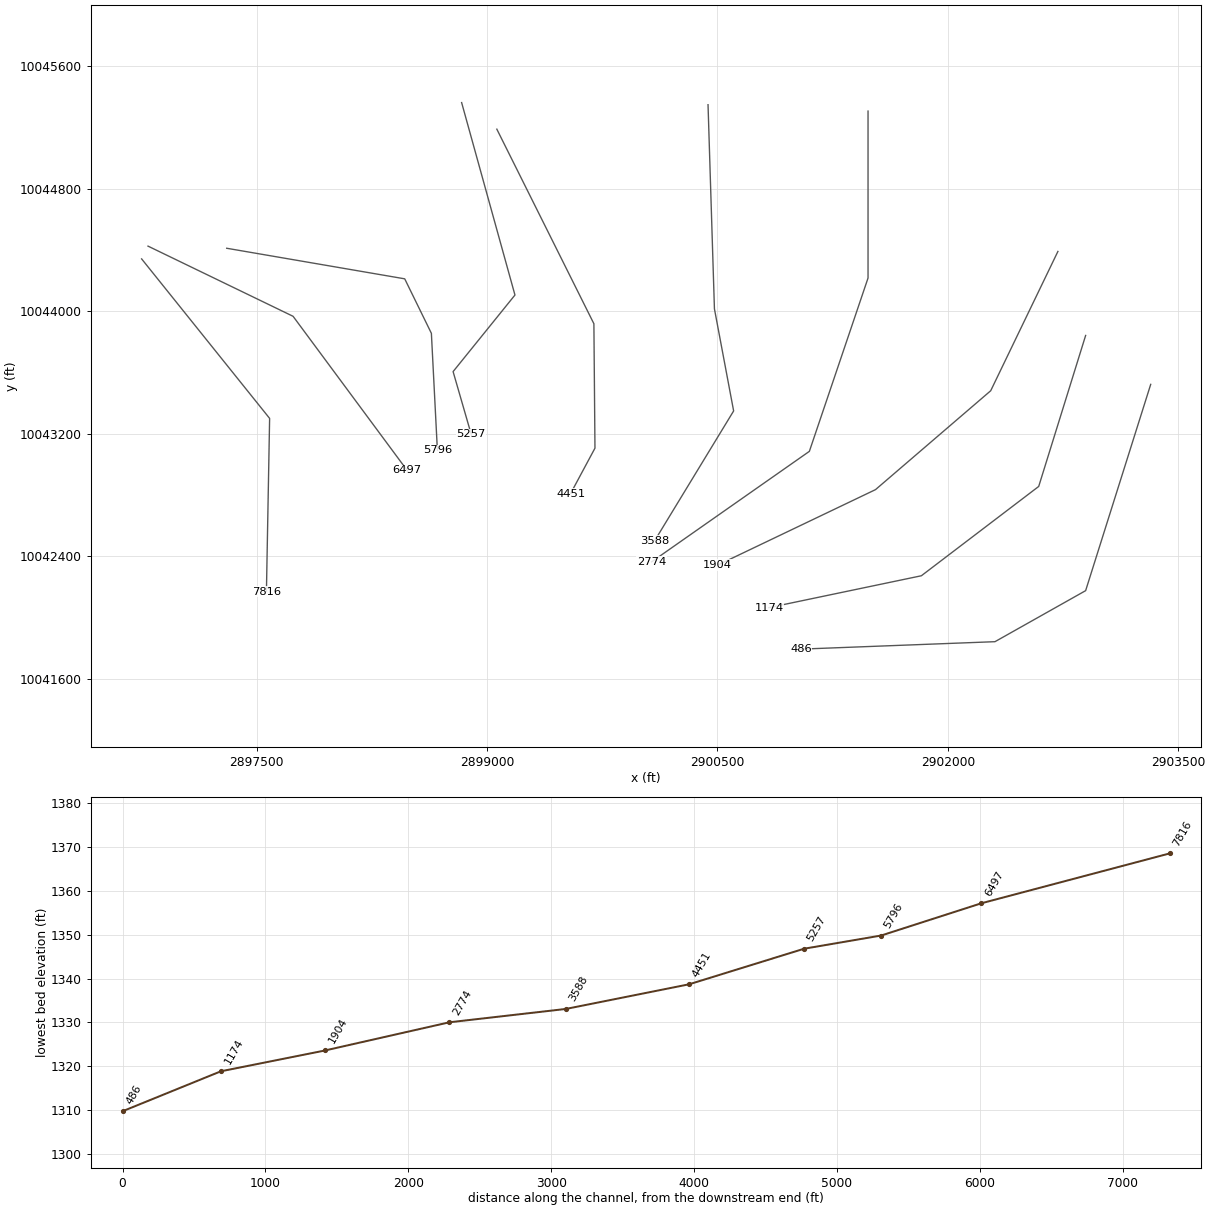
HEC-RAS study UNT 1023 IN LATR.prj: UNT 1023 IN LATR Base Level Engineering

--- UNT 1023 IN LATR.g01 (geometry) --- (continued)

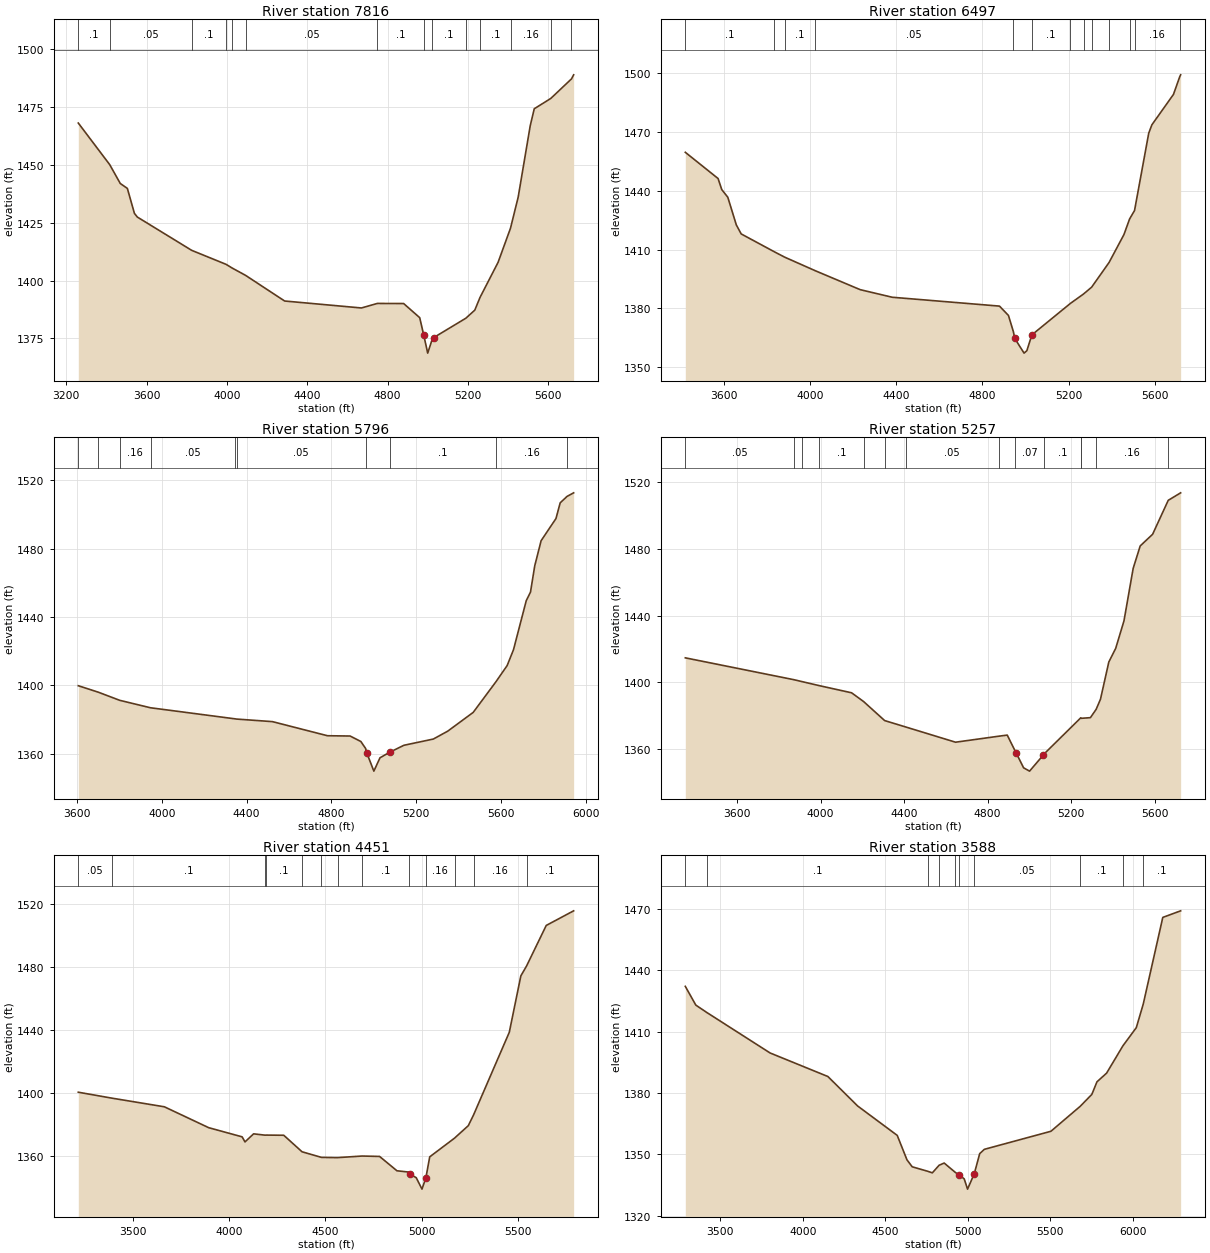
Type RM Length L Ch R = 1 ,7816    ,1319,1319,1319
BEGIN DESCRIPTION:
UNT 1023 IN LATR 17.0
END DESCRIPTION:
XS GIS Cut Line= 3
       2896751.9     10044340.47      2897585.21     10043298.83
       2897564.4     10042167.77
#Sta/Elev= 30
  3260.3 1468.11  3416.8  1450.1  3469.2 1441.97  3504.4 1439.85  3539.6 1429.05
    3554 1427.46  3824.7 1413.05  3995.5 1407.01  4024.8 1405.46  4092.5 1402.25
  4287.2 1391.14  4669.4 1388.13  4748.4 1390.09  4879.4 1390.05  4959.4 1383.94
  4979.4 1376.42  4999.2  1368.6  5019.4 1373.99  5029.4 1375.34  5188.9 1383.69
  5233.5 1387.19  5259.9 1392.75  5349.5 1407.88  5411.3 1422.64  5449.5 1436.08
  5509.5 1466.98  5529.5 1474.29  5611.7 1478.75  5714.8 1487.22  5725.5 1488.97
#Mann= 14 ,-1 , 0
  3260.3      .1       0  3416.8     .05       0  3824.7      .1       0
  3995.5     .05       0  4024.8      .1       0  4092.5     .05       0
  4748.4      .1       0  4979.4     .07       0  5019.4      .1       0
  5188.9     .05       0  5259.9      .1       0  5411.3     .16       0
  5611.7      .1       0  5714.8     .05       0
Bank Sta=4979.4,5029.4
XS Rating Curve= 0 ,0
Exp/Cntr=0.3,0.1

Type RM Length L Ch R = 1 ,6497    ,701,701,701
BEGIN DESCRIPTION:
UNT 1023 IN LATR 14.0
END DESCRIPTION:
XS GIS Cut Line= 3
      2896793.55     10044423.83      2897737.99      10043965.5
      2898480.98     10042958.64
#Sta/Elev= 30
  3419.7 1459.72    3572 1446.33    3589  1440.7  3617.1 1436.78  3656.7 1422.65
  3679.3 1418.06  3831.9 1409.02  3881.5 1406.19  4023.1 1399.29    4232 1389.61
  4381.1 1385.73  4879.2 1381.21  4920.9 1376.44  4943.9 1368.11  4950.2 1364.69
  4993.4 1357.21  5006.5 1358.48  5029.6 1366.52  5208.8  1382.6  5269.6 1387.38
  5307.3 1390.88  5388.1 1403.45  5457.6 1417.78  5483.6 1425.69  5506.6    1430
  5572.5 1469.46  5587.1 1473.74  5687.4 1489.27  5716.9 1498.39  5720.8 1499.27
#Mann= 13 ,-1 , 0
  3419.7      .1       0  3831.9     .05       0  3881.5      .1       0
  4023.1     .05       0  4943.9     .07       0  5029.6      .1       0
  5208.8     .05       0  5269.6      .1       0  5307.3     .05       0
  5388.1     .16       0  5483.6      .1       0  5506.6     .16       0
  5716.9      .1       0
Bank Sta=4950.2,5029.6
XS Rating Curve= 0 ,0
Exp/Cntr=0.3,0.1

Type RM Length L Ch R = 1 ,5796    ,539,539,539
BEGIN DESCRIPTION:
UNT 1023 IN LATR 13.0
END DESCRIPTION:
XS GIS Cut Line= 4
       2897305.9     10044409.91      2898464.73     10044210.26
      2898638.34     10043854.36       2898677.4     10043090.45
#Sta/Elev= 30
  3606.3 1399.81  3700.8 1396.02  3801.6 1391.27    3947 1386.91  4343.8 1380.47
  4352.7 1380.31  4522.2  1378.8  4781.6 1370.56  4888.7 1370.38  4939.3 1367.18
  4961.9 1363.07  4967.5 1360.43  5000.6 1349.85  5029.5 1357.65  5074.5 1360.84
  5142.1 1364.96  5281.3 1368.62    5349 1373.22  5469.2  1384.2    5576 1402.04
  5629.4  1411.6  5659.4 1420.89  5719.5 1449.56  5739.5 1454.56  5759.6 1469.96
  5789.6 1484.63  5859.7 1497.61  5879.7  1506.8  5911.9 1510.55  5943.1 1512.65
#Mann= 10 ,-1 , 0
  3606.3     .05       0  3700.8      .1       0  3801.6     .16       0
    3947     .05       0  4343.8      .1       0  4352.7     .05       0
  4961.9     .07       0  5074.5      .1       0    5576     .16       0
  5911.9      .1       0
Bank Sta=4967.5,5074.5
XS Rating Curve= 0 ,0
Exp/Cntr=0.3,0.1

Type RM Length L Ch R = 1 ,5257    ,806,806,806
BEGIN DESCRIPTION:
UNT 1023 IN LATR 12.0
END DESCRIPTION:
XS GIS Cut Line= 4
      2898835.22     10045361.31      2899182.43     10044104.38
      2898779.66     10043604.38       2898897.7     10043194.71
#Sta/Elev= 30
    3352 1414.76  3871.2 1401.68  3908.6 1400.58  3994.5 1398.07  4148.3 1393.81
  4205.9 1388.56  4306.7 1377.15  4407.6 1373.31  4646.3 1364.18  4853.8 1367.79
  4893.9 1368.44  4929.1 1359.58  4937.1 1357.61  4972.3 1348.82  5000.8 1346.84
  5065.1 1356.26  5071.5 1357.28  5246.1 1378.81  5248.6  1378.5  5292.2  1378.9
  5319.7 1383.89  5340.4 1389.94  5380.4 1412.28  5413.2 1420.41    5453 1436.94
    5497  1468.4  5530.7 1481.86  5590.1 1488.84    5665 1509.21  5724.4  1513.7
#Mann= 14 ,-1 , 0
    3352     .05       0  3871.2      .1       0  3908.6     .05       0
  3994.5      .1       0  4205.9     .16       0  4306.7      .1       0
  4407.6     .05       0  4853.8      .1       0  4929.1     .07       0
  5071.5      .1       0  5246.1     .05       0  5248.6      .1       0
  5319.7     .16       0    5665     .05       0
Bank Sta=4937.1,5065.1
XS Rating Curve= 0 ,0
Exp/Cntr=0.3,0.1

Type RM Length L Ch R = 1 ,4451    ,863,863,863
BEGIN DESCRIPTION:
UNT 1023 IN LATR 9.0
END DESCRIPTION:
XS GIS Cut Line= 4
       2899064.4     10045187.68      2899696.32     10043916.88
      2899703.27     10043104.38      2899544.35     10042807.28
#Sta/Elev= 30
  3218.3 1400.29  3393.7  1396.5  3664.6 1391.03  3894.2 1377.77  4067.8 1371.93
  4082.7 1368.71  4127.3 1373.84  4187.2    1373  4191.6 1373.05  4283.7 1372.94
  4378.6 1362.44  4479.2 1358.88  4562.8 1358.72    4690 1359.74  4780.7 1359.48
  4870.7 1350.37  4930.7 1349.56  4940.7 1348.08  4970.7 1345.98  5000.5 1338.71
  5020.7 1345.87  5040.7 1359.22  5169.3 1371.11  5240.7 1379.03  5267.7 1385.78
  5453.3 1438.37  5513.2 1474.21    5543 1480.54  5644.9 1506.27    5787 1515.56
#Mann= 13 ,-1 , 0
  3218.3     .05       0  3393.7      .1       0  4187.2     .05       0
  4191.6      .1       0  4378.6     .05       0  4479.2      .1       0
  4562.8     .05       0    4690      .1       0  4930.7     .07       0
  5020.7     .16       0  5169.3     .05       0  5267.7     .16       0
    5543      .1       0
Bank Sta=4940.7,5020.7
XS Rating Curve= 0 ,0
Exp/Cntr=0.3,0.1

Type RM Length L Ch R = 1 ,3588    ,814,814,814
BEGIN DESCRIPTION:
UNT 1023 IN LATR 8.0
END DESCRIPTION:
XS GIS Cut Line= 4
      2900439.38     10045347.39      2900481.05     10044014.11
      2900606.05     10043347.44      2900092.79     10042501.26
#Sta/Elev= 30
  3287.4 1432.05  3351.1 1422.89  3417.7 1419.29  3801.3 1399.53  4151.5 1388.04
  4331.6 1373.67  4571.7 1359.31  4630.6  1347.4  4662.4 1343.98  4756.9 1341.78
  4784.5 1341.03  4825.5 1344.73  4856.2 1345.81  4924.8 1341.17  4947.3 1340.12
  4977.8 1338.06  4997.9 1333.08  5038.9 1340.67  5071.5  1350.4  5099.9 1352.51
    5503 1361.31  5680.5 1373.49  5751.2 1379.33  5782.1 1385.45  5840.3 1389.67
  5939.8 1403.07  6020.6  1411.9  6062.6 1423.38  6181.1  1465.7  6289.3 1468.91
#Mann= 10 ,-1 , 0
  3287.4     .05       0  3417.7      .1       0  4756.9     .05       0
  4825.5      .1       0  4924.8     .05       0  4947.3    .035       0
  5038.9     .05       0  5680.5      .1       0  5939.8     .05       0
  6062.6      .1       0
Bank Sta=4947.3,5038.9
XS Rating Curve= 0 ,0
Exp/Cntr=0.3,0.1

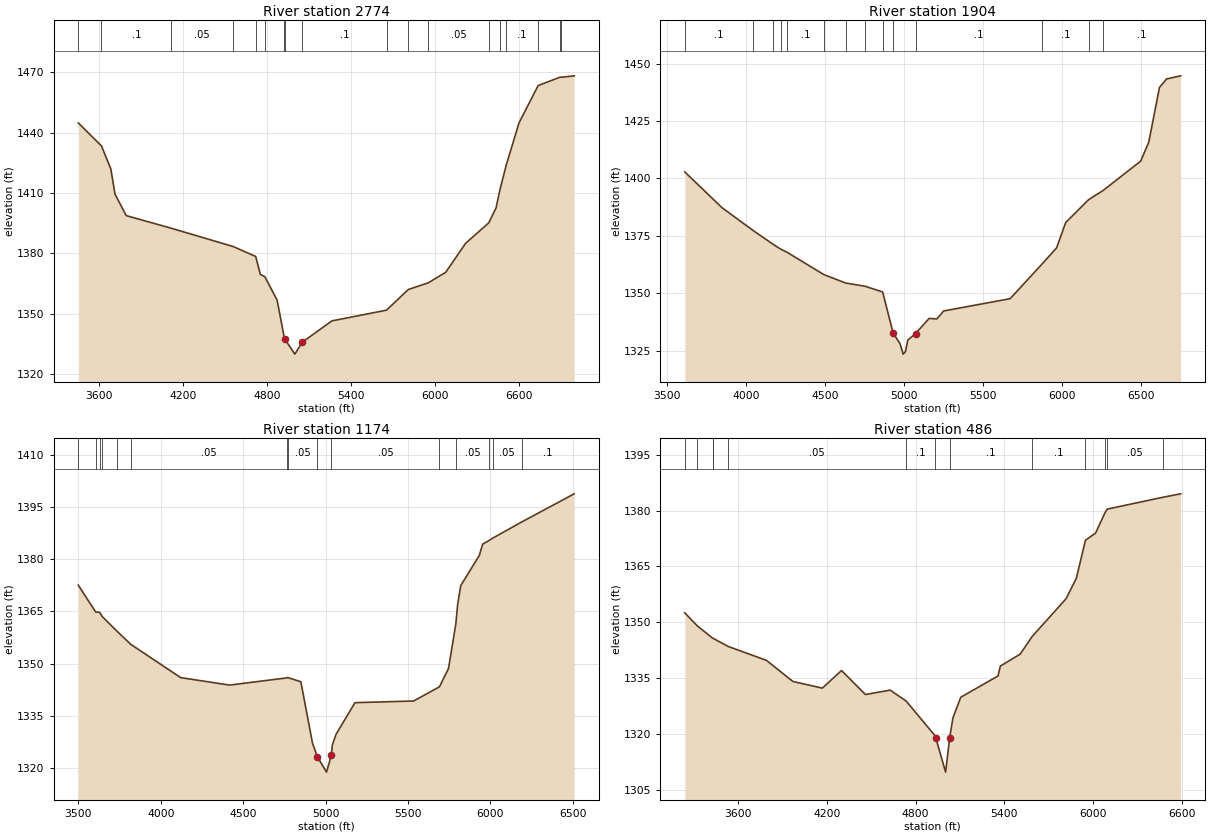
Type RM Length L Ch R = 1 ,2774    ,870,870,870
BEGIN DESCRIPTION:
UNT 1023 IN LATR 6.0
END DESCRIPTION:
XS GIS Cut Line= 4
      2901481.05     10045305.76      2901481.05      10044215.5
       2901099.1     10043083.55      2900072.36     10042362.06
#Sta/Elev= 30
  3454.6 1444.72  3619.9 1433.32  3686.6 1421.97  3716.6 1409.41  3796.6 1398.76
    4119 1392.49  4560.3 1383.42  4720.8  1378.5  4754.4 1369.54  4785.9 1368.51
  4873.9 1356.82  4924.7 1338.32  4926.7  1337.7  5000.3 1330.04  5053.3 1335.95
  5264.4 1346.52  5654.9 1351.86  5810.7 1362.12    5953 1365.42  6077.4 1370.64
  6220.3 1385.09  6384.5 1395.15  6436.9  1402.6    6464 1411.45  6510.2    1424
    6601 1444.81  6737.3 1463.28  6896.1 1467.52  6902.6 1467.41  6994.4 1468.12
#Mann= 18 ,-1 , 0
  3454.6     .05       0  3619.9      .1       0    4119     .05       0
  4560.3      .1       0  4720.8     .05       0  4785.9      .1       0
  4924.7     .05       0  4926.7    .035       0  5053.3      .1       0
  5654.9     .05       0  5810.7      .1       0    5953     .05       0
  6384.5      .1       0    6464     .05       0  6510.2      .1       0
  6737.3     .05       0  6896.1      .1       0  6902.6     .05       0
Bank Sta=4926.7,5053.3
XS Rating Curve= 0 ,0
Exp/Cntr=0.3,0.1

Type RM Length L Ch R = 1 ,1904    ,730,730,730
BEGIN DESCRIPTION:
UNT 1023 IN LATR 4.0
END DESCRIPTION:
XS GIS Cut Line= 4
      2902717.14     10044389.07      2902279.66     10043479.38
      2901529.66     10042833.55      2900502.68     10042340.88
#Sta/Elev= 30
  3610.3 1402.85  3846.6 1387.26  4044.9 1377.28  4166.7  1371.5  4216.9  1369.3
    4259 1367.85  4490.6 1358.19  4628.7 1354.53  4752.6 1353.11  4862.5 1350.64
  4929.3  1332.7  4972.1 1328.23  4992.7 1323.61  5007.2 1324.72  5021.5 1329.71
  5070.9 1332.56  5156.4 1339.13  5205.8 1338.93  5248.6 1342.38  5669.3 1347.72
  5873.4 1362.95  5963.8 1369.86  6021.2 1380.87  6166.1 1390.77  6258.5 1394.82
  6495.8 1407.56  6546.7 1415.76  6614.6 1439.59  6659.9 1443.29  6748.5 1444.65
#Mann= 14 ,-1 , 0
  3610.3      .1       0  4044.9     .05       0  4166.7      .1       0
  4216.9     .05       0    4259      .1       0  4490.6     .05       0
  4628.7      .1       0  4752.6     .05       0  4862.5      .1       0
  4929.3     .05       0  5070.9      .1       0  5873.4      .1       0
  6166.1     .05       0  6258.5      .1       0
Bank Sta=4929.3,5070.9
XS Rating Curve= 0 ,0
Exp/Cntr=0.3,0.1

Type RM Length L Ch R = 1 ,1174    ,688,688,688
BEGIN DESCRIPTION:
UNT 1023 IN LATR 2.0
END DESCRIPTION:
XS GIS Cut Line= 4
      2902897.71     10043840.48      2902592.16     10042854.38
      2901828.27     10042271.05      2900835.19     10042062.71
#Sta/Elev= 30
  3500.3 1372.52  3605.5 1364.82  3630.2  1364.7    3645 1363.55  3734.5 1359.33
    3819 1355.52  4121.3 1345.98  4418.2 1343.84  4764.7  1345.9  4769.4 1346.03
  4850.3  1344.8    4921 1327.19  4950.1 1323.32    5006 1318.85  5035.3 1323.67
  5041.6 1326.66  5064.3 1329.74  5178.6 1338.79  5534.5 1339.27    5691 1343.33
  5746.3 1348.61  5790.9 1361.51  5801.3 1366.87  5820.6 1372.42    5933 1381.04
  5953.4 1384.31  5990.8 1385.32  6013.1 1385.99  6189.6 1390.65  6508.5 1398.75
#Mann= 15 ,-1 , 0
  3500.3      .1       0  3605.5     .05       0  3630.2      .1       0
    3645     .05       0  3734.5      .1       0    3819     .05       0
  4764.7      .1       0  4769.4     .05       0  4950.1    .035       0
  5035.3     .05       0    5691      .1       0  5790.9     .05       0
  5990.8      .1       0  6013.1     .05       0  6189.6      .1       0
Bank Sta=4950.1,5035.3
XS Rating Curve= 0 ,0
Exp/Cntr=0.3,0.1

Type RM Length L Ch R = 1 ,486     ,0,0,0
BEGIN DESCRIPTION:
UNT 1023 IN LATR 1.0
END DESCRIPTION:
XS GIS Cut Line= 4
      2903321.33     10043521.07      2902897.71     10042173.83
      2902307.43      10041840.5      2901043.53     10041791.88
#Sta/Elev= 30
  3237.9 1352.53    3323    1349  3425.9 1345.75  3427.5 1345.72    3532 1343.49
  3790.7 1339.75  3969.2 1334.09  4168.8  1332.3  4298.4 1337.03  4460.3 1330.58
  4627.5 1331.76  4735.5 1328.84  4927.8 1319.67  4936.4 1318.89  5002.7 1309.73
  5030.3 1318.97    5052 1324.29  5105.4 1329.85  5357.1 1335.56    5373 1338.22
  5507.2 1341.44  5588.7 1346.19  5817.4  1356.3  5887.4 1361.82  5948.9 1372.03
  6017.5 1373.96  6078.8 1379.22  6095.6 1380.39  6475.8  1383.6  6592.9  1384.5
#Mann= 13 ,-1 , 0
  3237.9     .05       0    3323      .1       0  3425.9     .05       0
  3427.5      .1       0    3532     .05       0  4735.5      .1       0
  4927.8     .04       0  5030.3      .1       0  5588.7      .1       0
  5948.9     .05       0  6078.8     .16       0  6095.6     .05       0
  6475.8      .1       0
Bank Sta=4936.4,5030.3
XS Rating Curve= 0 ,0
Exp/Cntr=0.3,0.1

Chan Stop Cuts=-1
Use User Specified Reach Order=0
Composite Channel Slope=5