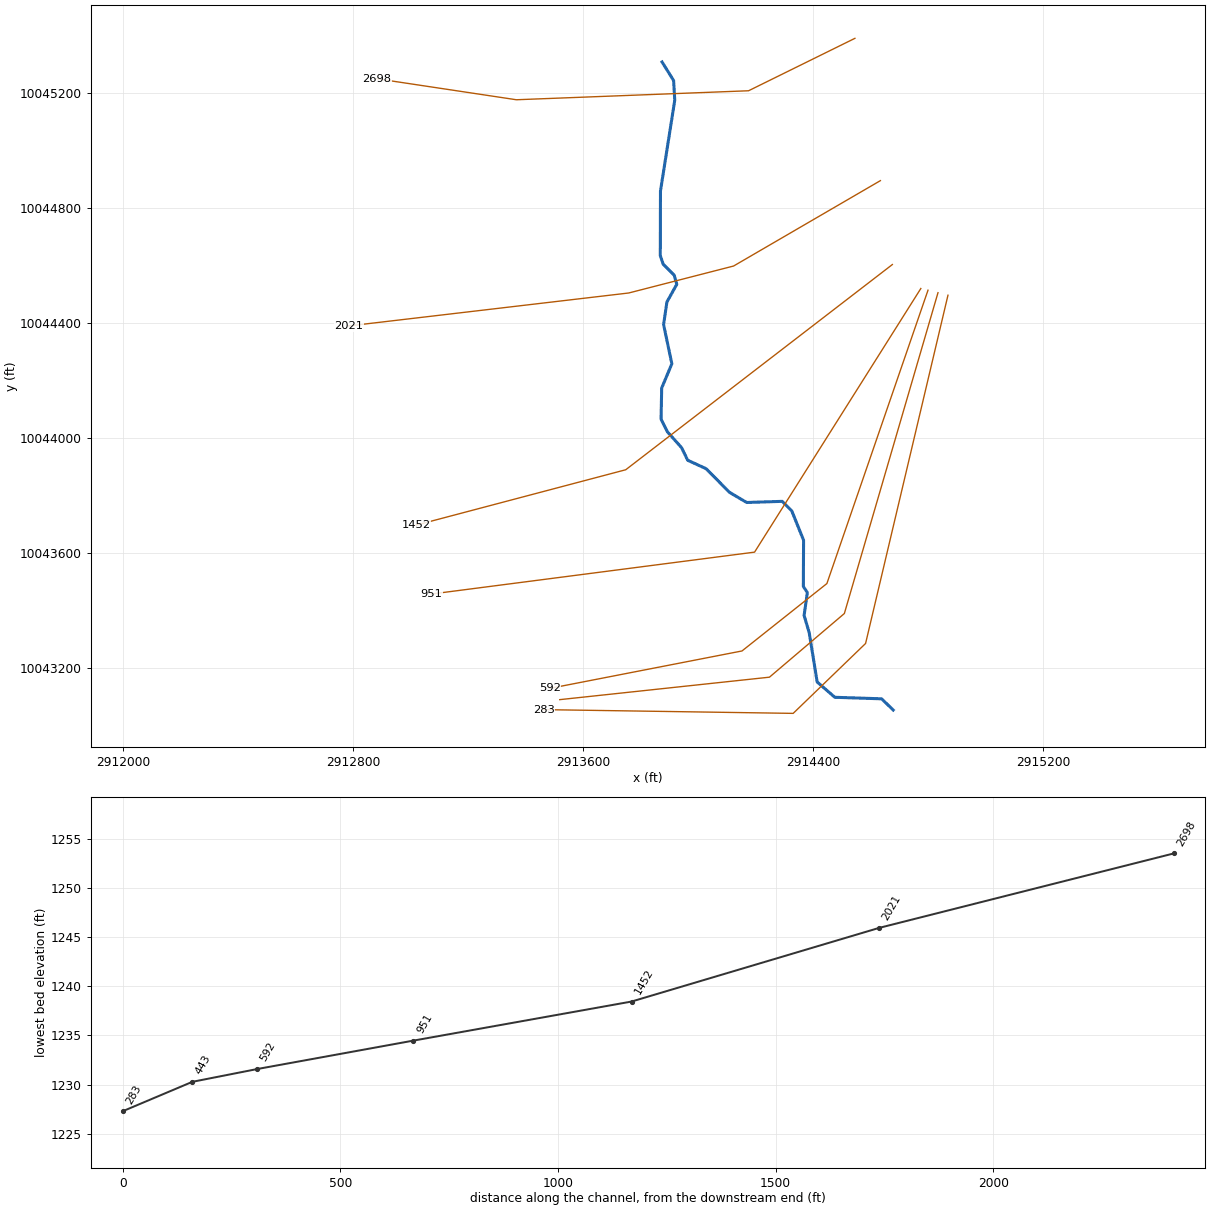
--- UNT 1027 IN LATR.prj (project) ---

Proj Title=UNT 1027 IN LATR Base Level Engineering
Current Plan=p01
Default Exp/Contr=0.3,0.1
English Units
Geom File=g01
Flow File=f01
Plan File=p01
BEGIN DESCRIPTION:
UNT 1027 IN LATR
END DESCRIPTION:

--- UNT 1027 IN LATR.p01 (plan) ---

Plan Title=Multiple Run
Short Identifier=Multiple
Geom File=g01
Flow File=f01
Subcritical Flow
K Sum by GR= 0
Std Step Tol= 0.01
Critical Tol= 0.01
Num of Std Step Trials= 20
Max Error Tol= 0.3
Flow Tol Ratio= 0.001
Split Flow NTrial= 30
Split Flow Tol= 0.02
Split Flow Ratio= 0.02
Log Output Level= 0
Friction Slope Method= 1
Unsteady Friction Slope Method= 2
Unsteady Bridges Friction Slope Method= 1
Parabolic Critical Depth
Global Vel Dist=  1 , 1 , 1
Global Log Level= 0
CheckData=True
Encroach Param= -1, 0, 0, 0
BEGIN DESCRIPTION:
Multiple Run
END DESCRIPTION:

--- UNT 1027 IN LATR.f01 (steady flow) ---

Flow Title=Multiple
Number of Profiles=7
Profile Names=10-year,25-year,50-year,1pct_min,100-year,1pct_plu,500-year
River Rch & RM= UNT 1027 IN LATR,Reach-1,2698
    1044    1534    1965    1845    2496    3375    4036
Boundary for River Rch & Prof#=UNT 1027 IN LATR,Reach-1,1
Up Type=0
Dn Type=3
Dn Slope=0.005
Boundary for River Rch & Prof#=UNT 1027 IN LATR,Reach-1,2
Up Type=0
Dn Type=3
Dn Slope=0.005
Boundary for River Rch & Prof#=UNT 1027 IN LATR,Reach-1,3
Up Type=0
Dn Type=3
Dn Slope=0.005
Boundary for River Rch & Prof#=UNT 1027 IN LATR,Reach-1,4
Up Type=0
Dn Type=3
Dn Slope=0.005
Boundary for River Rch & Prof#=UNT 1027 IN LATR,Reach-1,5
Up Type=0
Dn Type=3
Dn Slope=0.005
Boundary for River Rch & Prof#=UNT 1027 IN LATR,Reach-1,6
Up Type=0
Dn Type=3
Dn Slope=0.005
Boundary for River Rch & Prof#=UNT 1027 IN LATR,Reach-1,7
Up Type=0
Dn Type=3
Dn Slope=0.005

--- UNT 1027 IN LATR.g01 (geometry) ---

Geom Title=Existing Conditions

River Reach=UNT 1027 IN LATR,Reach-1
Reach XY= 30
      2913874.58     10045307.04      2913914.91     10045242.25
      2913918.83     10045173.76      2913869.23     10044858.41
      2913868.57     10044633.69      2913878.58     10044603.92
      2913916.96     10044565.41      2913925.94     10044533.87
      2913891.66     10044472.51      2913880.00     10044393.85
      2913908.76     10044257.74      2913873.42     10044173.10
      2913871.26     10044064.94      2913893.45     10044020.80
      2913942.46     10043966.08      2913963.94     10043922.09
      2914027.98     10043892.75      2914109.13     10043810.68
      2914168.94     10043775.30      2914292.51     10043779.25
      2914325.56     10043746.32      2914366.75     10043644.04
      2914365.94     10043483.25      2914379.96     10043462.14
      2914368.56     10043382.58      2914386.31     10043322.72
      2914414.03     10043151.16      2914475.43     10043098.00
      2914637.99     10043092.70      2914678.47     10043053.73

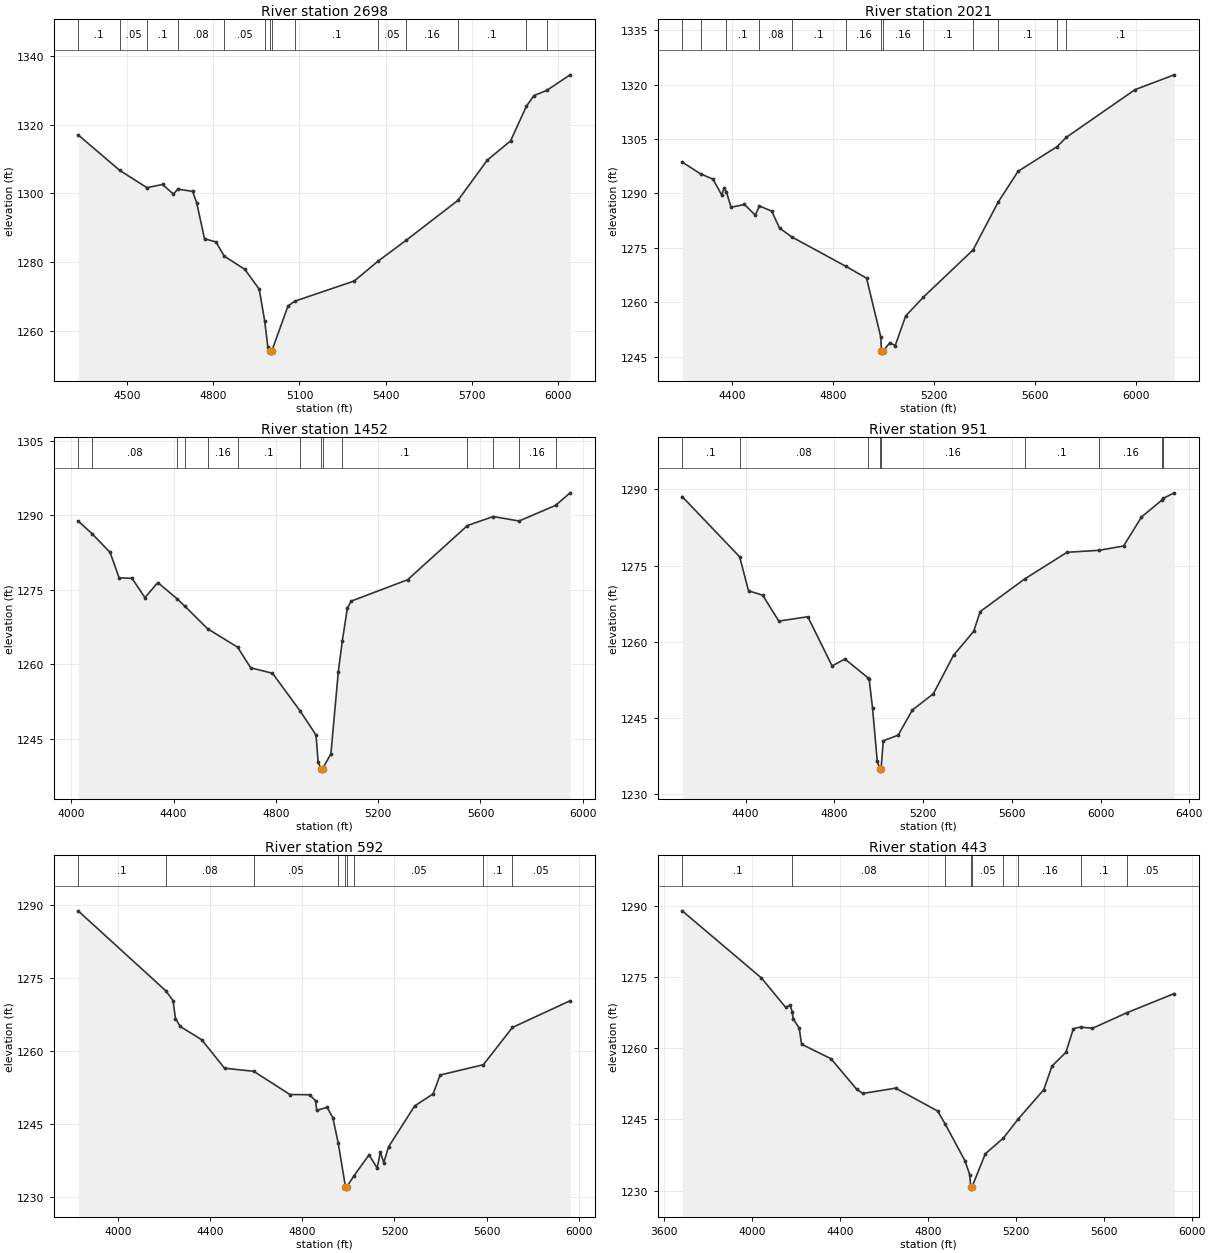
Type RM Length L Ch R = 1,2698,677,677,677
BEGIN DESCRIPTION:
UNT 1027 IN LATR 5.0
END DESCRIPTION:
XS GIS Cut Line= 4
      2914545.24     10045389.09      2914175.49     10045206.81
      2913368.20     10045175.56      2912883.79     10045248.49
#Sta/Elev= 30
  4330.7 1317.04  4475.5 1306.69  4570.0 1301.67  4624.0 1302.61  4661.6 1299.82
  4677.7 1301.25  4728.5 1300.60  4742.9 1297.23  4770.0 1286.79  4810.0 1285.87
  4838.2 1281.76  4910.1 1277.90  4960.1 1272.11  4979.0 1262.91  4990.1 1255.33
  4997.2 1254.01  4999.9 1253.51  5003.2 1254.01  5060.2 1267.24  5084.3 1268.65
  5290.4 1274.51  5373.3 1280.30  5471.9 1286.42  5650.7 1297.97  5752.8 1309.68
  5833.7 1315.29  5888.6 1325.35  5914.6 1328.47  5959.5 1329.99  6040.7 1334.52
#Mann=14,-1,0
  4330.7     0.1       0  4475.5    0.05       0  4570.0     0.1       0
  4677.7    0.08       0  4838.2    0.05       0  4979.0    0.16       0
  4997.2    0.07       0  5003.2    0.16       0  5084.3     0.1       0
  5373.3    0.05       0  5471.9    0.16       0  5650.7     0.1       0
  5888.6    0.16       0  5959.5     0.1       0
Bank Sta=4997.2,5003.2
Exp/Cntr=0.3,0.1

Type RM Length L Ch R = 1,2021,569,569,569
BEGIN DESCRIPTION:
UNT 1027 IN LATR 4.0
END DESCRIPTION:
XS GIS Cut Line= 4
      2914633.85     10044894.33      2914123.41     10044597.44
      2913758.82     10044503.69      2912784.89     10044389.11
#Sta/Elev= 30
  4202.1 1298.64  4275.6 1295.35  4324.0 1293.93  4358.7 1289.54  4368.4 1291.59
  4376.9 1290.45  4395.7 1286.17  4448.7 1286.94  4491.7 1283.98  4507.7 1286.52
  4556.3 1285.12  4587.7 1280.41  4637.0 1277.95  4851.2 1269.84  4931.9 1266.62
  4988.5 1250.33  4990.9 1246.44  4993.6 1245.94  4996.9 1246.44  5024.0 1248.80
  5045.5 1248.03  5086.8 1256.18  5155.7 1261.30  5353.6 1274.40  5452.5 1287.52
  5531.9 1296.09  5686.0 1302.87  5723.0 1305.47  5995.1 1318.61  6149.7 1322.69
#Mann=13,-1,0
  4202.1     0.1       0  4275.6    0.08       0  4376.9     0.1       0
  4507.7    0.08       0  4637.0     0.1       0  4851.2    0.16       0
  4990.9    0.07       0  4996.9    0.16       0  5155.7     0.1       0
  5353.6    0.05       0  5452.5     0.1       0  5686.0    0.16       0
  5723.0     0.1       0
Bank Sta=4990.9,4996.9
Exp/Cntr=0.3,0.1

Type RM Length L Ch R = 1,1452,501,501,501
BEGIN DESCRIPTION:
UNT 1027 IN LATR 3.0
END DESCRIPTION:
XS GIS Cut Line= 3
      2914675.47     10044602.63      2913748.41     10043889.11
      2913019.20     10043696.39
#Sta/Elev= 30
  4026.6 1288.89  4082.3 1286.26  4151.5 1282.55  4186.9 1277.42  4237.3 1277.33
  4287.8 1273.43  4338.2 1276.47  4415.1 1273.13  4444.3 1271.69  4533.0 1267.15
  4650.0 1263.45  4701.6 1259.28  4786.7 1258.18  4894.6 1250.60  4957.0 1245.72
  4965.2 1240.25  4976.7 1238.95  4979.5 1238.45  4982.7 1238.95  5015.1 1241.94
  5044.1 1258.49  5059.9 1264.75  5079.4 1271.25  5093.9 1272.71  5315.3 1277.04
  5549.2 1287.97  5650.1 1289.78  5751.0 1288.88  5893.7 1292.03  5950.7 1294.56
#Mann=14,-1,0
  4026.6     0.1       0  4082.3    0.08       0  4415.1     0.1       0
  4444.3    0.08       0  4533.0    0.16       0  4650.0     0.1       0
  4894.6    0.16       0  4976.7    0.07       0  4982.7    0.16       0
  5059.9     0.1       0  5549.2    0.16       0  5650.1     0.1       0
  5751.0    0.16       0  5893.7     0.1       0
Bank Sta=4976.7,4982.7
Exp/Cntr=0.3,0.1

Type RM Length L Ch R = 1,951,359,359,359
BEGIN DESCRIPTION:
UNT 1027 IN LATR 2.0
END DESCRIPTION:
XS GIS Cut Line= 3
      2914774.42     10044519.28      2914196.32     10043602.65
      2913072.43     10043456.96
#Sta/Elev= 30
  4114.1 1288.59  4373.1 1276.72  4413.1 1270.02  4476.7 1269.16  4549.6 1264.05
  4680.3 1264.91  4789.7 1255.21  4847.4 1256.58  4951.1 1252.89  4956.8 1252.55
  4971.9 1246.93  4993.3 1236.40  5004.4 1234.98  5007.1 1234.48  5010.4 1234.98
  5020.4 1240.46  5087.4 1241.57  5151.0 1246.51  5246.1 1249.73  5336.8 1257.31
  5427.6 1262.02  5457.2 1265.93  5658.3 1272.38  5848.3 1277.61  5992.4 1278.00
  6103.2 1278.85  6183.8 1284.56  6277.4 1287.96  6282.8 1288.26  6331.1 1289.33
#Mann=9,-1,0
  4114.1     0.1       0  4373.1    0.08       0  4951.1    0.16       0
  5004.4    0.07       0  5010.4    0.16       0  5658.3     0.1       0
  5992.4    0.16       0  6277.4    0.05       0  6282.8     0.1       0
Bank Sta=5004.4,5010.4
Exp/Cntr=0.3,0.1

Type RM Length L Ch R = 1,592,149,149,149
BEGIN DESCRIPTION:
Mapping XS 36cee9c7
END DESCRIPTION:
XS GIS Cut Line= 4
      2914799.36     10044513.41      2914447.80     10043493.46
      2914152.66     10043259.09      2913484.24     10043128.88
#Sta/Elev= 30
  3826.1 1288.78  4208.1 1272.29  4238.1 1270.34  4248.9 1266.64  4269.3 1265.02
  4362.9 1262.29  4461.8 1256.44  4588.8 1255.80  4746.0 1251.03  4831.0 1250.99
  4857.0 1249.77  4862.3 1247.78  4907.7 1248.39  4932.3 1246.26  4955.3 1241.14
  4987.0 1232.09  4989.8 1231.59  4993.0 1232.09  5024.8 1234.39  5089.3 1238.61
  5124.6 1235.93  5139.0 1239.20  5153.4 1237.03  5174.2 1240.27  5287.4 1248.68
  5367.6 1251.16  5398.2 1255.04  5586.0 1257.16  5712.5 1264.82  5962.8 1270.30
#Mann=9,-1,0
  3826.1     0.1       0  4208.1    0.08       0  4588.8    0.05       0
  4955.3    0.16       0  4987.0    0.07       0  4993.0    0.16       0
  5024.8    0.05       0  5586.0     0.1       0  5712.5    0.05       0
Bank Sta=4987,4993
Exp/Cntr=0.3,0.1

Type RM Length L Ch R = 1,443,160,160,160
BEGIN DESCRIPTION:
Mapping XS 89e108d9
END DESCRIPTION:
XS GIS Cut Line= 4
      2914834.08     10044504.72      2914508.56     10043389.30
      2914248.15     10043167.94      2913518.95     10043089.81
#Sta/Elev= 30
  3683.4 1288.88  4043.2 1274.77  4154.0 1268.56  4174.0 1269.02  4184.6 1267.51
  4187.5 1266.18  4215.7 1264.18  4226.2 1260.80  4360.1 1257.74  4476.1 1251.36
  4504.4 1250.43  4653.9 1251.55  4845.3 1246.73  4880.2 1243.93  4969.9 1236.20
  4990.8 1233.35  4995.5 1230.79  4998.3 1230.29  5001.5 1230.79  5062.2 1237.76
  5143.6 1241.02  5211.7 1245.07  5327.6 1251.22  5365.1 1256.20  5428.2 1259.09
  5462.3 1264.08  5494.7 1264.41  5548.9 1264.15  5705.6 1267.43  5920.5 1271.45
#Mann=9,-1,0
  3683.4     0.1       0  4184.6    0.08       0  4880.2    0.05       0
  4995.5    0.04       0  5001.5    0.05       0  5143.6     0.1       0
  5211.7    0.16       0  5494.7     0.1       0  5705.6    0.05       0
Bank Sta=4995.5,5001.5
Exp/Cntr=0.3,0.1

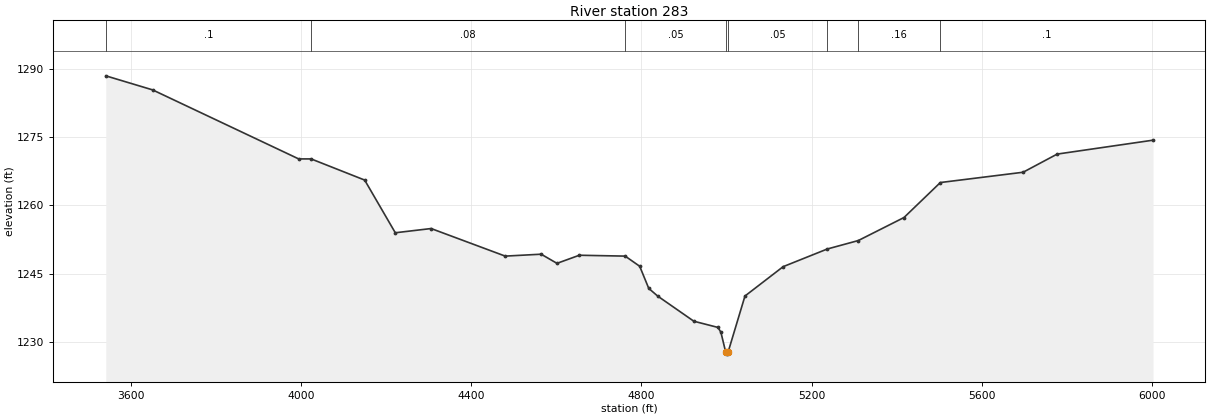
Type RM Length L Ch R = 1,283,0,0,0
BEGIN DESCRIPTION:
UNT 1027 IN LATR 1.0
END DESCRIPTION:
XS GIS Cut Line= 4
      2914868.80     10044496.02      2914582.35     10043285.13
      2914330.61     10043042.07      2913463.05     10043055.09
#Sta/Elev= 30
  3541.0 1288.46  3651.1 1285.37  3994.5 1270.20  4023.7 1270.20  4149.6 1265.55
  4221.6 1253.97  4305.8 1254.90  4480.0 1248.84  4564.5 1249.26  4601.7 1247.25
  4654.2 1249.03  4762.0 1248.84  4796.1 1246.61  4817.4 1241.75  4838.5 1240.05
  4923.4 1234.53  4980.0 1233.17  4987.0 1232.12  4998.1 1227.80  5000.9 1227.30
  5004.1 1227.80  5043.6 1240.07  5133.3 1246.52  5237.0 1250.40  5310.0 1252.26
  5417.4 1257.32  5502.9 1265.01  5697.4 1267.27  5777.5 1271.26  6002.9 1274.32
#Mann=8,-1,0
  3541.0     0.1       0  4023.7    0.08       0  4762.0    0.05       0
  4998.1    0.04       0  5004.1    0.05       0  5237.0     0.1       0
  5310.0    0.16       0  5502.9     0.1       0
Bank Sta=4998.1,5004.1
Exp/Cntr=0.3,0.1

Chan Stop Cuts=-1