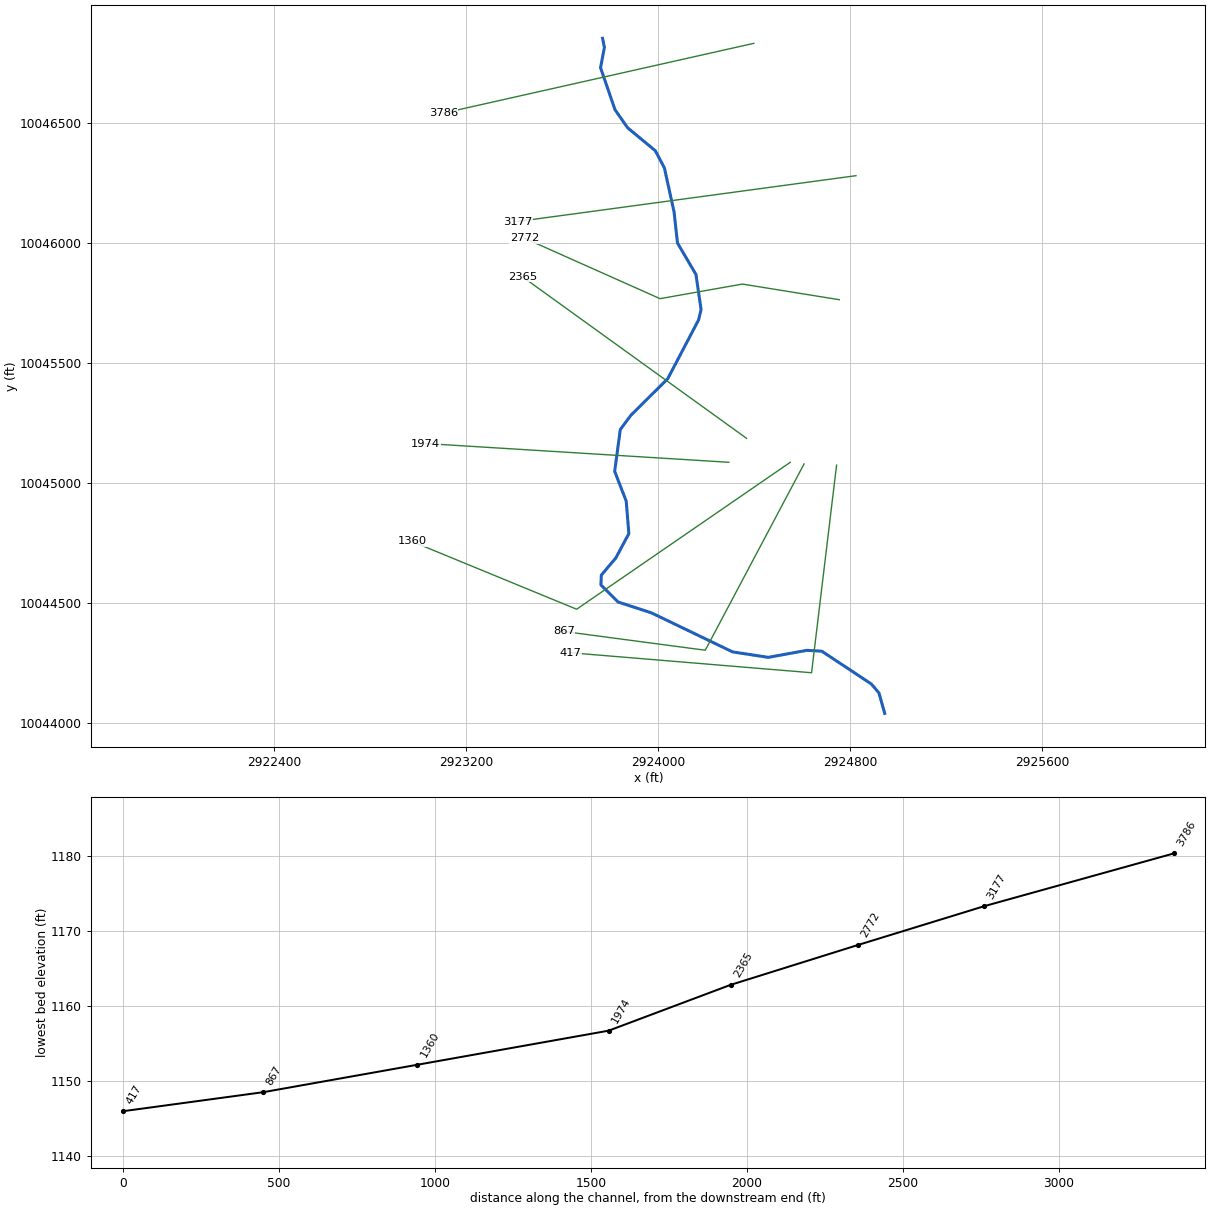
--- UNT 1030 IN LATR.prj (project) ---

Proj Title=UNT 1030 IN LATR Base Level Engineering
Current Plan=p01
Default Exp/Contr=0.3,0.1
English Units
Geom File=g01
Flow File=f01
Plan File=p01
BEGIN DESCRIPTION:
UNT 1030 IN LATR
END DESCRIPTION:

--- UNT 1030 IN LATR.p01 (plan) ---

Plan Title=Multiple Run
Short Identifier=Multiple
Geom File=g01
Flow File=f01
Subcritical Flow
K Sum by GR= 0
Std Step Tol= 0.01
Critical Tol= 0.01
Num of Std Step Trials= 20
Max Error Tol= 0.3
Flow Tol Ratio= 0.001
Split Flow NTrial= 30
Split Flow Tol= 0.02
Split Flow Ratio= 0.02
Log Output Level= 0
Friction Slope Method= 1
Unsteady Friction Slope Method= 2
Unsteady Bridges Friction Slope Method= 1
Parabolic Critical Depth
Global Vel Dist=  1 , 1 , 1
Global Log Level= 0
CheckData=True
Encroach Param= -1, 0, 0, 0
BEGIN DESCRIPTION:
Multiple Run
END DESCRIPTION:

--- UNT 1030 IN LATR.f01 (steady flow) ---

Flow Title=Multiple
Number of Profiles=7
Profile Names=10-year,25-year,50-year,1pct_min,100-year,1pct_plu,500-year
River Rch & RM= UNT 1030 IN LATR,Reach-1,3786
    1186    1739    2225    2083    2817    3809    4531
Boundary for River Rch & Prof#=UNT 1030 IN LATR,Reach-1,1
Up Type=0
Dn Type=3
Dn Slope=0.005
Boundary for River Rch & Prof#=UNT 1030 IN LATR,Reach-1,2
Up Type=0
Dn Type=3
Dn Slope=0.005
Boundary for River Rch & Prof#=UNT 1030 IN LATR,Reach-1,3
Up Type=0
Dn Type=3
Dn Slope=0.005
Boundary for River Rch & Prof#=UNT 1030 IN LATR,Reach-1,4
Up Type=0
Dn Type=3
Dn Slope=0.005
Boundary for River Rch & Prof#=UNT 1030 IN LATR,Reach-1,5
Up Type=0
Dn Type=3
Dn Slope=0.005
Boundary for River Rch & Prof#=UNT 1030 IN LATR,Reach-1,6
Up Type=0
Dn Type=3
Dn Slope=0.005
Boundary for River Rch & Prof#=UNT 1030 IN LATR,Reach-1,7
Up Type=0
Dn Type=3
Dn Slope=0.005

--- UNT 1030 IN LATR.g01 (geometry) ---

Geom Title=Existing Conditions

River Reach=UNT 1030 IN LATR,Reach-1
Reach XY= 30
      2923768.47     10046851.60      2923776.11     10046813.81
      2923760.10     10046729.17      2923820.22     10046554.46
      2923872.78     10046479.05      2923988.03     10046383.68
      2924025.86     10046312.66      2924066.32     10046128.23
      2924080.38     10045999.45      2924157.36     10045868.21
      2924178.82     10045721.69      2924168.31     10045678.84
      2924039.87     10045433.97      2923885.96     10045281.29
      2923842.26     10045222.16      2923818.96     10045048.23
      2923866.98     10044924.22      2923877.97     10044788.97
      2923823.82     10044687.71      2923763.26     10044616.09
      2923761.63     10044575.29      2923833.42     10044503.91
      2923971.33     10044459.26      2924309.59     10044296.45
      2924458.41     10044273.61      2924619.06     10044302.80
      2924681.28     10044299.33      2924887.65     10044162.89
      2924919.53     10044125.50      2924943.49     10044040.31

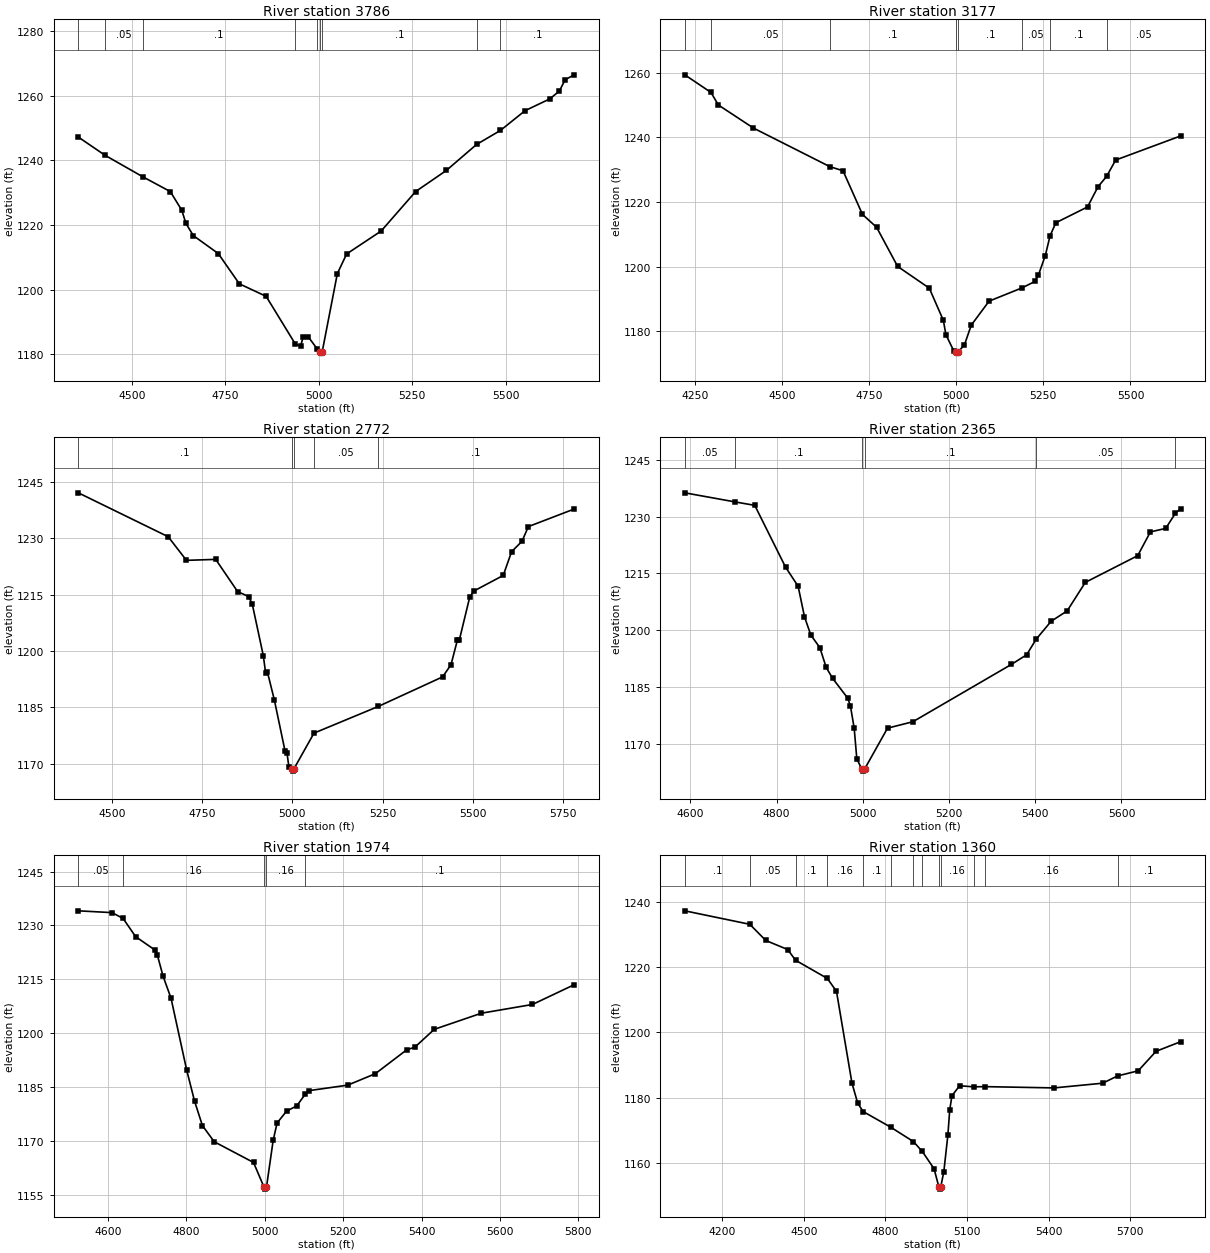
Type RM Length L Ch R = 1,3786,609,609,609
BEGIN DESCRIPTION:
UNT 1030 IN LATR 7.0
END DESCRIPTION:
XS GIS Cut Line= 2
      2924398.39     10046830.80      2923104.98     10046540.00
#Sta/Elev= 30
  4357.1 1247.24  4428.6 1241.59  4528.8 1234.98  4603.0 1230.35  4633.8 1224.55
  4644.6 1220.52  4664.5 1216.71  4731.2 1211.15  4787.5 1201.78  4859.3 1197.88
  4937.7 1183.03  4951.5 1182.51  4957.9 1185.16  4972.0 1185.33  4996.4 1181.49
  5003.3 1180.79  5006.1 1180.29  5009.3 1180.79  5049.6 1204.93  5074.5 1211.03
  5166.7 1218.12  5259.0 1230.36  5341.0 1236.89  5421.8 1244.95  5485.6 1249.29
  5551.5 1255.42  5617.7 1259.07  5643.2 1261.50  5658.7 1265.01  5682.8 1266.53
#Mann=9,-1,0
  4357.1     0.1       0  4428.6    0.05       0  4528.8     0.1       0
  4937.7    0.16       0  4996.4     0.1       0  5003.3    0.07       0
  5009.3     0.1       0  5421.8    0.16       0  5485.6     0.1       0
Bank Sta=5003.3,5009.3
Exp/Cntr=0.3,0.1

Type RM Length L Ch R = 1,3177,405,405,405
BEGIN DESCRIPTION:
UNT 1030 IN LATR 6.0
END DESCRIPTION:
XS GIS Cut Line= 2
      2924823.75     10046279.59      2923413.71     10046088.69
#Sta/Elev= 30
  4221.1 1259.29  4296.2 1253.85  4317.3 1249.97  4418.2 1242.82  4637.4 1230.90
  4675.1 1229.63  4731.0 1216.12  4771.4 1212.17  4831.9 1200.05  4922.7 1193.33
  4963.1 1183.37  4970.5 1178.90  4993.4 1173.85  5000.5 1173.74  5003.2 1173.24
  5006.5 1173.74  5023.6 1175.78  5043.1 1181.88  5094.3 1189.31  5189.9 1193.46
  5225.5 1195.39  5235.6 1197.29  5255.7 1203.42  5269.3 1209.51  5286.0 1213.56
  5376.8 1218.44  5407.1 1224.72  5431.4 1227.86  5457.6 1232.94  5644.0 1240.39
#Mann=8,-1,0
  4221.1     0.1       0  4296.2    0.05       0  4637.4     0.1       0
  5000.5    0.07       0  5006.5     0.1       0  5189.9    0.05       0
  5269.3     0.1       0  5431.4    0.05       0
Bank Sta=5000.5,5006.5
Exp/Cntr=0.3,0.1

Type RM Length L Ch R = 1,2772,407,407,407
BEGIN DESCRIPTION:
UNT 1030 IN LATR 5.0
END DESCRIPTION:
XS GIS Cut Line= 4
      2924754.36     10045763.09      2924350.67     10045828.20
      2924007.79     10045767.44      2923444.08     10046018.94
#Sta/Elev= 30
  4406.8 1242.04  4655.9 1230.37  4706.5 1224.09  4787.6 1224.35  4848.4 1215.78
  4878.9 1214.47  4889.0 1212.43  4919.5 1198.77  4925.9 1194.22  4931.0 1194.38
  4950.0 1187.04  4980.0 1173.31  4985.1 1172.93  4990.6 1169.10  4997.8 1168.56
  5000.5 1168.06  5003.8 1168.56  5060.0 1178.16  5238.1 1185.25  5416.5 1193.11
  5439.8 1196.34  5457.5 1202.89  5463.0 1202.96  5491.7 1214.30  5502.6 1215.91
  5584.6 1220.08  5607.8 1226.40  5636.5 1229.14  5654.2 1233.06  5781.2 1237.73
#Mann=5,-1,0
  4406.8     0.1       0  4997.8    0.07       0  5003.8     0.1       0
  5060.0    0.05       0  5238.1     0.1       0
Bank Sta=4997.8,5003.8
Exp/Cntr=0.3,0.1

Type RM Length L Ch R = 1,2365,391,391,391
BEGIN DESCRIPTION:
UNT 1030 IN LATR 4.0
END DESCRIPTION:
XS GIS Cut Line= 2
      2924368.00     10045185.86      2923434.91     10045858.56
#Sta/Elev= 30
  4586.9 1236.28  4702.5 1233.90  4749.2 1232.97  4820.6 1216.66  4849.8 1211.60
  4864.6 1203.53  4879.3 1198.70  4900.1 1195.41  4914.9 1190.17  4929.6 1187.31
  4965.2 1181.99  4971.3 1179.88  4979.9 1174.08  4986.0 1165.98  4997.8 1163.26
  5000.5 1162.76  5003.8 1163.26  5057.2 1174.11  5116.1 1175.81  5344.3 1190.93
  5379.9 1193.49  5402.2 1197.63  5436.9 1202.36  5473.9 1205.08  5516.1 1212.62
  5637.6 1219.68  5667.1 1225.96  5702.6 1226.88  5725.1 1230.89  5737.2 1232.08
#Mann=6,-1,0
  4586.9    0.05       0  4702.5     0.1       0  4997.8    0.07       0
  5003.8     0.1       0  5402.2    0.05       0  5725.1     0.1       0
Bank Sta=4997.8,5003.8
Exp/Cntr=0.3,0.1

Type RM Length L Ch R = 1,1974,614,614,614
BEGIN DESCRIPTION:
UNT 1030 IN LATR 3.0
END DESCRIPTION:
XS GIS Cut Line= 2
      2924294.27     10045086.01      2923032.38     10045164.07
#Sta/Elev= 30
  4524.8 1234.07  4610.8 1233.57  4639.0 1231.94  4670.9 1226.89  4721.0 1223.10
  4726.0 1221.86  4741.0 1215.85  4761.1 1209.78  4801.1 1189.76  4821.2 1181.11
  4841.2 1174.33  4871.3 1169.83  4971.5 1164.07  4998.5 1157.15  5001.3 1156.65
  5004.5 1157.15  5021.6 1170.21  5031.6 1175.05  5055.7 1178.34  5081.7 1179.81
  5103.3 1183.03  5111.7 1184.03  5211.8 1185.58  5282.1 1188.76  5362.2 1195.41
  5383.0 1196.14  5432.3 1201.10  5552.6 1205.59  5682.8 1208.02  5789.1 1213.51
#Mann=5,-1,0
  4524.8    0.05       0  4639.0    0.16       0  4998.5    0.07       0
  5004.5    0.16       0  5103.3     0.1       0
Bank Sta=4998.5,5004.5
Exp/Cntr=0.3,0.1

Type RM Length L Ch R = 1,1360,493,493,493
BEGIN DESCRIPTION:
UNT 1030 IN LATR 2.0
END DESCRIPTION:
XS GIS Cut Line= 3
      2924550.34     10045086.02      2923660.56     10044474.03
      2922974.84     10044756.14
#Sta/Elev= 30
  4063.0 1237.20  4301.8 1233.08  4360.4 1228.14  4440.9 1225.36  4470.1 1222.08
  4586.5 1216.53  4620.2 1212.59  4677.0 1184.56  4698.0 1178.42  4717.9 1175.83
  4819.1 1171.06  4902.9 1166.63  4935.4 1163.62  4978.7 1158.33  4996.8 1152.60
  4999.6 1152.10  5002.8 1152.60  5014.6 1157.48  5029.5 1168.70  5036.2 1176.33
  5044.4 1180.68  5072.6 1183.71  5123.7 1183.38  5166.4 1183.44  5419.5 1183.05
  5598.0 1184.49  5652.6 1186.71  5728.6 1188.28  5794.0 1194.24  5884.4 1197.18
#Mann=13,-1,0
  4063.0     0.1       0  4301.8    0.05       0  4470.1     0.1       0
  4586.5    0.16       0  4717.9     0.1       0  4819.1    0.16       0
  4902.9     0.1       0  4935.4    0.16       0  4996.8    0.07       0
  5002.8    0.16       0  5123.7     0.1       0  5166.4    0.16       0
  5652.6     0.1       0
Bank Sta=4996.8,5002.8
Exp/Cntr=0.3,0.1

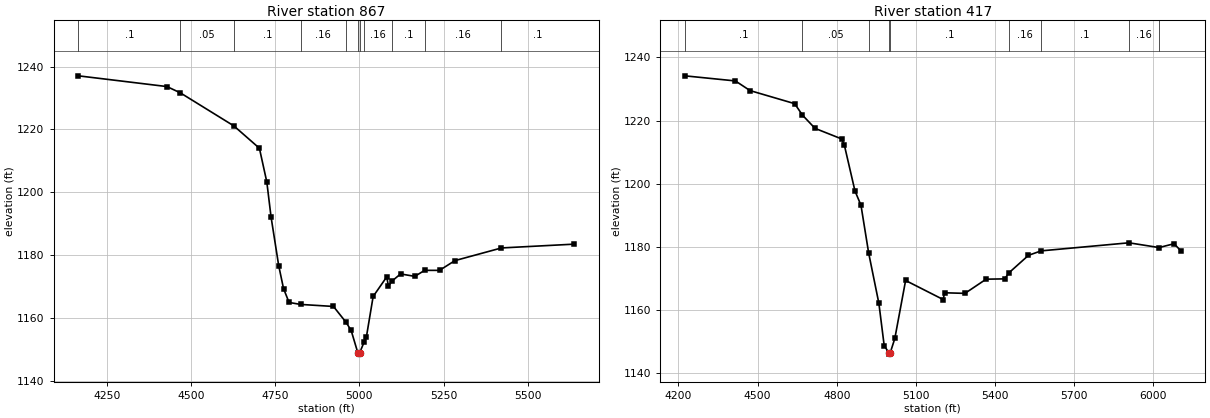
Type RM Length L Ch R = 1,867,450,450,450
BEGIN DESCRIPTION:
Mapping XS 59183ef6
END DESCRIPTION:
XS GIS Cut Line= 3
      2924607.63     10045079.29      2924196.18     10044303.27
      2923607.59     10044381.40
#Sta/Elev= 30
  4165.8 1237.07  4428.8 1233.65  4468.5 1231.66  4627.9 1221.10  4703.4 1214.01
  4725.4 1203.27  4738.0 1192.13  4760.7 1176.62  4775.0 1169.34  4791.4 1164.91
  4825.5 1164.28  4923.3 1163.63  4960.6 1158.59  4975.7 1156.02  4995.4 1148.95
  4998.1 1148.45  5001.4 1148.95  5014.0 1152.23  5021.0 1153.89  5041.1 1166.81
  5081.4 1173.04  5086.5 1170.11  5097.3 1171.73  5122.5 1173.99  5164.8 1173.21
  5194.0 1175.13  5238.1 1175.12  5283.9 1178.23  5422.0 1182.26  5637.9 1183.47
#Mann=11,-1,0
  4165.8     0.1       0  4468.5    0.05       0  4627.9     0.1       0
  4825.5    0.16       0  4960.6     0.1       0  4995.4    0.07       0
  5001.4     0.1       0  5014.0    0.16       0  5097.3     0.1       0
  5194.0    0.16       0  5422.0     0.1       0
Bank Sta=4995.4,5001.4
Exp/Cntr=0.3,0.1

Type RM Length L Ch R = 1,417,0,0,0
BEGIN DESCRIPTION:
UNT 1030 IN LATR 1.0
END DESCRIPTION:
XS GIS Cut Line= 3
      2924743.06     10045074.15      2924638.89     10044209.52
      2923633.71     10044292.85
#Sta/Elev= 30
  4223.9 1234.18  4415.7 1232.56  4471.2 1229.50  4640.4 1225.35  4670.0 1221.71
  4717.5 1217.52  4818.6 1214.16  4828.7 1212.21  4868.9 1197.68  4891.7 1193.13
  4921.0 1177.92  4959.6 1162.02  4979.7 1148.62  4996.9 1146.41  4999.6 1145.91
  5002.9 1146.41  5020.0 1150.87  5060.9 1169.27  5203.4 1163.22  5208.4 1165.37
  5285.9 1165.18  5366.1 1169.68  5436.4 1169.78  5453.0 1171.73  5526.7 1177.25
  5574.6 1178.66  5907.4 1181.22  6021.8 1179.71  6078.6 1180.93  6103.4 1178.75
#Mann=9,-1,0
  4223.9     0.1       0  4670.0    0.05       0  4921.0     0.1       0
  4996.9    0.07       0  5002.9     0.1       0  5453.0    0.16       0
  5574.6     0.1       0  5907.4    0.16       0  6021.8     0.1       0
Bank Sta=4996.9,5002.9
Exp/Cntr=0.3,0.1

Chan Stop Cuts=-1