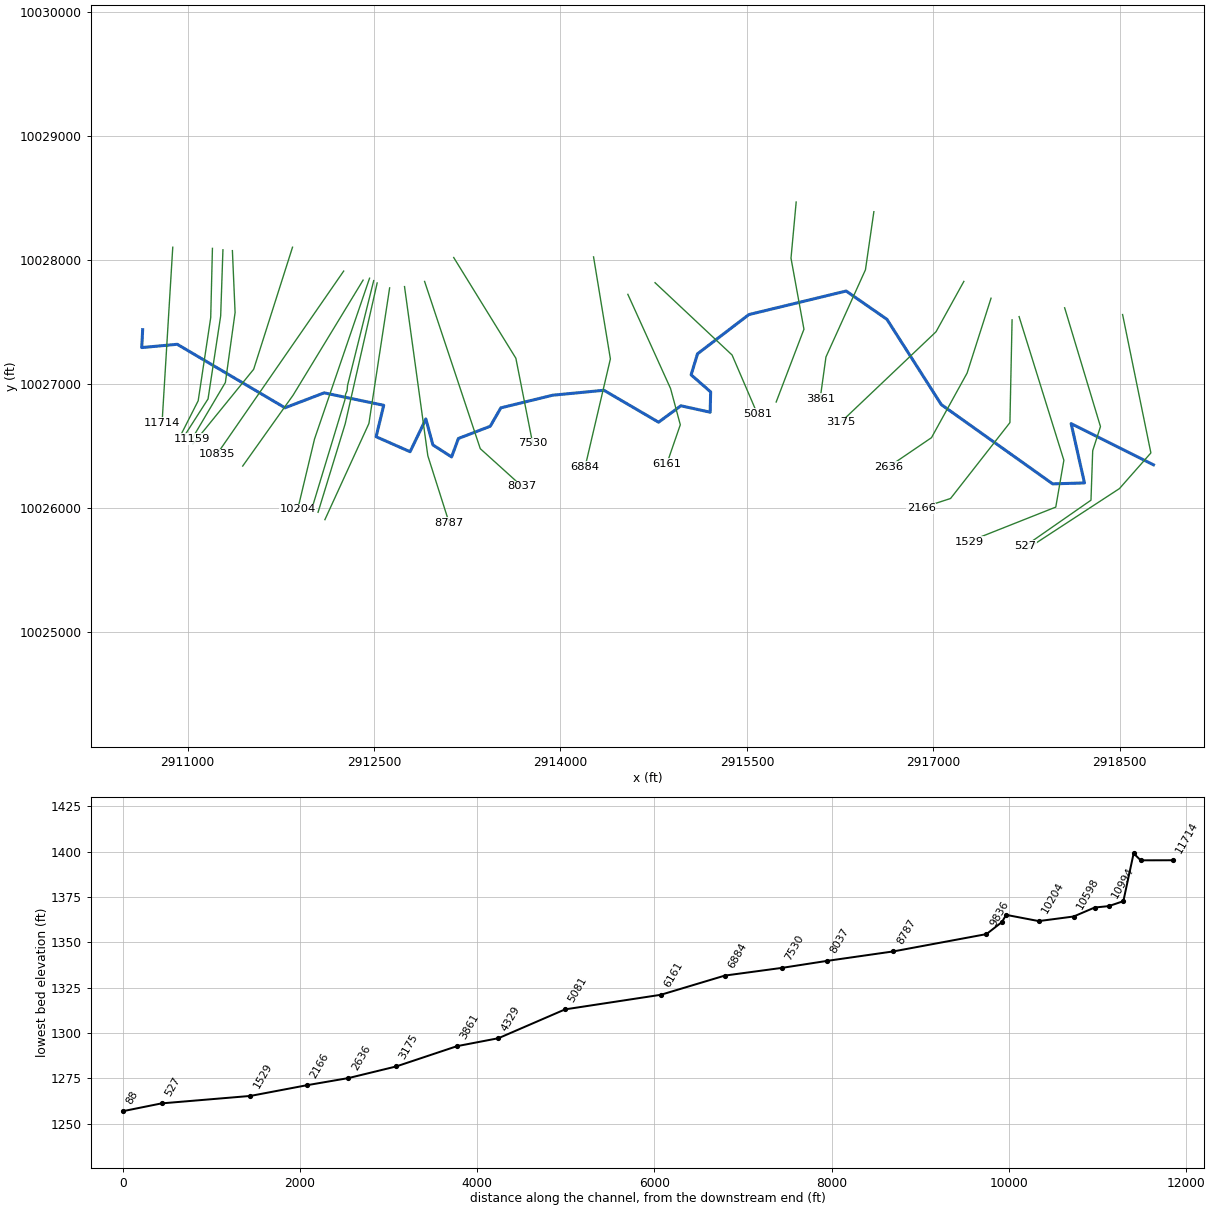
--- UNT 1032 IN LATR.prj (project) ---

Proj Title=UNT 1032 IN LATR Base Level Engineering
Current Plan=p01
Default Exp/Contr=0.3,0.1
English Units
Geom File=g01
Flow File=f01
Plan File=p01
Y Axis Title=Elevation
X Axis Title(PF)=Main Channel Distance
X Axis Title(XS)=Station
BEGIN DESCRIPTION:
UNT 1032 IN LATR
END DESCRIPTION:
DSS Export Rating Curves= 0
DSS Export Rating Curve Sorted= 0
DSS Export Volume Flow Curves= 0
DXF OffsetX= 0
DXF OffsetY= 0
DXF ScaleX= 1
DXF ScaleY= 10

--- UNT 1032 IN LATR.p01 (plan) ---

Plan Title=Multiple Run
Short Identifier=Multiple
Geom File=g01
Flow File=f01
Subcritical Flow
K Sum by GR= 0
Std Step Tol= 0.01
Critical Tol= 0.01
Num of Std Step Trials= 20
Max Error Tol= 0.3
Flow Tol Ratio= 0.001
Split Flow NTrial= 30
Split Flow Tol= 0.02
Split Flow Ratio= 0.02
Log Output Level= 0
Friction Slope Method= 1
Unsteady Friction Slope Method= 2
Unsteady Bridges Friction Slope Method= 1
Parabolic Critical Depth
Global Vel Dist=  1 , 1 , 1
Global Log Level= 0
CheckData=True
Encroach Param= -1, 0, 0, 0
BEGIN DESCRIPTION:
Multiple Run
END DESCRIPTION:

--- UNT 1032 IN LATR.f01 (steady flow) ---

Flow Title=Multiple
Program Version=4.10
Number of Profiles= 7
Profile Names=10-year,25-year,50-year,1pct_min,100-year,1pct_plu,500-year
River Rch & RM=UNT 1032 IN LATR,Reach-1         ,11714
     997    1457    1861    1741    2355    3185    3783
River Rch & RM=UNT 1032 IN LATR,Reach-1         ,10598
    1509    2255    2924    2773    3750    5071    6190
River Rch & RM=UNT 1032 IN LATR,Reach-1         ,6884
    1684    2519    3267    3096    4188    5663    6907
Boundary for River Rch & Prof#=UNT 1032 IN LATR,Reach-1         , 1
Up Type= 0
Dn Type= 3
Dn Slope=0.0099
Boundary for River Rch & Prof#=UNT 1032 IN LATR,Reach-1         , 2
Up Type= 0
Dn Type= 3
Dn Slope=0.0099
Boundary for River Rch & Prof#=UNT 1032 IN LATR,Reach-1         , 3
Up Type= 0
Dn Type= 3
Dn Slope=0.0099
Boundary for River Rch & Prof#=UNT 1032 IN LATR,Reach-1         , 4
Up Type= 0
Dn Type= 3
Dn Slope=0.0099
Boundary for River Rch & Prof#=UNT 1032 IN LATR,Reach-1         , 5
Up Type= 0
Dn Type= 3
Dn Slope=0.0099
Boundary for River Rch & Prof#=UNT 1032 IN LATR,Reach-1         , 6
Up Type= 0
Dn Type= 3
Dn Slope=0.0099
Boundary for River Rch & Prof#=UNT 1032 IN LATR,Reach-1         , 7
Up Type= 0
Dn Type= 3
Dn Slope=0.0099
DSS Import GetInterval= 0
DSS Import GetPeak= 0
DSS Import FillOption= 0

--- UNT 1032 IN LATR.g01 (geometry) ---

Geom Title=Existing Conditions
Program Version=4.10

River Reach=UNT 1032 IN LATR,Reach-1
Reach XY= 30
      2910638.42     10027440.93      2910631.19      10027296.5
      2910916.75       10027323.      2911783.66     10026810.67
      2912098.51     10026931.32      2912577.95     10026830.83
      2912516.76      10026577.3      2912790.17     10026456.28
      2912916.89     10026720.73      2912973.57     10026511.12
      2913123.96     10026414.34      2913178.87     10026563.26
      2913434.88     10026661.59      2913520.31     10026810.31
      2913937.25     10026912.21      2914349.65     10026952.03
      2914789.13     10026694.52      2914968.74     10026826.96
      2915204.26     10026775.05      2915208.29     10026938.74
      2915051.05     10027076.79      2915102.43     10027246.06
      2915515.97     10027562.74      2916298.37     10027752.69
      2916626.78     10027524.13      2917063.86      10026836.5
      2917959.85     10026197.09      2918215.72     10026204.62
       2918108.4     10026683.13      2918770.59     10026350.74

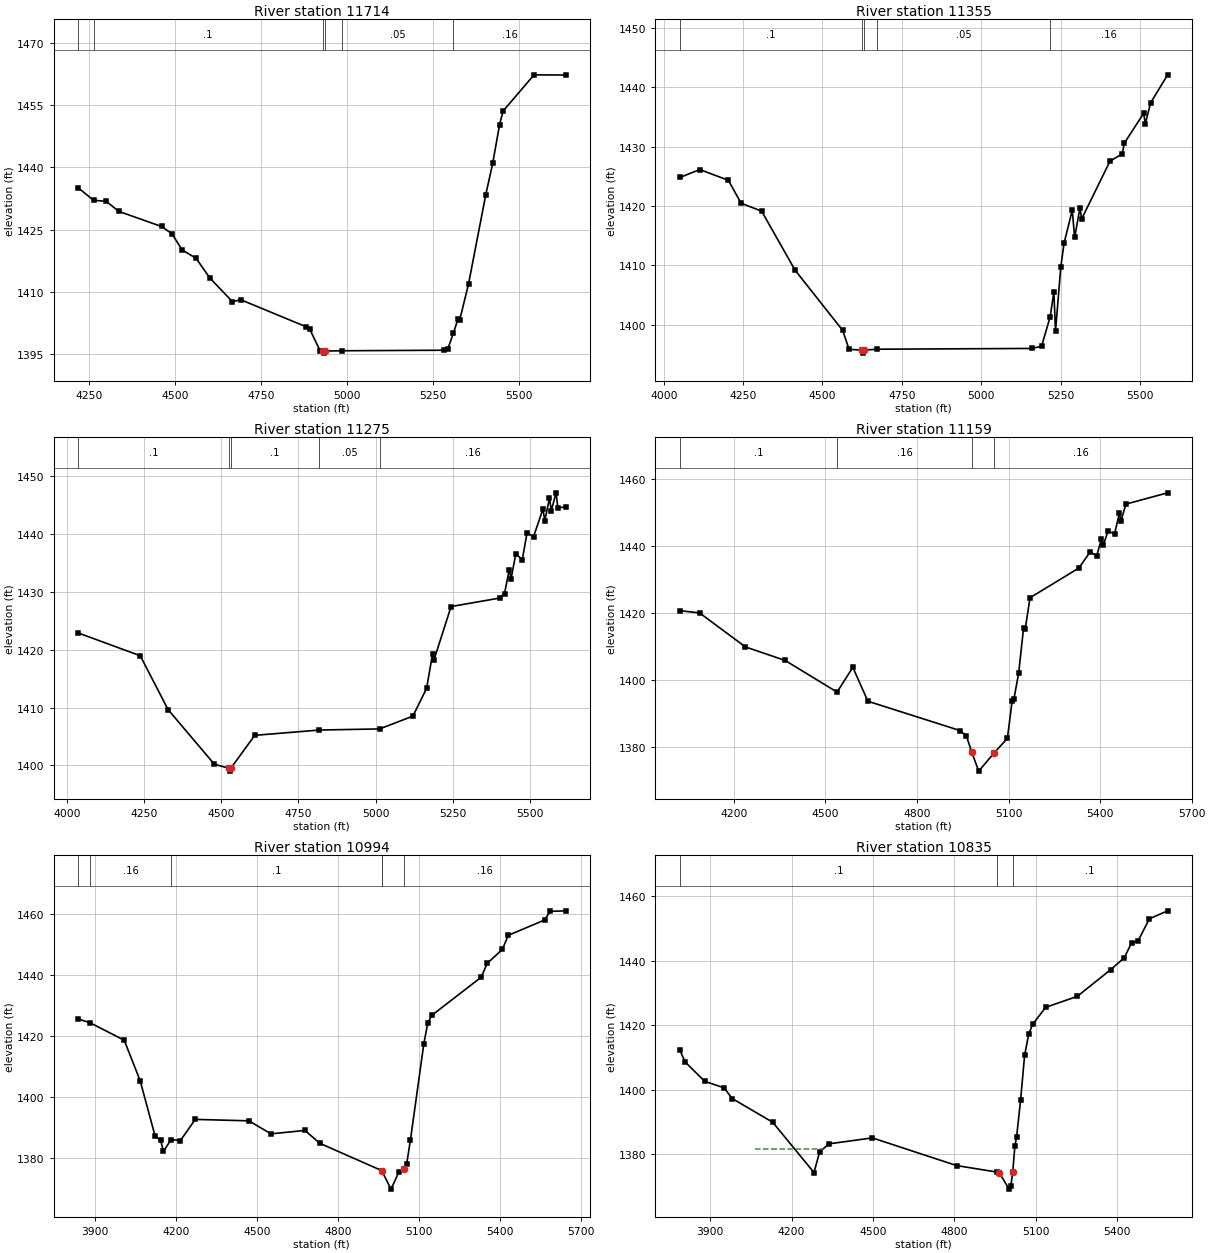
Type RM Length L Ch R = 1 ,11714   ,359,359,359
BEGIN DESCRIPTION:
UNT 1032 IN LATR 24.0
END DESCRIPTION:
XS GIS Cut Line= 2
       2910880.7     10028106.14      2910794.76     10026692.05
#Sta/Elev= 30
  4218.6 1435.11  4263.9 1432.06  4301.2 1431.79    4337 1429.39  4461.5 1425.74
  4491.5    1424  4521.6 1420.07  4561.6  1418.1  4601.7 1413.34  4667.2 1407.65
  4691.9 1408.09  4882.2 1401.56  4892.2 1400.96  4922.3 1395.76  4929.3 1395.74
  4932.1 1395.24  4935.3 1395.74  4984.5 1395.81    5283 1395.94    5293 1396.29
  5309.1 1400.02  5322.5 1403.51  5327.5 1403.25  5353.1  1411.9  5403.2 1433.42
  5423.2 1440.94  5443.3 1450.26  5453.3 1453.54  5543.4 1462.27  5635.3 1462.22
#Mann= 6 ,-1 , 0
  4218.6     .05       0  4263.9      .1       0  4929.3    .033       0
  4935.3      .1       0  4984.5     .05       0  5309.1     .16       0
Bank Sta=4929.3,4935.3
XS Rating Curve= 0 ,0
Exp/Cntr=0.3,0.1

Type RM Length L Ch R = 1 ,11355   ,80,80,80
BEGIN DESCRIPTION:
Mapping XS 4485ff99
END DESCRIPTION:
XS GIS Cut Line= 4
      2911199.86      10028096.6      2911185.97     10027537.58
      2911085.27     10026867.44      2910949.84     10026600.04
#Sta/Elev= 30
  4050.8  1424.8  4113.7 1426.13  4203.7 1424.32  4243.7 1420.46  4308.4 1419.12
  4413.8 1409.17  4563.8 1399.02  4583.8 1395.83  4624.9 1395.69  4627.7 1395.19
  4630.9 1395.69  4672.9 1395.85  5159.9 1395.98  5190.3 1396.35  5217.6 1401.35
  5229.1 1405.52  5234.2  1398.9    5251 1409.76  5261.1 1413.71    5287 1419.28
  5294.5 1414.69  5311.2 1419.65  5316.8 1417.83  5405.9 1427.55  5444.9 1428.79
  5450.5 1430.54  5511.7  1435.6  5517.3 1433.88    5534 1437.39  5587.4  1442.1
#Mann= 5 ,-1 , 0
  4050.8      .1       0  4624.9    .033       0  4630.9      .1       0
  4672.9     .05       0  5217.6     .16       0
Bank Sta=4624.9,4630.9
XS Rating Curve= 0 ,0
Exp/Cntr=0.3,0.1

Type RM Length L Ch R = 1 ,11275   ,116,116,116
BEGIN DESCRIPTION:
Mapping XS 510a89fc
END DESCRIPTION:
XS GIS Cut Line= 4
      2911284.35     10028085.32      2911266.12     10027551.43
      2911164.55     10026882.16      2910966.66      10026572.3
#Sta/Elev= 30
  4036.1 1422.93  4237.8 1418.97  4327.9 1409.65  4477.9 1400.19    4525 1399.51
  4527.7 1399.01    4531 1399.51  4608.4  1405.2    4818 1406.12  5012.5 1406.31
  5120.2 1408.52  5164.7 1413.33  5183.9 1419.27  5188.9 1418.31  5243.9 1427.48
  5401.7 1428.95  5416.9 1429.73  5432.2 1433.88  5438.1 1432.29  5453.3 1436.56
  5474.5 1435.61  5489.7 1440.23  5510.8 1439.56  5541.3 1444.36  5547.2 1442.31
  5562.4 1446.23  5568.4 1444.06  5583.6 1447.15  5589.5 1444.61  5614.9 1444.67
#Mann= 5 ,-1 , 0
  4036.1      .1       0    4525    .033       0    4531      .1       0
    4818     .05       0  5012.5     .16       0
Bank Sta=4525,4531
XS Rating Curve= 0 ,0
Exp/Cntr=0.3,0.1

Type RM Length L Ch R = 1 ,11159   ,165,165,165
BEGIN DESCRIPTION:
Mapping XS d374d9bb
END DESCRIPTION:
XS GIS Cut Line= 4
      2911360.45     10028078.39      2911382.15     10027579.25
      2911304.02     10027015.01      2911034.92     10026559.27
#Sta/Elev= 30
  4022.7 1420.67  4087.3 1420.01  4237.6 1409.83  4367.7 1405.78    4538 1396.31
  4589.6 1403.72  4638.9 1393.58  4941.8 1384.77    4962 1383.13  4979.2 1378.37
  5002.1 1372.66  5052.8 1378.11  5096.1 1382.48  5111.8 1393.74  5117.6 1394.29
  5133.2 1402.08  5148.9 1415.35  5154.7  1415.3  5170.3 1424.55  5330.3 1433.43
  5367.4 1438.26  5388.8 1437.06  5404.4 1442.19  5410.2 1440.22  5425.9 1444.51
  5447.3 1443.64    5463 1449.76  5468.8 1447.65  5484.4 1452.56  5621.2 1455.94
#Mann= 4 ,-1 , 0
  4022.7      .1       0    4538     .16       0  4979.2     .07       0
  5052.8     .16       0
Bank Sta=4979.2,5052.8
XS Rating Curve= 0 ,0
Exp/Cntr=0.3,0.1

Type RM Length L Ch R = 1 ,10994   ,159,159,159
BEGIN DESCRIPTION:
UNT 1032 IN LATR 23.0
END DESCRIPTION:
XS GIS Cut Line= 3
      2911844.23     10028106.08      2911531.74     10027121.75
      2911043.27     10026518.96
#Sta/Elev= 30
    3836 1425.69  3879.9 1424.48  4007.7  1418.7  4066.9  1405.4  4121.7 1387.46
  4142.7  1385.9  4153.2 1382.29  4181.3 1386.16  4216.2 1385.85    4271 1392.78
  4469.8 1392.31  4551.9 1388.05  4677.8 1389.16  4733.2 1384.93    4962 1376.03
    4997 1369.94    5026 1375.52  5046.8 1376.51  5054.7 1378.02  5069.1 1386.18
  5118.7 1417.63    5133 1424.24  5147.4 1426.81  5331.3 1439.35  5353.6 1443.88
  5409.6 1448.45  5431.9 1453.07  5566.3 1458.09  5587.1 1460.92  5644.6 1461.09
#Mann= 6 ,-1 , 0
    3836      .1       0  3879.9     .16       0  4181.3      .1       0
    4962     .05       0    4962     .07       0  5046.8     .16       0
Bank Sta=4962,5046.8
XS Rating Curve= 0 ,0
Exp/Cntr=0.3,0.1

Type RM Length L Ch R = 1 ,10835   ,237,237,237
BEGIN DESCRIPTION:
UNT 1032 IN LATR 22.0
END DESCRIPTION:
XS GIS Cut Line= 2
      2912255.71     10027913.43      2911234.84     10026434.21
#Sta/Elev= 30
  3788.3 1412.23    3808 1408.58  3879.7 1402.61  3951.3 1400.57  3981.1 1397.27
  4130.5  1389.9  4282.6  1374.3  4303.6 1380.81  4339.4 1383.23  4497.6 1385.05
  4807.9 1376.47  4957.3 1374.44  4966.1 1374.12  5001.7 1369.16    5008  1370.2
  5015.1 1374.62  5022.9 1382.64    5029 1385.26  5043.9 1396.84  5058.7 1410.71
  5073.6 1417.18    5088 1420.28  5136.6 1425.56  5252.8 1428.96  5375.2 1437.21
  5425.9 1440.94  5452.9 1445.54  5476.6 1446.15  5518.5 1453.03  5585.6 1455.49
#Mann= 3 ,-1 , 0
  3788.3      .1       0  4957.3     .07       0  5015.1      .1       0
#XS Ineff= 1 ,-1
 4065.34  4312.5 1381.53
Permanent Ineff=
       T
Bank Sta=4966.1,5015.1
XS Rating Curve= 0 ,0
Exp/Cntr=0.3,0.1

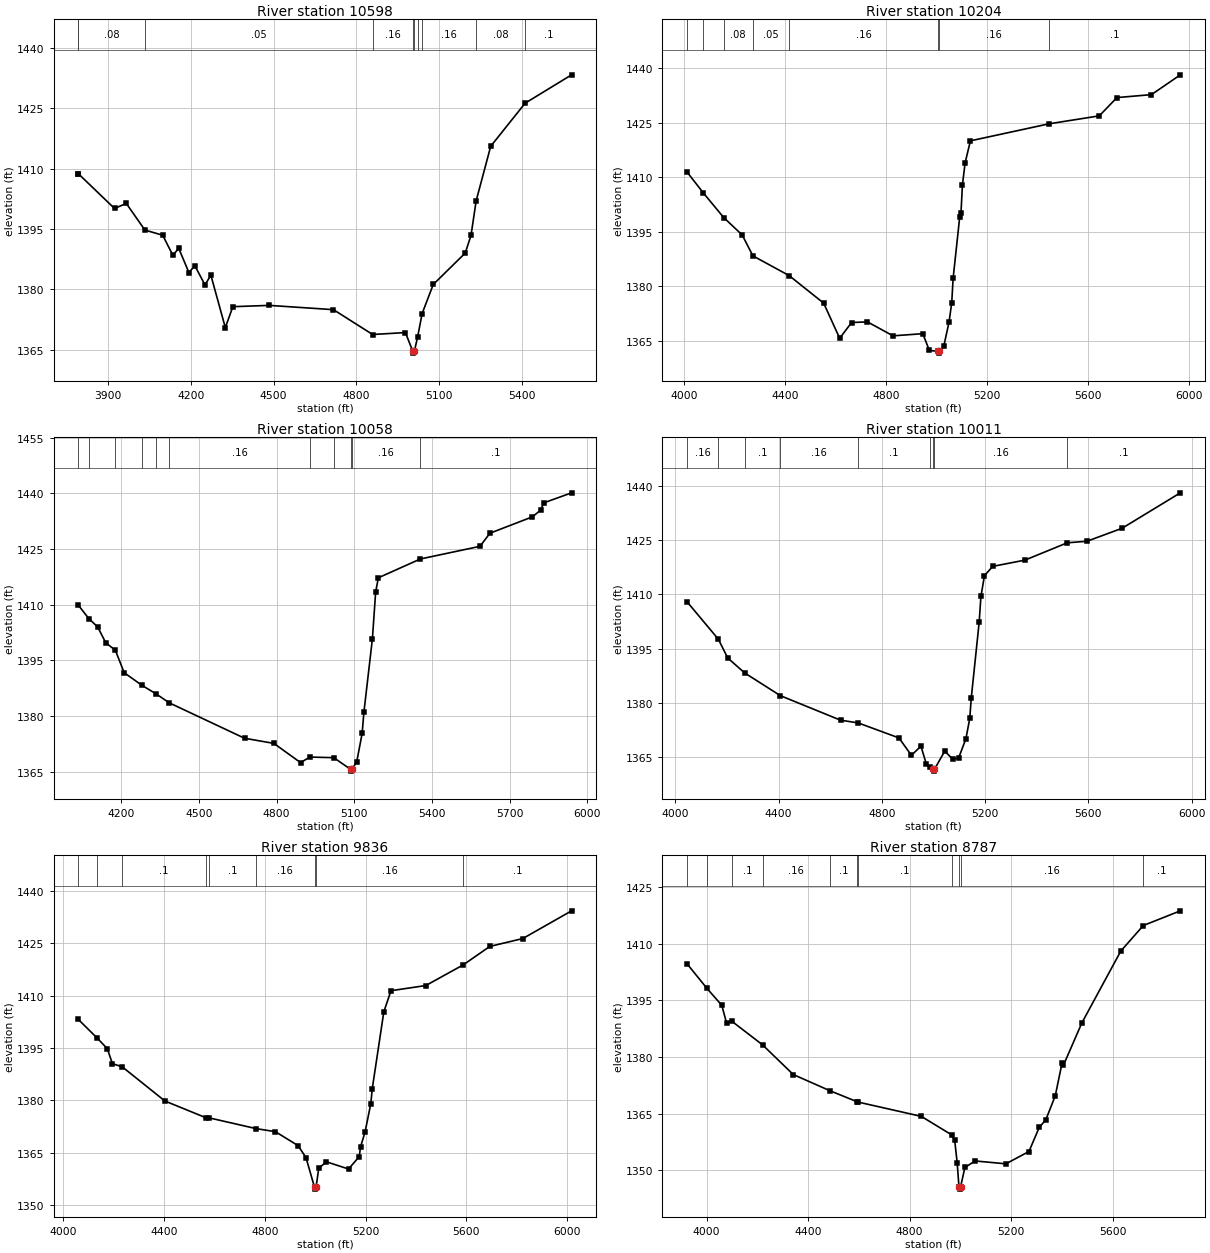
Type RM Length L Ch R = 1 ,10598   ,394,394,394
BEGIN DESCRIPTION:
UNT 1032 IN LATR 21.0
END DESCRIPTION:
XS GIS Cut Line= 3
      2912411.97     10027840.53      2911849.45     10026913.41
      2911443.35     10026340.71
#Sta/Elev= 30
  3792.4 1408.74  3792.8 1408.72  3923.8 1400.09  3966.5 1401.34  4033.9 1394.73
  4098.3 1393.46  4135.1 1388.48  4156.4  1390.2  4193.3 1384.18  4214.6  1385.9
  4251.4 1381.14  4272.8 1383.54  4325.1 1370.53  4352.3 1375.73  4484.1 1376.05
  4716.7 1374.99  4858.5 1368.83  4977.1 1369.31  5003.7 1364.71  5006.4 1364.21
  5009.7 1364.71  5021.4 1368.23  5037.7 1374.03    5078 1381.24  5193.7 1389.03
  5214.6 1393.39  5233.4 1402.01    5286 1415.52  5410.7 1426.21  5578.9 1433.24
#Mann= 10 ,-1 , 0
  3792.4     .05       0  3792.8     .08       0  4033.9     .05       0
  4858.5     .16       0  5003.7     .07       0  5009.7     .16       0
  5021.4     .08       0  5037.7     .16       0  5233.4     .08       0
  5410.7      .1       0
Bank Sta=5003.7,5009.7
XS Rating Curve= 0 ,0
Exp/Cntr=0.3,0.1

Type RM Length L Ch R = 1 ,10204   ,368,368,368
BEGIN DESCRIPTION:
UNT 1032 IN LATR 20.0
END DESCRIPTION:
XS GIS Cut Line= 3
      2912464.02     10027856.08      2912021.32     10026559.25
       2911885.9     10025991.49
#Sta/Elev= 30
  4010.3 1411.45  4074.6 1405.73  4155.9 1398.91    4229 1394.14  4271.4  1388.4
  4414.8 1382.98  4551.7 1375.41  4615.1 1365.76  4662.3 1370.08    4725 1370.27
  4826.4 1366.43  4944.3 1367.02  4970.3 1362.42  5003.9 1362.18  5006.7 1361.68
  5009.9 1362.18  5027.2 1363.52  5048.3 1370.24  5058.9 1375.53  5064.3 1382.19
  5090.3 1398.95  5095.6 1400.28  5101.1 1407.77  5111.7 1413.88  5132.8 1419.99
  5443.9 1424.66  5643.3 1426.85  5713.1 1431.87  5849.8 1432.68  5964.3 1438.12
#Mann= 8 ,-1 , 0
  4010.3     .05       0  4074.6     .16       0  4155.9     .08       0
  4271.4     .05       0  4414.8     .16       0  5003.9     .07       0
  5009.9     .16       0  5443.9      .1       0
Bank Sta=5003.9,5009.9
XS Rating Curve= 0 ,0
Exp/Cntr=0.3,0.1

Type RM Length L Ch R = 1 ,10058   ,47,47,47
BEGIN DESCRIPTION:
Mapping XS 0aa91d5b
END DESCRIPTION:
XS GIS Cut Line= 6
      2912497.37      10027836.8      2912286.96     10026991.74
      2912283.05     10026949.22      2912271.07     10026919.53
      2912265.86     10026875.26      2912000.84     10025999.97
#Sta/Elev= 30
    4034 1409.92  4074.9 1406.27  4109.3 1403.99  4140.2 1399.75  4177.4 1397.72
  4211.5 1391.67  4279.9 1388.27  4335.9  1385.9  4385.8 1383.53  4676.1 1373.99
  4789.4  1372.6  4892.5 1367.41  4928.4 1368.91  5020.6 1368.75  5085.3 1365.62
  5088.1 1365.12  5091.3 1365.62  5109.3 1367.63  5130.1 1375.28  5136.9 1380.94
  5169.8 1400.84  5182.4 1413.47  5192.8 1417.27    5355 1422.34  5585.2 1425.75
  5623.3 1429.28  5787.7 1433.71  5819.9 1435.55  5831.1 1437.47  5938.8 1440.18
#Mann= 11 ,-1 , 0
    4034     .05       0  4074.9     .16       0  4177.4     .05       0
  4279.9      .1       0  4335.9     .05       0  4385.8     .16       0
  4928.4      .1       0  5020.6     .16       0  5085.3     .07       0
  5091.3     .16       0    5355      .1       0
Bank Sta=5085.3,5091.3
XS Rating Curve= 0 ,0
Exp/Cntr=0.3,0.1

Type RM Length L Ch R = 1 ,10011   ,175,175,175
BEGIN DESCRIPTION:
Mapping XS c194902b
END DESCRIPTION:
XS GIS Cut Line= 3
      2912525.15      10027817.7      2912268.21     10026682.29
      2912049.72     10025967.88
#Sta/Elev= 30
  4045.2 1408.01  4166.7 1397.64  4203.1 1392.45  4268.6 1388.32  4406.9 1382.03
  4640.3 1375.24  4708.1  1374.5  4866.4 1370.34  4914.6 1365.53  4951.5 1368.06
    4972 1363.23  4985.9  1362.2    4998 1361.66  5000.7 1361.16    5004 1361.66
  5043.8 1366.71  5074.6 1364.45  5097.5 1364.79  5125.8 1370.13  5140.7 1375.77
  5146.3 1381.28  5177.1 1402.33  5183.9 1409.48  5197.6  1415.2  5229.7 1417.78
  5354.2  1419.5  5518.2 1424.29  5594.7 1424.72  5730.7 1428.31  5956.4 1438.11
#Mann= 9 ,-1 , 0
  4045.2     .16       0  4166.7     .05       0  4268.6      .1       0
  4406.9     .16       0  4708.1      .1       0  4985.9     .16       0
    4998     .07       0    5004     .16       0  5518.2      .1       0
Bank Sta=4998,5004
XS Rating Curve= 0 ,0
Exp/Cntr=0.3,0.1

Type RM Length L Ch R = 1 ,9836    ,1049,1049,1049
BEGIN DESCRIPTION:
UNT 1032 IN LATR 19.0
END DESCRIPTION:
XS GIS Cut Line= 3
      2912625.48     10027777.95      2912458.82     10026684.25
      2912104.77     10025908.45
#Sta/Elev= 30
  4058.7 1403.22  4133.4 1397.89  4174.2 1394.81  4194.5 1390.51  4233.6 1389.59
  4402.9 1379.79  4565.3    1375  4577.2 1374.97  4764.1 1371.88  4841.9 1370.98
  4931.5 1366.99  4963.2 1363.55  4997.1    1355  4999.8  1354.5  5003.1    1355
  5013.8 1360.49  5044.2 1362.34  5132.2 1360.27  5174.5 1363.83    5180 1366.69
  5197.6 1370.87  5220.6 1379.06  5226.1 1383.23  5272.2 1405.38  5300.7 1411.44
  5438.9 1412.92  5587.5 1418.85  5693.2 1424.15  5823.9  1426.4  6017.8 1434.36
#Mann= 9 ,-1 , 0
  4058.7     .16       0  4133.4     .05       0  4233.6      .1       0
  4565.3     .16       0  4577.2      .1       0  4764.1     .16       0
  4997.1     .07       0  5003.1     .16       0  5587.5      .1       0
Bank Sta=4997.1,5003.1
XS Rating Curve= 0 ,0
Exp/Cntr=0.3,0.1

Type RM Length L Ch R = 1 ,8787    ,750,750,750
BEGIN DESCRIPTION:
UNT 1032 IN LATR 18.0
END DESCRIPTION:
XS GIS Cut Line= 3
      2912745.28     10027788.45      2912932.78     10026423.83
      2913104.07       10025884.
#Sta/Elev= 30
  3922.6 1404.74  4001.7 1398.17  4059.9  1393.7  4078.8 1388.96  4100.4 1389.43
  4220.3 1383.23  4341.2 1375.36  4485.5 1371.07    4594 1368.11  4597.4 1368.04
  4845.9 1364.26  4964.9 1359.38  4977.1 1358.07  4987.2 1351.94  4994.3 1345.47
  4997.1 1344.97  5000.3 1345.47  5017.5 1350.72  5057.9 1352.44    5179 1351.68
  5269.9 1354.94  5310.6 1361.36  5336.1 1363.32  5373.6 1369.71  5400.7 1378.53
  5405.9 1377.83  5478.5 1389.06  5631.8 1408.09  5720.4 1414.86  5866.4 1418.76
#Mann= 11 ,-1 , 0
  3922.6      .1       0  4001.7     .05       0  4100.4      .1       0
  4220.3     .16       0  4485.5      .1       0    4594     .16       0
  4597.4      .1       0  4964.9     .16       0  4994.3     .07       0
  5000.3     .16       0  5720.4      .1       0
Bank Sta=4994.3,5000.3
XS Rating Curve= 0 ,0
Exp/Cntr=0.3,0.1

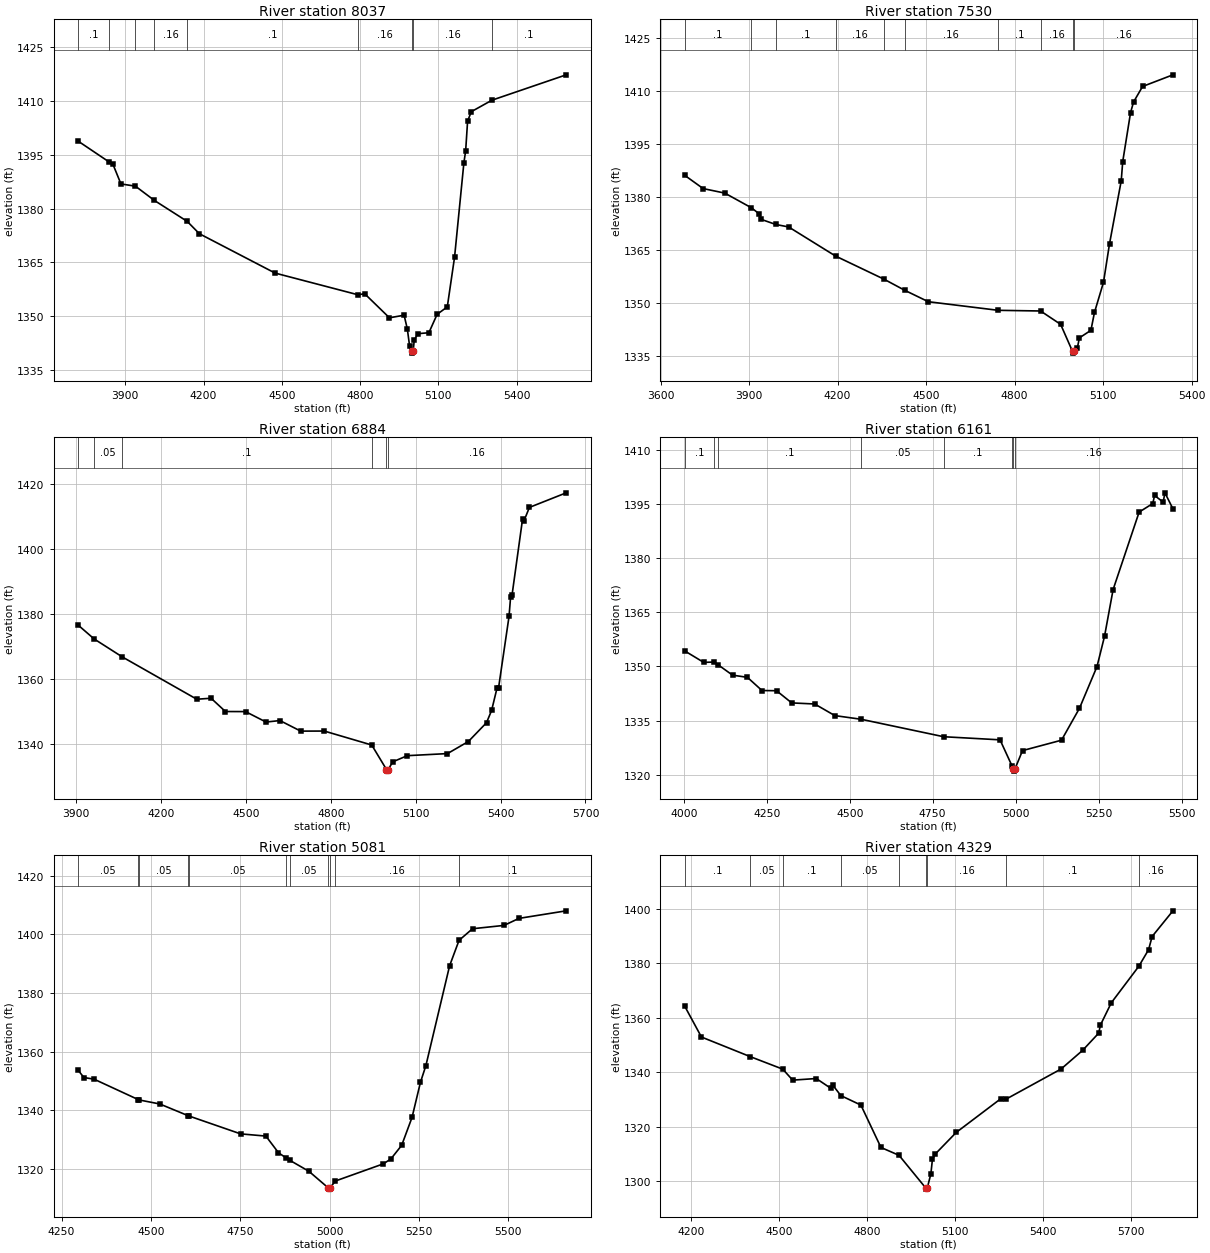
Type RM Length L Ch R = 1 ,8037    ,507,507,507
BEGIN DESCRIPTION:
UNT 1032 IN LATR 17.0
END DESCRIPTION:
XS GIS Cut Line= 3
      2912906.74     10027830.08      2913354.66     10026481.12
      2913687.97     10026179.06
#Sta/Elev= 30
  3718.6 1398.83  3836.6 1393.06  3851.7 1392.53  3883.3 1386.87  3938.8 1386.25
  4011.8 1382.26  4137.4 1376.43  4183.9    1373  4474.2 1362.03  4791.7 1355.99
  4817.4 1356.28  4912.4 1349.57  4968.6  1350.3    4981 1346.43  4989.7 1341.68
  4997.3 1340.23    5000 1339.73  5003.3 1340.23  5007.4 1343.36  5021.3 1345.15
  5063.5 1345.41  5095.1 1350.54  5134.1 1352.62  5161.9 1366.44  5197.7 1392.75
  5204.5 1396.12  5211.9 1404.37  5226.1    1407  5305.1  1410.2  5589.8 1417.27
#Mann= 9 ,-1 , 0
  3718.6      .1       0  3836.6     .05       0  3938.8      .1       0
  4011.8     .16       0  4137.4      .1       0  4791.7     .16       0
  4997.3     .07       0  5003.3     .16       0  5305.1      .1       0
Bank Sta=4997.3,5003.3
XS Rating Curve= 0 ,0
Exp/Cntr=0.3,0.1

Type RM Length L Ch R = 1 ,7530    ,646,646,646
BEGIN DESCRIPTION:
UNT 1032 IN LATR 16.0
END DESCRIPTION:
XS GIS Cut Line= 3
      2913141.11      10028022.8      2913641.12     10027210.29
      2913776.52     10026522.84
#Sta/Elev= 30
  3681.8 1386.15  3744.4  1382.4  3817.8 1381.12  3908.2 1376.96  3933.8 1375.29
  3939.6 1373.74  3990.8 1372.25  4034.3 1371.55  4193.1 1363.33  4358.5 1356.74
  4426.9 1353.68  4507.6 1350.42  4744.3 1347.99    4888  1347.8  4955.9 1344.03
  4996.2 1336.39    4999 1335.89  5002.2 1336.39  5012.4 1337.29  5019.6 1340.21
  5058.6 1342.34  5070.6 1347.38  5101.2 1355.91  5121.6 1366.78  5161.3 1384.58
  5166.4 1390.02  5192.9 1403.85  5203.1 1406.87  5233.7 1411.26  5336.5 1414.55
#Mann= 10 ,-1 , 0
  3681.8      .1       0  3908.2     .05       0  3990.8      .1       0
  4193.1     .16       0  4358.5      .1       0  4426.9     .16       0
  4744.3      .1       0    4888     .16       0  4996.2     .07       0
  5002.2     .16       0
Bank Sta=4996.2,5002.2
XS Rating Curve= 0 ,0
Exp/Cntr=0.3,0.1

Type RM Length L Ch R = 1 ,6884    ,723,723,723
BEGIN DESCRIPTION:
UNT 1032 IN LATR 14.0
END DESCRIPTION:
XS GIS Cut Line= 3
      2914266.11     10028028.03      2914401.53     10027205.08
      2914198.82     10026337.05
#Sta/Elev= 30
  3906.6 1376.64  3963.8 1372.33  4062.8 1366.82  4326.5 1353.77  4377.1 1354.07
  4427.8 1349.98  4498.8 1349.96  4571.3 1346.74  4620.4  1347.2  4693.7 1343.95
    4777 1343.97  4944.8 1339.67  4996.9 1332.13  4999.7 1331.63  5002.9 1332.13
  5019.3  1334.5  5070.6 1336.39  5212.5 1337.03  5286.3 1340.75  5350.4 1346.54
  5368.4 1350.32  5387.8 1357.29  5392.9 1357.23    5430 1379.27  5435.4 1385.15
  5440.6 1385.83  5477.9 1409.31  5483.1 1408.75  5501.9 1412.83    5632 1417.32
#Mann= 6 ,-1 , 0
  3906.6      .1       0  3963.8     .05       0  4062.8      .1       0
  4944.8     .16       0  4996.9     .07       0  5002.9     .16       0
Bank Sta=4996.9,5002.9
XS Rating Curve= 0 ,0
Exp/Cntr=0.3,0.1

Type RM Length L Ch R = 1 ,6161    ,1080,1080,1080
BEGIN DESCRIPTION:
UNT 1032 IN LATR 13.0
END DESCRIPTION:
XS GIS Cut Line= 4
      2914542.14     10027725.95      2914885.91      10026965.5
      2914964.03     10026673.83      2914855.11     10026357.44
#Sta/Elev= 30
  4002.8 1354.31  4060.1 1351.13  4092.1 1351.22  4102.5 1350.53    4147 1347.59
  4191.8 1346.99  4235.7 1343.34  4279.6 1343.28  4325.3 1339.91  4394.6 1339.61
  4455.2  1336.4  4534.6 1335.38  4783.2 1330.55    4953 1329.69  4989.3 1322.43
  4991.5 1321.53  4994.2 1321.03  4997.5 1321.53  5020.7 1326.71  5138.2 1329.59
  5192.3 1338.42  5245.2 1349.98  5267.8 1358.33  5293.7 1371.28  5372.1 1392.72
  5413.3 1395.09  5418.6 1397.33  5444.5 1395.47  5449.8 1398.05  5473.9 1393.63
#Mann= 8 ,-1 , 0
  4002.8      .1       0  4092.1     .05       0  4102.5      .1       0
  4534.6     .05       0  4783.2      .1       0  4989.3     .16       0
  4991.5     .07       0  4997.5     .16       0
Bank Sta=4991.5,4997.5
XS Rating Curve= 0 ,0
Exp/Cntr=0.3,0.1

Type RM Length L Ch R = 1 ,5081    ,752,752,752
BEGIN DESCRIPTION:
UNT 1032 IN LATR 11.0
END DESCRIPTION:
XS GIS Cut Line= 3
      2914760.87     10027819.69       2915380.7     10027236.33
      2915583.66     10026762.76
#Sta/Elev= 30
    4296 1353.68  4312.6 1351.12    4341 1350.56  4464.9 1343.57  4467.2 1343.46
  4525.1 1342.08  4604.5 1338.07  4606.1    1338  4751.2 1331.87    4822 1331.11
  4857.2 1325.42  4879.1  1323.6  4888.4 1322.87  4942.2  1319.1  4995.8 1313.49
  4998.6 1312.99  5001.8 1313.49  5016.5 1315.77  5150.7 1321.63  5171.8 1323.31
    5202 1327.96    5231 1337.51  5254.5 1349.49  5269.7 1355.18  5336.1  1389.3
  5362.5 1397.98  5400.2 1401.95  5488.5 1403.09  5530.2 1405.49  5662.4 1408.07
#Mann= 11 ,-1 , 0
    4296     .05       0  4464.9      .1       0  4467.2     .05       0
  4604.5      .1       0  4606.1     .05       0  4879.1     .16       0
  4888.4     .05       0  4995.8     .04       0  5001.8     .05       0
  5016.5     .16       0  5362.5      .1       0
Bank Sta=4995.8,5001.8
XS Rating Curve= 0 ,0
Exp/Cntr=0.3,0.1

Type RM Length L Ch R = 1 ,4329    ,468,468,468
BEGIN DESCRIPTION:
UNT 1032 IN LATR 9.0
END DESCRIPTION:
XS GIS Cut Line= 4
      2915896.32      10028470.7      2915854.66     10028017.58
      2915958.82     10027444.66      2915735.35     10026857.39
#Sta/Elev= 30
  4177.7 1364.21  4234.9 1352.87  4401.6 1345.67  4512.3 1341.09  4546.2 1337.06
  4626.6 1337.65  4677.1 1334.01  4682.2 1335.33  4710.6 1331.38  4778.9 1327.92
  4847.3 1312.37    4909 1309.49  4999.5 1297.59  5002.3 1297.09  5005.5 1297.59
  5017.6 1302.66  5022.9 1307.97    5033 1310.01  5104.2 1317.89  5255.9 1330.22
  5273.2 1330.03  5462.1 1341.16  5535.5    1348  5590.4 1354.32  5595.8 1357.19
  5633.3 1365.44    5727  1378.8  5760.4  1384.9  5772.4 1389.73  5843.4 1399.15
#Mann= 9 ,-1 , 0
  4177.7      .1       0  4401.6     .05       0  4512.3      .1       0
  4710.6     .05       0    4909     .16       0  4999.5     .07       0
  5005.5     .16       0  5273.2      .1       0    5727     .16       0
Bank Sta=4999.5,5005.5
XS Rating Curve= 0 ,0
Exp/Cntr=0.3,0.1

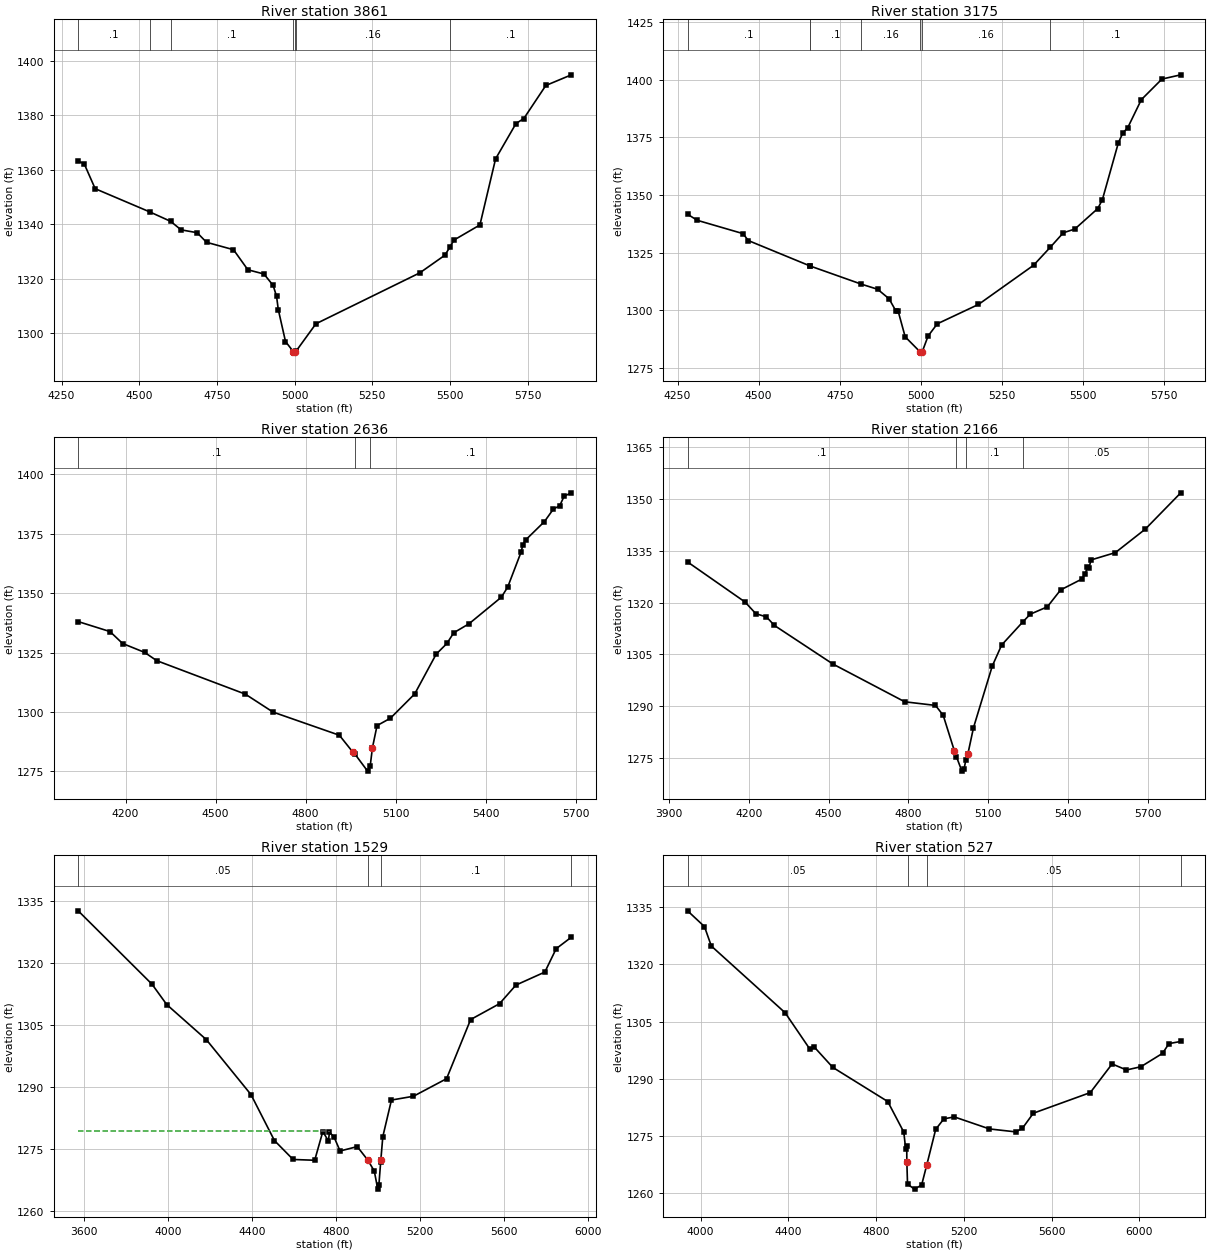
Type RM Length L Ch R = 1 ,3861    ,686,686,686
BEGIN DESCRIPTION:
UNT 1032 IN LATR 8.0
END DESCRIPTION:
XS GIS Cut Line= 4
      2916521.32     10028392.53      2916453.62     10027923.83
      2916135.91      10027220.7      2916089.03     10026882.17
#Sta/Elev= 30
  4303.6 1363.16  4322.6 1362.33  4358.2  1353.1  4534.4 1344.55  4601.2  1341.1
  4634.5 1337.99  4686.3 1336.94  4716.6 1333.41  4803.3 1330.69  4849.5 1323.32
  4901.2 1321.77  4930.9 1317.57  4941.9 1313.53  4947.4 1308.71  4970.6 1296.97
  4996.2  1293.2  4998.9  1292.7  5002.2  1293.2  5005.7 1293.59  5068.5 1303.48
  5402.8 1322.19  5483.4 1328.66  5500.6 1331.82  5512.5 1334.22  5596.2 1339.79
  5646.6 1364.07  5712.3 1377.04  5737.5 1378.88  5808.2 1391.01  5890.5 1394.93
#Mann= 7 ,-1 , 0
  4303.6      .1       0  4534.4     .05       0  4601.2      .1       0
  4996.2     .07       0  5002.2      .1       0  5005.7     .16       0
  5500.6      .1       0
Bank Sta=4996.2,5002.2
XS Rating Curve= 0 ,0
Exp/Cntr=0.3,0.1

Type RM Length L Ch R = 1 ,3175    ,539,539,539
BEGIN DESCRIPTION:
UNT 1032 IN LATR 6.0
END DESCRIPTION:
XS GIS Cut Line= 3
      2917245.27     10027830.05      2917021.32     10027423.83
      2916255.67     10026694.63
#Sta/Elev= 30
  4280.7 1341.68  4310.8 1339.06  4451.8 1333.29  4467.9  1330.3  4657.5 1319.34
    4658  1319.3  4815.9 1311.44  4866.9 1309.18  4902.1 1305.08  4923.5 1299.72
  4930.4  1299.6  4951.9 1288.58  4998.2 1282.01    5001 1281.51  5004.2 1282.01
  5022.6 1288.93  5050.9 1294.21    5178 1302.61  5347.8 1319.57  5399.3 1327.36
  5439.7 1333.67  5475.2 1335.28    5546 1344.17  5560.2 1348.03  5609.5 1372.68
  5623.7 1377.04  5637.8 1379.04  5680.3 1391.35  5743.8 1400.27  5801.9 1402.11
#Mann= 7 ,-1 , 0
  4280.7      .1       0  4657.5     .16       0    4658      .1       0
  4815.9     .16       0  4998.2     .07       0  5004.2     .16       0
  5399.3      .1       0
Bank Sta=4998.2,5004.2
XS Rating Curve= 0 ,0
Exp/Cntr=0.3,0.1

Type RM Length L Ch R = 1 ,2636    ,470,470,470
BEGIN DESCRIPTION:
UNT 1032 IN LATR 5.0
END DESCRIPTION:
XS GIS Cut Line= 4
      2917464.04     10027694.67      2917271.32      10027090.5
      2916984.87     10026569.66      2916642.29     10026336.09
#Sta/Elev= 30
  4042.1 1338.04  4148.1 1333.84    4190 1328.82  4263.5 1325.07  4303.7  1321.6
  4598.8 1307.52  4691.1 1299.96  4912.2 1290.21  4957.3 1283.08    4963 1282.46
  5006.3  1275.1    5015 1277.29  5022.5 1284.98  5037.8 1294.27  5082.3 1297.36
  5163.3  1307.6  5234.8 1324.33  5270.7 1328.86  5293.3 1333.34  5344.2 1337.12
  5451.9  1348.3  5472.9  1352.5  5517.6 1367.26  5523.7 1370.38  5532.6 1372.37
  5595.5 1380.13  5625.4 1385.41  5646.3 1386.79  5661.3 1390.84  5685.3 1392.24
#Mann= 3 ,-1 , 0
  4042.1      .1       0    4963     .05       0    5015      .1       0
Bank Sta=4957.3,5022.5
XS Rating Curve= 0 ,0
Exp/Cntr=0.3,0.1

Type RM Length L Ch R = 1 ,2166    ,637,637,637
BEGIN DESCRIPTION:
UNT 1032 IN LATR 4.0
END DESCRIPTION:
XS GIS Cut Line= 4
       2917633.3     10027520.23      2917615.94     10026691.19
      2917138.51     10026079.21      2916901.68      10026001.7
#Sta/Elev= 30
  3969.5 1331.76    4186 1320.13  4226.1 1316.77  4266.1 1315.84  4296.1 1313.36
  4516.1 1302.18  4786.2 1291.24  4901.8 1290.19  4930.7 1287.34  4973.1 1276.95
  4980.5 1275.33  5001.1 1271.15  5009.4 1271.88  5015.8 1274.32  5023.8 1276.21
  5044.7 1283.75  5115.3  1301.6  5150.6  1307.7  5230.7 1314.43  5258.2 1316.62
  5322.4 1318.76  5372.2 1323.65  5450.9 1326.75  5465.3  1328.3  5471.7 1330.28
  5479.8  1330.1  5486.1 1332.33  5578.3 1334.47  5690.7 1341.27  5824.1 1351.79
#Mann= 4 ,-1 , 0
  3969.5      .1       0  4980.5     .05       0  5015.8      .1       0
  5230.7     .05       0
Bank Sta=4973.1,5023.8
XS Rating Curve= 0 ,0
Exp/Cntr=0.3,0.1

Type RM Length L Ch R = 1 ,1529    ,1002,1002,1002
BEGIN DESCRIPTION:
UNT 1032 IN LATR 3.0
END DESCRIPTION:
XS GIS Cut Line= 4
      2917689.72     10027546.24      2918049.97     10026387.37
      2917984.87     10026009.77       2917286.1       10025732.
#Sta/Elev= 30
  3571.7 1332.64  3923.2 1314.87  3993.5 1309.93  4181.7 1301.46  4394.6 1288.14
  4506.3 1277.01  4595.1 1272.43    4698 1272.24  4736.7  1279.2  4763.1 1276.91
  4768.4    1279  4789.7 1277.91  4818.9 1274.48  4900.6 1275.55  4951.3 1272.25
  4981.8 1269.63  4998.3 1265.25  5003.6 1266.22  5012.2 1271.84    5013 1272.32
  5022.4 1277.97  5063.5 1286.82  5168.4 1287.74    5326 1291.99  5440.5 1306.31
  5578.1 1310.15  5656.4 1314.66    5794 1317.81    5848 1323.47  5920.4 1326.26
#Mann= 4 ,-1 , 0
  3571.7     .05       0  4951.3    .035       0  5012.2      .1       0
  5920.4     .05       0
#XS Ineff= 2 , 0
         4768.47 1279.32
Permanent Ineff=
       T       T
Bank Sta=4951.3,5013
XS Rating Curve= 0 ,0
Exp/Cntr=0.3,0.1

Type RM Length L Ch R = 1 ,527     ,439,439,439
BEGIN DESCRIPTION:
Mapping XS d62d0f31
END DESCRIPTION:
XS GIS Cut Line= 5
      2918056.27     10027617.46      2918344.47      10026659.1
      2918281.97     10026464.66      2918268.08     10026065.35
      2917740.29     10025697.28
#Sta/Elev= 30
  3940.9 1334.01  4017.9 1329.88  4049.2 1324.79  4385.6 1307.32  4498.2 1297.81
  4517.7 1298.39  4602.7 1293.02  4853.3 1284.08  4926.4 1276.07  4934.9 1271.75
  4939.9 1272.37 4940.34 1268.31  4943.5 1262.44  4975.3 1261.14  5007.7 1262.21
  5031.3 1267.49  5071.9  1276.8  5109.2 1279.54  5156.8 1280.05  5316.9  1276.9
    5437 1276.13    5467 1277.06    5517 1281.02  5776.6 1286.42    5876 1293.92
  5941.4 1292.34  6006.9 1293.18  6105.8 1296.69  6135.1 1299.24  6188.9 1299.81
#Mann= 4 ,-1 , 0
  3940.9     .05       0  4943.5    .035       0  5031.3     .05       0
  6188.9      .1       0
Bank Sta=4940.34,5031.3
XS Rating Curve= 0 ,0
Exp/Cntr=0.3,0.1

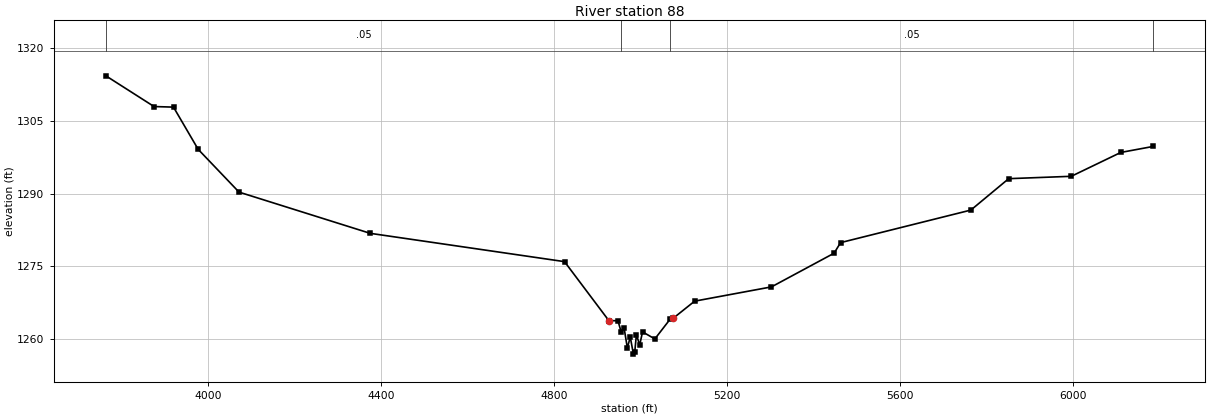
Type RM Length L Ch R = 1 ,88      ,0,0,0
BEGIN DESCRIPTION:
UNT 1032 IN LATR 1.0
END DESCRIPTION:
XS GIS Cut Line= 4
      2918522.42     10027562.92      2918750.03      10026446.6
      2918497.25      10026159.1      2917743.75     10025666.02
#Sta/Elev= 30
  3763.3 1314.34  3874.7 1307.99  3919.7 1307.87  3976.8 1299.14  4071.3  1290.3
  4374.8 1281.78  4824.3 1275.93    4927 1263.72  4947.9 1263.72  4955.5 1261.37
  4962.1 1262.25  4969.7 1258.07  4976.4 1260.36  4983.7 1256.81  4986.9 1257.31
  4990.6 1260.85  4998.2 1258.68  5004.8 1261.41  5033.3 1259.95  5068.4 1264.01
    5076 1264.24  5125.3 1267.76  5303.1 1270.71  5447.9 1277.67    5463 1279.86
  5764.4 1286.59  5851.9 1293.08  5996.7 1293.57  6111.2  1298.5  6185.9 1299.74
#Mann= 4 ,-1 , 0
  3763.3     .05       0  4955.5    .035       0  5068.4     .05       0
  6185.9      .1       0
Bank Sta=4927,5076
XS Rating Curve= 0 ,0
Exp/Cntr=0.3,0.1

Chan Stop Cuts=-1
Use User Specified Reach Order=0
Composite Channel Slope=5