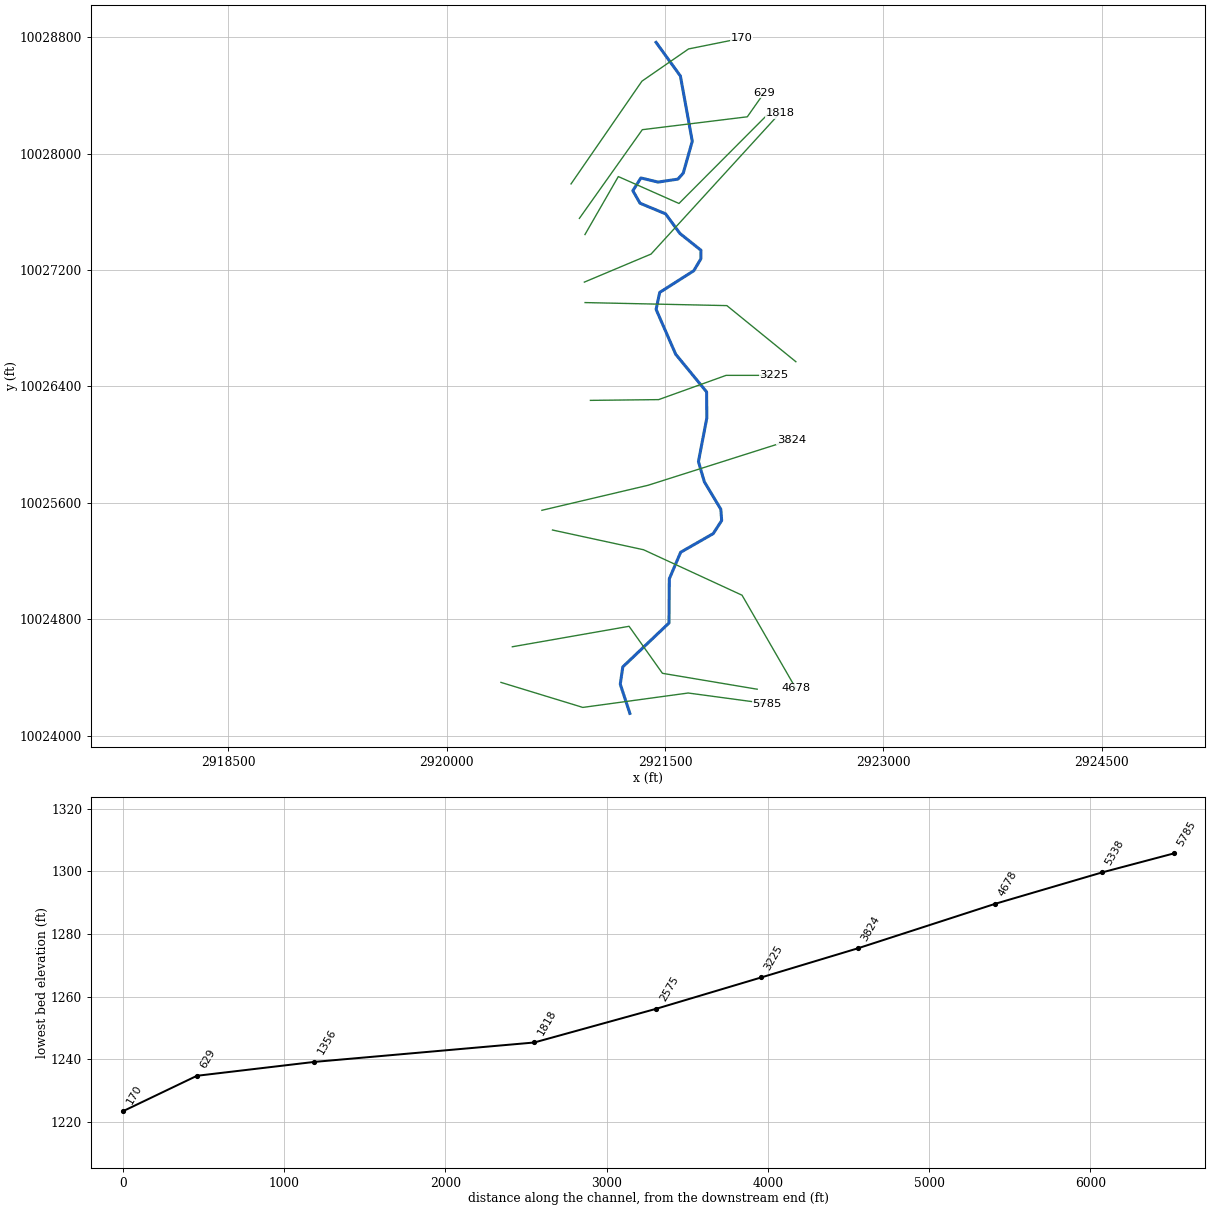
--- UNT 1033 IN LATR.prj (project) ---

Proj Title=UNT 1033 IN LATR Base Level Engineering
Current Plan=p01
Default Exp/Contr=0.3,0.1
English Units
Geom File=g01
Flow File=f01
Plan File=p01
Y Axis Title=Elevation
X Axis Title(PF)=Main Channel Distance
X Axis Title(XS)=Station
BEGIN DESCRIPTION:
UNT 1033 IN LATR
END DESCRIPTION:
DSS Export Rating Curves= 0
DSS Export Rating Curve Sorted= 0
DSS Export Volume Flow Curves= 0
DXF OffsetX= 0
DXF OffsetY= 0
DXF ScaleX= 1
DXF ScaleY= 10

--- UNT 1033 IN LATR.p01 (plan) ---

Plan Title=Multiple Run
Short Identifier=Multiple
Geom File=g01
Flow File=f01
Subcritical Flow
K Sum by GR= 0
Std Step Tol= 0.01
Critical Tol= 0.01
Num of Std Step Trials= 20
Max Error Tol= 0.3
Flow Tol Ratio= 0.001
Split Flow NTrial= 30
Split Flow Tol= 0.02
Split Flow Ratio= 0.02
Log Output Level= 0
Friction Slope Method= 1
Unsteady Friction Slope Method= 2
Unsteady Bridges Friction Slope Method= 1
Parabolic Critical Depth
Global Vel Dist=  1 , 1 , 1
Global Log Level= 0
CheckData=True
Encroach Param= -1, 0, 0, 0
BEGIN DESCRIPTION:
Multiple Run
END DESCRIPTION:

--- UNT 1033 IN LATR.f01 (steady flow) ---

Flow Title=Multiple
Number of Profiles=7
Profile Names=10-year,25-year,50-year,1pct_min,100-year,1pct_plu,500-year
River Rch & RM= UNT 1033 IN LATR,Reach-1,5785
     851    1223    1544    1428    1932    2612    3031
River Rch & RM= UNT 1033 IN LATR,Reach-1,4678
    1218    1782    2277    2128    2878    3892    4612
Boundary for River Rch & Prof#=UNT 1033 IN LATR,Reach-1,1
Up Type=0
Dn Type=3
Dn Slope=0.005
Boundary for River Rch & Prof#=UNT 1033 IN LATR,Reach-1,2
Up Type=0
Dn Type=3
Dn Slope=0.005
Boundary for River Rch & Prof#=UNT 1033 IN LATR,Reach-1,3
Up Type=0
Dn Type=3
Dn Slope=0.005
Boundary for River Rch & Prof#=UNT 1033 IN LATR,Reach-1,4
Up Type=0
Dn Type=3
Dn Slope=0.005
Boundary for River Rch & Prof#=UNT 1033 IN LATR,Reach-1,5
Up Type=0
Dn Type=3
Dn Slope=0.005
Boundary for River Rch & Prof#=UNT 1033 IN LATR,Reach-1,6
Up Type=0
Dn Type=3
Dn Slope=0.005
Boundary for River Rch & Prof#=UNT 1033 IN LATR,Reach-1,7
Up Type=0
Dn Type=3
Dn Slope=0.005

--- UNT 1033 IN LATR.g01 (geometry) ---

Geom Title=Existing Conditions
Program Version=4.10

River Reach=UNT 1033 IN LATR,Reach-1
Reach XY= 30
      2921258.47     10024153.73      2921192.49     10024354.36
      2921209.96     10024473.13      2921527.17     10024774.48
      2921529.46     10025078.15      2921607.53     10025260.72
      2921831.05     10025388.62      2921889.11     10025478.45
      2921883.31     10025556.04      2921770.21     10025744.46
      2921729.66     10025883.64      2921787.28     10026183.82
      2921785.57     10026362.43      2921573.21     10026620.99
      2921438.76     10026929.03      2921463.28      10027045.5
      2921697.48     10027194.59      2921746.09     10027276.16
      2921747.02     10027335.16      2921602.27      10027450.8
      2921503.96     10027585.47      2921328.14     10027658.48
      2921278.99     10027744.39      2921334.17     10027831.95
       2921452.5     10027803.73      2921588.57     10027824.11
        2921625.     10027865.01      2921687.24     10028084.36
      2921605.56     10028532.53      2921438.47     10028763.73

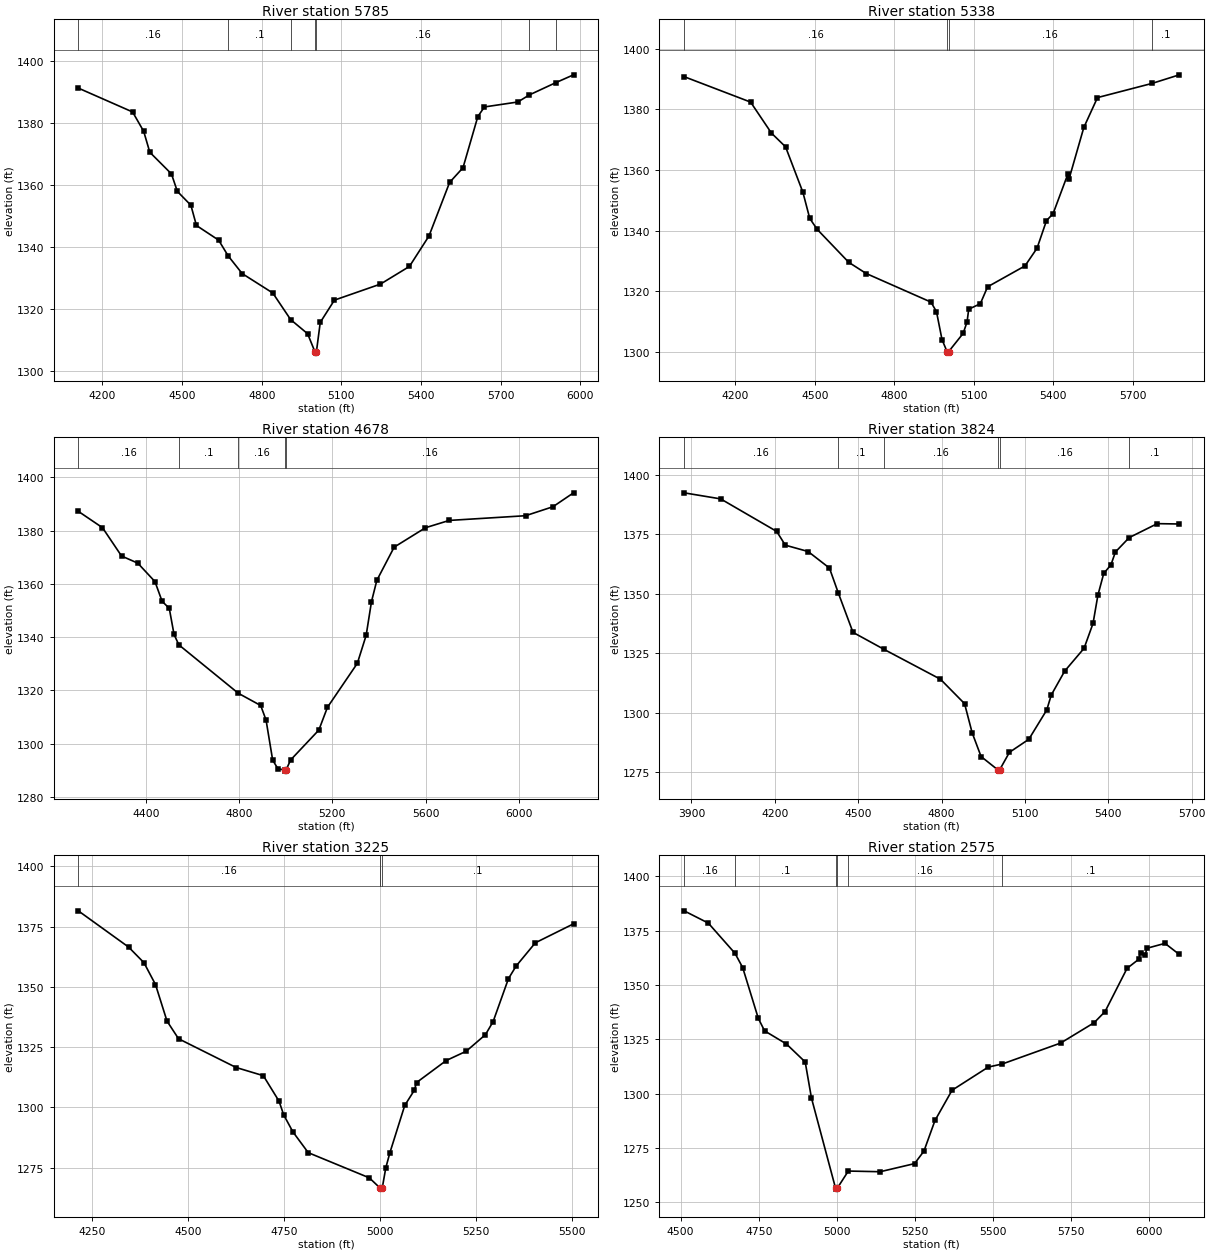
Type RM Length L Ch R = 1 ,5785    ,447,447,447
BEGIN DESCRIPTION:
UNT 1033 IN LATR 12.0
END DESCRIPTION:
XS GIS Cut Line= 4
      2920372.91     10024366.53      2920935.39     10024194.66
      2921659.34     10024293.62      2922201.02      10024220.7
#Sta/Elev= 30
    4109 1391.26  4313.5 1383.55  4355.3  1377.3  4378.3 1370.55  4459.9 1363.55
    4482 1357.92  4533.1 1353.43    4554  1346.9  4637.6 1342.17  4673.3 1337.11
  4726.3 1331.37  4841.6  1325.1    4909  1316.5  4972.8 1311.95    5000 1306.19
  5002.8 1305.69    5006 1306.19  5020.4 1315.61  5073.7  1322.8  5247.2 1327.98
  5356.3 1333.68  5429.9  1343.5  5507.7 1360.81  5558.1 1365.55    5614 1382.08
  5638.8 1385.17  5764.6 1386.77  5807.7 1389.04  5907.8 1393.02  5974.4 1395.54
#Mann= 7 ,-1 , 0
    4109     .16       0  4673.3      .1       0    4909     .16       0
    5000     .07       0    5006     .16       0  5807.7      .1       0
  5907.8     .16       0
Bank Sta=5000,5006
XS Rating Curve= 0 ,0
Exp/Cntr=0.3,0.1

Type RM Length L Ch R = 1 ,5338    ,660,660,660
BEGIN DESCRIPTION:
UNT 1033 IN LATR 11.0
END DESCRIPTION:
XS GIS Cut Line= 4
      2920451.02     10024611.33      2921253.09     10024751.95
      2921482.26     10024429.04      2922133.26     10024319.67
#Sta/Elev= 30
  4006.4 1390.83  4257.6 1382.43  4336.3  1372.2  4389.6 1367.67  4455.1 1352.67
    4481 1344.03  4509.4 1340.41  4628.3 1329.56  4694.2 1325.87  4938.7 1316.44
  4959.6 1313.28  4980.5 1304.06  4999.5  1300.1  5002.2  1299.6  5005.5  1300.1
  5060.4 1306.12  5075.2 1309.94  5081.3 1314.09  5125.1 1315.89  5152.7 1321.48
  5293.9 1328.38  5339.4 1334.22  5375.1 1343.32    5400 1345.62  5455.5 1358.61
  5460.6 1357.17  5516.1 1374.06  5567.7 1383.92  5773.9  1388.6  5876.8 1391.43
#Mann= 4 ,-1 , 0
  4006.4     .16       0  4999.5     .07       0  5005.5     .16       0
  5773.9      .1       0
Bank Sta=4999.5,5005.5
XS Rating Curve= 0 ,0
Exp/Cntr=0.3,0.1

Type RM Length L Ch R = 1 ,4678    ,854,854,854
BEGIN DESCRIPTION:
UNT 1033 IN LATR 9.0
END DESCRIPTION:
XS GIS Cut Line= 4
      2920727.03     10025413.42      2921352.05       10025278.
      2922029.14      10024965.5      2922398.91     10024324.91
#Sta/Elev= 30
    4110 1387.24  4213.8 1381.09  4295.6 1370.45  4365.2 1367.77  4438.9 1360.84
  4469.6 1353.43  4500.3  1350.8  4520.8 1340.99  4541.4 1337.08  4796.6 1318.88
  4892.6 1314.29  4915.6 1308.82    4944 1293.76  4966.9 1290.47  4995.9 1290.13
  4998.6 1289.63  5001.9 1290.13  5020.9 1293.82  5142.1 1305.06    5179  1313.6
  5307.3 1330.13  5345.1 1340.64    5368 1353.31    5391 1361.32  5465.3 1373.78
  5599.7 1381.08  5701.6 1383.82  6029.1 1385.59  6146.8 1388.97  6234.9 1394.19
#Mann= 5 ,-1 , 0
    4110     .16       0  4541.4      .1       0  4796.6     .16       0
  4995.9     .07       0  5001.9     .16       0
Bank Sta=4995.9,5001.9
XS Rating Curve= 0 ,0
Exp/Cntr=0.3,0.1

Type RM Length L Ch R = 1 ,3824    ,599,599,599
BEGIN DESCRIPTION:
UNT 1033 IN LATR 7.0
END DESCRIPTION:
XS GIS Cut Line= 3
      2920654.11     10025548.82       2921383.3      10025720.7
      2922367.72     10026033.22
#Sta/Elev= 30
  3873.7 1392.36  4005.3 1389.81  4206.9 1376.14  4237.8 1370.37    4320 1367.69
  4396.7 1360.74  4428.2  1350.4  4481.4 1333.72    4594 1326.52  4796.2 1314.02
    4883 1303.74  4910.1 1291.56  4942.3 1281.54    5003  1275.9  5005.7  1275.4
    5009  1275.9  5044.4 1283.31  5114.1 1288.78  5178.7 1301.11  5194.8 1307.37
  5243.2 1317.44  5312.9 1327.02  5345.2 1337.49  5362.7 1349.34  5383.7 1358.49
  5409.7  1362.1  5425.7  1367.5  5475.4 1373.55  5576.3 1379.41  5655.7 1379.26
#Mann= 6 ,-1 , 0
  3873.7     .16       0  4428.2      .1       0    4594     .16       0
    5003     .07       0    5009     .16       0  5475.4      .1       0
Bank Sta=5003,5009
XS Rating Curve= 0 ,0
Exp/Cntr=0.3,0.1

Type RM Length L Ch R = 1 ,3225    ,650,650,650
BEGIN DESCRIPTION:
UNT 1033 IN LATR 6.0
END DESCRIPTION:
XS GIS Cut Line= 4
      2920987.47     10026304.04      2921456.22     10026309.25
      2921919.76     10026475.91      2922247.89     10026475.91
#Sta/Elev= 30
    4215 1381.53    4346 1366.49    4386 1360.01    4416 1350.96    4446 1335.79
    4476 1328.48    4626 1316.55  4696.8 1313.16  4737.7 1302.58  4749.9 1296.88
  4773.7 1289.88  4813.7 1281.24  4972.8 1270.79  5000.4 1266.62  5000.5 1266.61
  5003.3 1266.11  5006.5 1266.61  5015.6 1274.89  5026.2 1281.14    5065 1300.81
    5090 1307.12  5095.7 1310.31    5173 1319.44  5225.1  1323.3  5275.1 1330.16
  5295.1 1335.57  5335.1 1353.42  5355.1 1358.64  5405.1 1368.27  5504.5 1376.13
#Mann= 4 ,-1 , 0
    4215     .16       0  5000.4      .1       0  5000.5     .07       0
  5006.5      .1       0
Bank Sta=5000.5,5006.5
XS Rating Curve= 0 ,0
Exp/Cntr=0.3,0.1

Type RM Length L Ch R = 1 ,2575    ,757,757,757
BEGIN DESCRIPTION:
UNT 1033 IN LATR 4.0
END DESCRIPTION:
XS GIS Cut Line= 3
      2920950.97     10026975.91      2921924.97     10026955.08
      2922398.92     10026569.67
#Sta/Elev= 30
  4511.2 1384.06  4588.7 1378.42  4674.1 1364.53  4698.7 1357.98  4748.7 1334.63
  4768.8 1328.88  4838.8 1322.84  4898.8 1314.58  4918.8 1298.04  4995.8 1256.63
  4998.6 1256.13  5001.8 1256.63  5036.8 1264.44  5138.8 1264.13  5248.9 1267.86
  5278.9 1273.62  5314.2 1287.68  5368.9 1301.59  5484.7 1312.23    5530 1313.68
  5716.4 1323.28  5823.5 1332.62  5858.6 1337.76    5929 1357.62  5965.7 1361.71
  5972.1 1364.79  5986.5 1363.69  5992.9 1366.86  6050.4 1369.11  6096.3 1363.99
#Mann= 6 ,-1 , 0
  4511.2     .16       0  4674.1      .1       0  4995.8     .07       0
  5001.8      .1       0  5036.8     .16       0    5530      .1       0
Bank Sta=4995.8,5001.8
XS Rating Curve= 0 ,0
Exp/Cntr=0.3,0.1

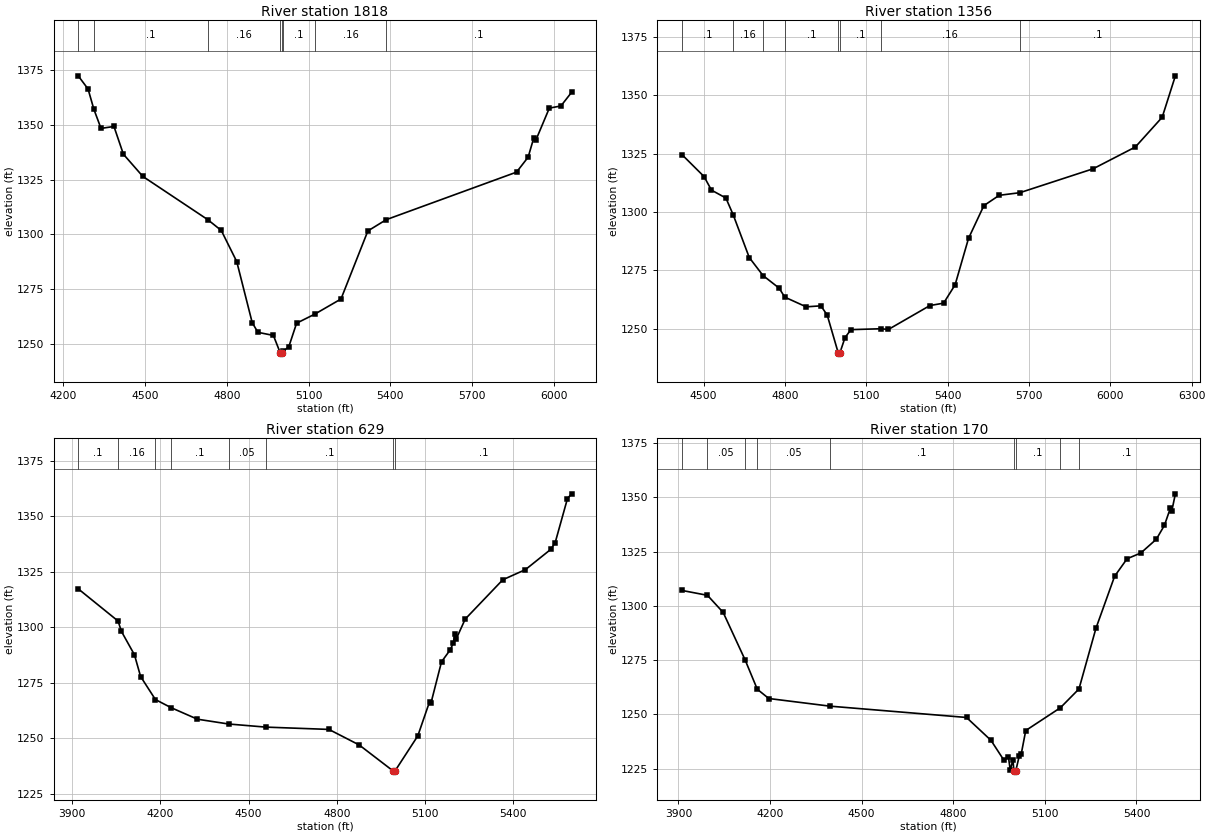
Type RM Length L Ch R = 1 ,1818    ,1365,1365,1365
BEGIN DESCRIPTION:
UNT 1033 IN LATR 3.0
END DESCRIPTION:
XS GIS Cut Line= 3
      2920945.84     10027116.55      2921404.14     10027309.25
      2922289.57     10028278.02
#Sta/Elev= 30
  4255.1 1372.37  4291.2 1366.36  4312.6 1357.09  4338.7 1348.37  4386.2 1349.27
  4420.8  1336.6  4492.1 1326.47  4730.4 1306.72  4779.8 1301.81  4836.5 1287.62
  4893.3 1259.73  4914.2 1255.32    4971  1253.9  4996.3 1245.87  4999.1 1245.37
  5002.3 1245.87    5008 1246.74  5027.7 1248.81  5056.1 1259.49  5123.4 1263.66
  5218.9 1270.53  5317.5 1301.59  5384.9 1306.73  5862.7 1328.42  5905.3 1335.25
  5926.2 1344.15  5933.6 1343.01    5983 1357.63  6025.5 1358.62  6064.7 1364.85
#Mann= 8 ,-1 , 0
  4255.1     .16       0  4312.6      .1       0  4730.4     .16       0
  4996.3     .07       0  5002.3     .16       0    5008      .1       0
  5123.4     .16       0  5384.9      .1       0
Bank Sta=4996.3,5002.3
XS Rating Curve= 0 ,0
Exp/Cntr=0.3,0.1

Type RM Length L Ch R = 1 ,1356    ,727,727,727
BEGIN DESCRIPTION:
Mapping XS 1c7d6d08
END DESCRIPTION:
XS GIS Cut Line= 4
      2920949.99     10027443.22      2921179.15     10027841.65
      2921595.82     10027656.75      2922233.69     10028297.22
#Sta/Elev= 30
  4420.6 1324.53  4501.9 1315.16  4529.3 1309.34  4582.5 1305.97  4609.8 1298.68
  4668.7 1280.49  4719.5 1272.79  4778.8 1267.41  4799.5 1263.57  4878.5 1259.41
  4932.7 1259.83    4956 1255.92  4996.8 1239.67  4999.6 1239.17  5002.8 1239.67
  5021.7 1246.23  5043.6 1249.65  5153.4 1250.03  5181.8 1249.73  5334.8 1259.96
  5385.3 1260.98  5427.7 1268.83  5477.2 1288.71  5533.8 1302.72  5590.4 1307.13
  5666.5 1308.25  5936.9 1318.49  6092.4  1327.8  6191.4 1340.54    6240 1358.26
#Mann= 8 ,-1 , 0
  4420.6      .1       0  4609.8     .16       0  4719.5     .05       0
  4799.5      .1       0  4996.8     .07       0  5002.8      .1       0
  5153.4     .16       0  5666.5      .1       0
Bank Sta=4996.8,5002.8
XS Rating Curve= 0 ,0
Exp/Cntr=0.3,0.1

Type RM Length L Ch R = 1 ,629     ,459,459,459
BEGIN DESCRIPTION:
Mapping XS 1c7d6d08
END DESCRIPTION:
XS GIS Cut Line= 4
      2920911.69     10027554.34      2921343.96     10028163.68
      2922065.31     10028252.22      2922182.44     10028418.81
#Sta/Elev= 30
  3920.9 1317.28  4056.4 1302.77  4067.8 1298.12  4112.1 1287.58    4133  1277.8
  4183.4 1267.43  4236.6 1263.78  4326.2 1258.58  4432.1 1256.42  4558.3 1255.02
  4773.3 1253.98  4876.3 1246.98  4991.9 1235.25  4994.7 1234.75  4997.9 1235.25
  5075.5 1251.07  5115.3 1266.37  5120.4 1265.91  5156.1 1284.42  5186.4 1289.93
  5196.4 1292.96  5201.7 1296.89  5206.7 1294.88  5236.7 1303.66  5364.4 1321.35
  5441.5 1325.93  5527.8 1335.07  5542.6 1338.09  5584.4 1357.94  5598.4 1360.05
#Mann= 8 ,-1 , 0
  3920.9      .1       0  4056.4     .16       0  4183.4     .05       0
  4236.6      .1       0  4432.1     .05       0  4558.3      .1       0
  4991.9     .07       0  4997.9      .1       0
Bank Sta=4991.9,4997.9
XS Rating Curve= 0 ,0
Exp/Cntr=0.3,0.1

Type RM Length L Ch R = 1 ,170     ,0,0,0
BEGIN DESCRIPTION:
UNT 1033 IN LATR 1.0
END DESCRIPTION:
XS GIS Cut Line= 4
      2920854.36     10027791.27      2921341.35     10028497.01
      2921661.66     10028718.37      2922023.58     10028791.27
#Sta/Elev= 30
  3911.5 1307.08  3994.9 1304.84  4046.4 1296.95  4118.1 1275.14  4158.1  1261.6
  4195.8 1257.33  4396.2 1253.81  4843.4  1248.6  4923.5 1238.08  4965.7 1228.96
  4980.6 1230.54  4986.7 1224.39  4995.5 1229.14  4998.6 1223.94  5001.3 1223.44
  5004.6 1223.94  5016.4 1231.05  5022.5 1231.73  5037.4 1242.59  5150.8 1253.07
  5211.7 1261.73  5267.3 1289.65  5328.5 1313.62  5369.3 1321.67  5414.3 1324.32
  5465.1 1330.65  5491.7 1337.08  5510.8 1344.86  5515.9 1343.77  5527.5 1351.56
#Mann= 9 ,-1 , 0
  3911.5     .16       0  3994.9     .05       0  4118.1      .1       0
  4158.1     .05       0  4396.2      .1       0  4998.6     .07       0
  5004.6      .1       0  5150.8     .16       0  5211.7      .1       0
Bank Sta=4998.6,5004.6
XS Rating Curve= 0 ,0
Exp/Cntr=0.3,0.1

Chan Stop Cuts=-1
Use User Specified Reach Order=0
Composite Channel Slope=5