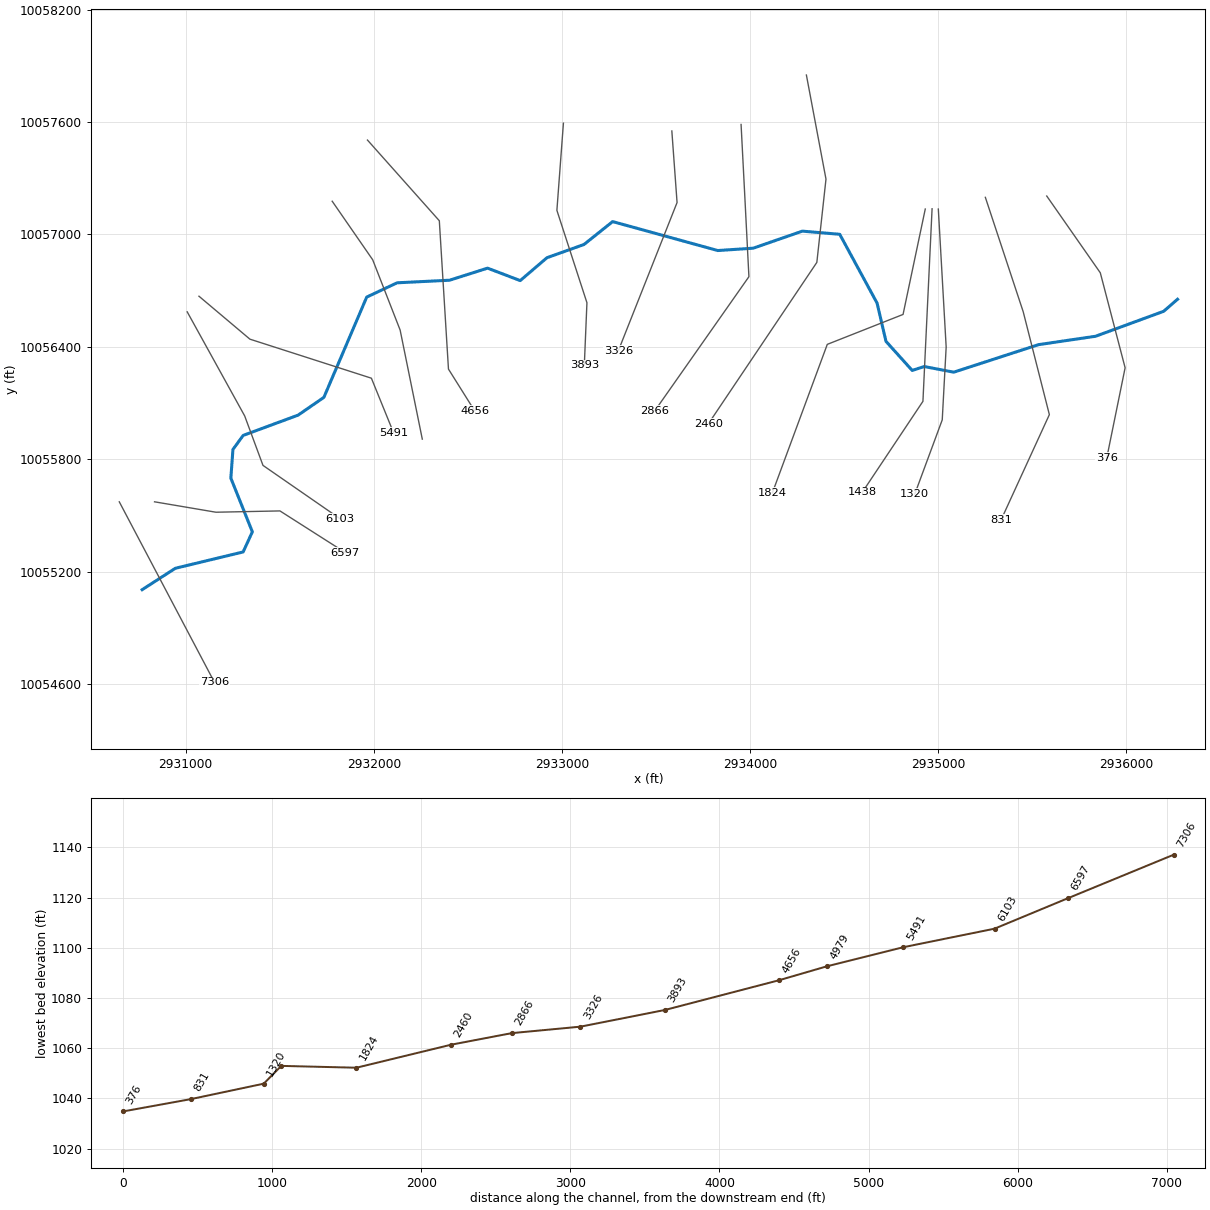
--- UNT 1038 IN LATR.prj (project) ---

Proj Title=UNT 1038 IN LATR Base Level Engineering
Current Plan=p01
Default Exp/Contr=0.3,0.1
English Units
Geom File=g01
Flow File=f01
Plan File=p01
Y Axis Title=Elevation
X Axis Title(PF)=Main Channel Distance
X Axis Title(XS)=Station
BEGIN DESCRIPTION:
UNT 1038 IN LATR
END DESCRIPTION:
DSS Export Rating Curves= 0
DSS Export Rating Curve Sorted= 0
DSS Export Volume Flow Curves= 0
DXF OffsetX= 0
DXF OffsetY= 0
DXF ScaleX= 1
DXF ScaleY= 10

--- UNT 1038 IN LATR.p01 (plan) ---

Plan Title=Multiple Run
Short Identifier=Multiple
Geom File=g01
Flow File=f01
Subcritical Flow
K Sum by GR= 0
Std Step Tol= 0.01
Critical Tol= 0.01
Num of Std Step Trials= 20
Max Error Tol= 0.3
Flow Tol Ratio= 0.001
Split Flow NTrial= 30
Split Flow Tol= 0.02
Split Flow Ratio= 0.02
Log Output Level= 0
Friction Slope Method= 1
Unsteady Friction Slope Method= 2
Unsteady Bridges Friction Slope Method= 1
Parabolic Critical Depth
Global Vel Dist=  1 , 1 , 1
Global Log Level= 0
CheckData=True
Encroach Param= -1, 0, 0, 0
BEGIN DESCRIPTION:
Multiple Run
END DESCRIPTION:

--- UNT 1038 IN LATR.f01 (steady flow) ---

Flow Title=Multiple
Number of Profiles=7
Profile Names=10-year,25-year,50-year,1pct_min,100-year,1pct_plu,500-year
River Rch & RM= UNT 1038 IN LATR,Reach-1,7306
     918    1336    1701    1587    2146    2902    3426
River Rch & RM= UNT 1038 IN LATR,Reach-1,6103
    1532    2284    2955    2795    3780    5113    6212
Boundary for River Rch & Prof#=UNT 1038 IN LATR,Reach-1,1
Up Type=0
Dn Type=3
Dn Slope=0.005
Boundary for River Rch & Prof#=UNT 1038 IN LATR,Reach-1,2
Up Type=0
Dn Type=3
Dn Slope=0.005
Boundary for River Rch & Prof#=UNT 1038 IN LATR,Reach-1,3
Up Type=0
Dn Type=3
Dn Slope=0.005
Boundary for River Rch & Prof#=UNT 1038 IN LATR,Reach-1,4
Up Type=0
Dn Type=3
Dn Slope=0.005
Boundary for River Rch & Prof#=UNT 1038 IN LATR,Reach-1,5
Up Type=0
Dn Type=3
Dn Slope=0.005
Boundary for River Rch & Prof#=UNT 1038 IN LATR,Reach-1,6
Up Type=0
Dn Type=3
Dn Slope=0.005
Boundary for River Rch & Prof#=UNT 1038 IN LATR,Reach-1,7
Up Type=0
Dn Type=3
Dn Slope=0.005

--- UNT 1038 IN LATR.g01 (geometry) ---

Geom Title=Existing Conditions
Program Version=4.10

River Reach=UNT 1038 IN LATR,Reach-1
Reach XY= 30
      2930768.84     10055104.11      2930945.35     10055218.23
      2931305.71     10055305.42      2931354.64     10055412.92
      2931240.28     10055699.31      2931251.44      10055852.5
      2931305.77     10055927.36      2931597.72     10056035.53
      2931734.89     10056130.36      2931962.58     10056665.66
      2932124.25     10056741.85       2932402.7     10056755.57
      2932605.17     10056820.03      2932778.65      10056753.6
      2932920.83     10056875.79      2933117.45     10056946.21
       2933270.1     10057068.51      2933828.68     10056914.05
      2934017.31     10056926.53      2934278.52     10057017.54
      2934477.27     10057000.64      2934675.83      10056633.3
      2934723.05     10056429.44      2934862.44      10056274.1
       2934926.4     10056294.95      2935083.22     10056264.82
      2935534.01     10056411.72      2935837.31     10056456.53
      2936199.42     10056589.78      2936273.12      10056654.1

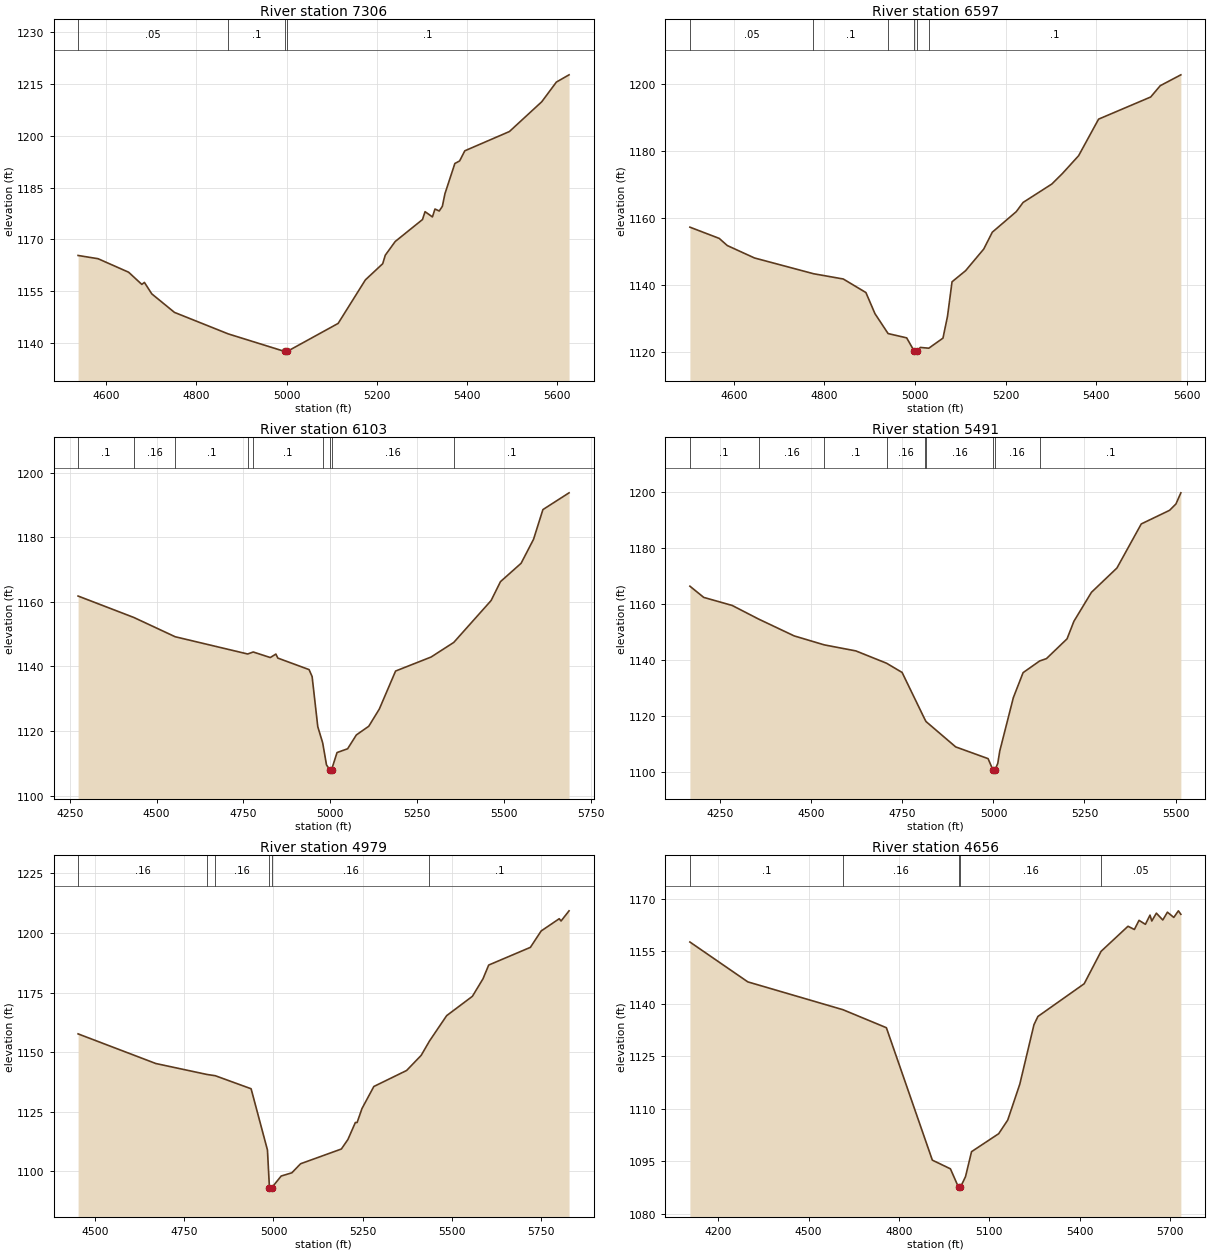
Type RM Length L Ch R = 1 ,7306    ,709,709,709
BEGIN DESCRIPTION:
UNT 1038 IN LATR 16.0
END DESCRIPTION:
XS GIS Cut Line= 2
      2930647.19     10055572.99      2931153.53     10054608.86
#Sta/Elev= 30
  4537.5 1165.35  4581.8 1164.41  4649.6  1160.5  4678.9 1156.97  4684.6 1157.55
    4701 1154.23  4751.3 1148.87  4870.5 1142.65  4995.4 1137.58  4998.1 1137.08
  5001.4 1137.58  5114.3 1145.68  5174.8 1158.29  5213.2 1162.97  5218.9 1165.43
  5240.9 1169.39  5301.4 1175.75  5307.1 1178.03  5323.5 1176.51  5329.1  1178.8
  5338.6 1178.22  5345.5 1179.58  5351.2 1183.22  5373.2 1191.97  5383.8 1192.72
  5395.3 1195.65  5494.2 1201.22    5566 1209.85  5598.4 1215.54  5626.5 1217.64
#Mann= 4 ,-1 , 0
  4537.5     .05       0  4870.5      .1       0  4995.4     .07       0
  5001.4      .1       0
Bank Sta=4995.4,5001.4
XS Rating Curve= 0 ,0
Exp/Cntr=0.3,0.1

Type RM Length L Ch R = 1 ,6597    ,494,494,494
BEGIN DESCRIPTION:
UNT 1038 IN LATR 15.0
END DESCRIPTION:
XS GIS Cut Line= 4
      2930834.66       10055573.      2931161.08     10055517.43
      2931501.36     10055524.38      2931848.57     10055302.16
#Sta/Elev= 30
  4503.3 1157.31    4568 1153.96  4585.8 1151.83    4646 1148.12  4776.1 1143.43
  4841.8 1141.86  4891.8 1137.82  4911.8 1131.52  4940.8 1125.59  4981.8 1124.31
  4998.8 1120.26  5001.6 1119.76  5004.8 1120.26  5011.8 1121.46  5030.6 1121.23
  5061.9 1124.23  5071.9 1130.73  5081.9 1141.02  5111.9 1144.34  5151.9 1150.79
  5170.8 1155.81  5223.6 1161.92  5238.8 1164.68  5302.2 1170.17  5325.7 1173.32
  5361.3 1178.61  5405.4 1189.51  5520.4 1196.11  5541.5 1199.48    5587 1202.72
#Mann= 6 ,-1 , 0
  4503.3     .05       0  4776.1      .1       0  4940.8     .16       0
  4998.8     .07       0  5004.8     .16       0  5030.6      .1       0
Bank Sta=4998.8,5004.8
XS Rating Curve= 0 ,0
Exp/Cntr=0.3,0.1

Type RM Length L Ch R = 1 ,6103    ,612,612,612
BEGIN DESCRIPTION:
UNT 1038 IN LATR 14.0
END DESCRIPTION:
XS GIS Cut Line= 4
      2931008.32     10056586.84      2931313.86     10056031.32
      2931411.08     10055767.43      2931820.83     10055482.69
#Sta/Elev= 30
  4273.9 1161.78  4434.4 1155.15  4553.5 1149.18  4762.4 1143.84  4778.4 1144.46
  4827.5 1142.74  4843.6 1143.81  4849.3 1142.57  4939.2 1139.01    4948 1136.86
  4964.3 1121.35  4978.5  1116.3  4989.4 1109.53  4998.2 1108.08    5001 1107.58
  5004.2 1108.08  5019.8 1113.33  5050.3  1114.5  5075.4 1118.78  5111.2 1121.47
  5141.6  1126.8  5188.4 1138.56  5290.7  1142.9    5356 1147.42  5463.6 1160.39
  5490.6 1166.24    5550 1171.92  5585.8 1179.35  5612.8 1188.54  5688.1 1193.73
#Mann= 9 ,-1 , 0
  4273.9      .1       0  4434.4     .16       0  4553.5      .1       0
  4762.4     .16       0  4778.4      .1       0  4978.5     .16       0
  4998.2     .07       0  5004.2     .16       0    5356      .1       0
Bank Sta=4998.2,5004.2
XS Rating Curve= 0 ,0
Exp/Cntr=0.3,0.1

Type RM Length L Ch R = 1 ,5491    ,512,512,512
BEGIN DESCRIPTION:
UNT 1038 IN LATR 13.0
END DESCRIPTION:
XS GIS Cut Line= 4
       2931070.8     10056670.22      2931341.64     10056441.04
      2931987.47     10056232.71      2932105.51     10055941.08
#Sta/Elev= 30
  4166.6 1166.38  4204.6 1162.37  4282.6 1159.49  4355.2 1154.62  4452.9 1148.59
  4535.5 1145.38  4622.3 1143.22  4706.4 1138.82  4749.2 1135.52  4811.5 1118.77
    4815 1117.93  4896.3 1108.87  4985.3 1104.67  4998.4  1100.7  5001.1  1100.2
  5004.4  1100.7  5011.9 1102.97  5017.3 1107.36  5054.6 1126.48  5081.4 1135.44
  5126.9 1139.62  5145.5 1140.46  5202.1 1147.54  5220.9 1153.81  5269.1 1164.19
  5339.1 1172.89  5405.9 1188.66  5483.6 1193.53    5501 1195.79  5514.6 1199.79
#Mann= 9 ,-1 , 0
  4166.6      .1       0  4355.2     .16       0  4535.5      .1       0
  4706.4     .16       0  4811.5      .1       0    4815     .16       0
  4998.4     .07       0  5004.4     .16       0  5126.9      .1       0
Bank Sta=4998.4,5004.4
XS Rating Curve= 0 ,0
Exp/Cntr=0.3,0.1

Type RM Length L Ch R = 1 ,4979    ,323,323,323
BEGIN DESCRIPTION:
UNT 1038 IN LATR 12.0
END DESCRIPTION:
XS GIS Cut Line= 4
      2931779.15     10057177.13      2931994.41     10056864.66
      2932140.25     10056489.66      2932258.05     10055907.56
#Sta/Elev= 30
  4452.6 1157.69  4670.5 1145.26  4813.8 1140.67    4837 1140.15  4937.4 1134.68
  4983.2 1109.01  4988.8  1093.1  4991.5  1092.6  4994.8  1093.1  5021.7 1098.09
  5051.6 1099.45  5076.1 1103.24  5190.3 1109.42  5208.6 1113.39  5229.5 1120.52
  5234.4 1120.52  5248.1 1126.39  5281.3 1135.63  5373.1 1142.34  5413.9 1148.67
  5437.2 1154.69  5485.3 1165.33  5557.5 1173.44  5587.3 1180.82  5603.1 1186.54
    5720 1193.97  5750.1 1200.83  5800.8 1205.97  5805.9 1205.01  5828.3 1209.28
#Mann= 6 ,-1 , 0
  4452.6     .16       0  4813.8      .1       0    4837     .16       0
  4988.8     .07       0  4994.8     .16       0  5437.2      .1       0
Bank Sta=4988.8,4994.8
XS Rating Curve= 0 ,0
Exp/Cntr=0.3,0.1

Type RM Length L Ch R = 1 ,4656    ,763,763,763
BEGIN DESCRIPTION:
UNT 1038 IN LATR 11.0
END DESCRIPTION:
XS GIS Cut Line= 4
      2931966.62     10057503.57      2932348.58     10057072.99
      2932397.19     10056281.32      2932536.08     10056059.09
#Sta/Elev= 30
  4105.9 1157.62  4298.3 1146.23  4614.3 1138.28  4758.5 1133.14  4911.2  1095.3
  4971.3 1092.82  4998.3 1087.52  5001.1 1087.02  5004.3 1087.52  5021.4 1090.59
  5041.4 1097.72  5131.6 1102.86  5161.6 1106.75  5201.7 1117.01  5248.7 1133.98
  5261.8 1136.35  5415.5 1145.69  5471.7 1154.96  5561.1 1162.12  5582.3  1161.2
  5597.7 1163.81  5618.9 1162.67  5634.2  1165.3  5640.1 1163.62  5655.4 1165.86
  5676.7 1163.91    5692 1166.14  5713.2 1164.65  5728.5 1166.53  5736.7 1165.54
#Mann= 5 ,-1 , 0
  4105.9      .1       0  4614.3     .16       0  4998.3     .07       0
  5004.3     .16       0  5471.7     .05       0
Bank Sta=4998.3,5004.3
XS Rating Curve= 0 ,0
Exp/Cntr=0.3,0.1

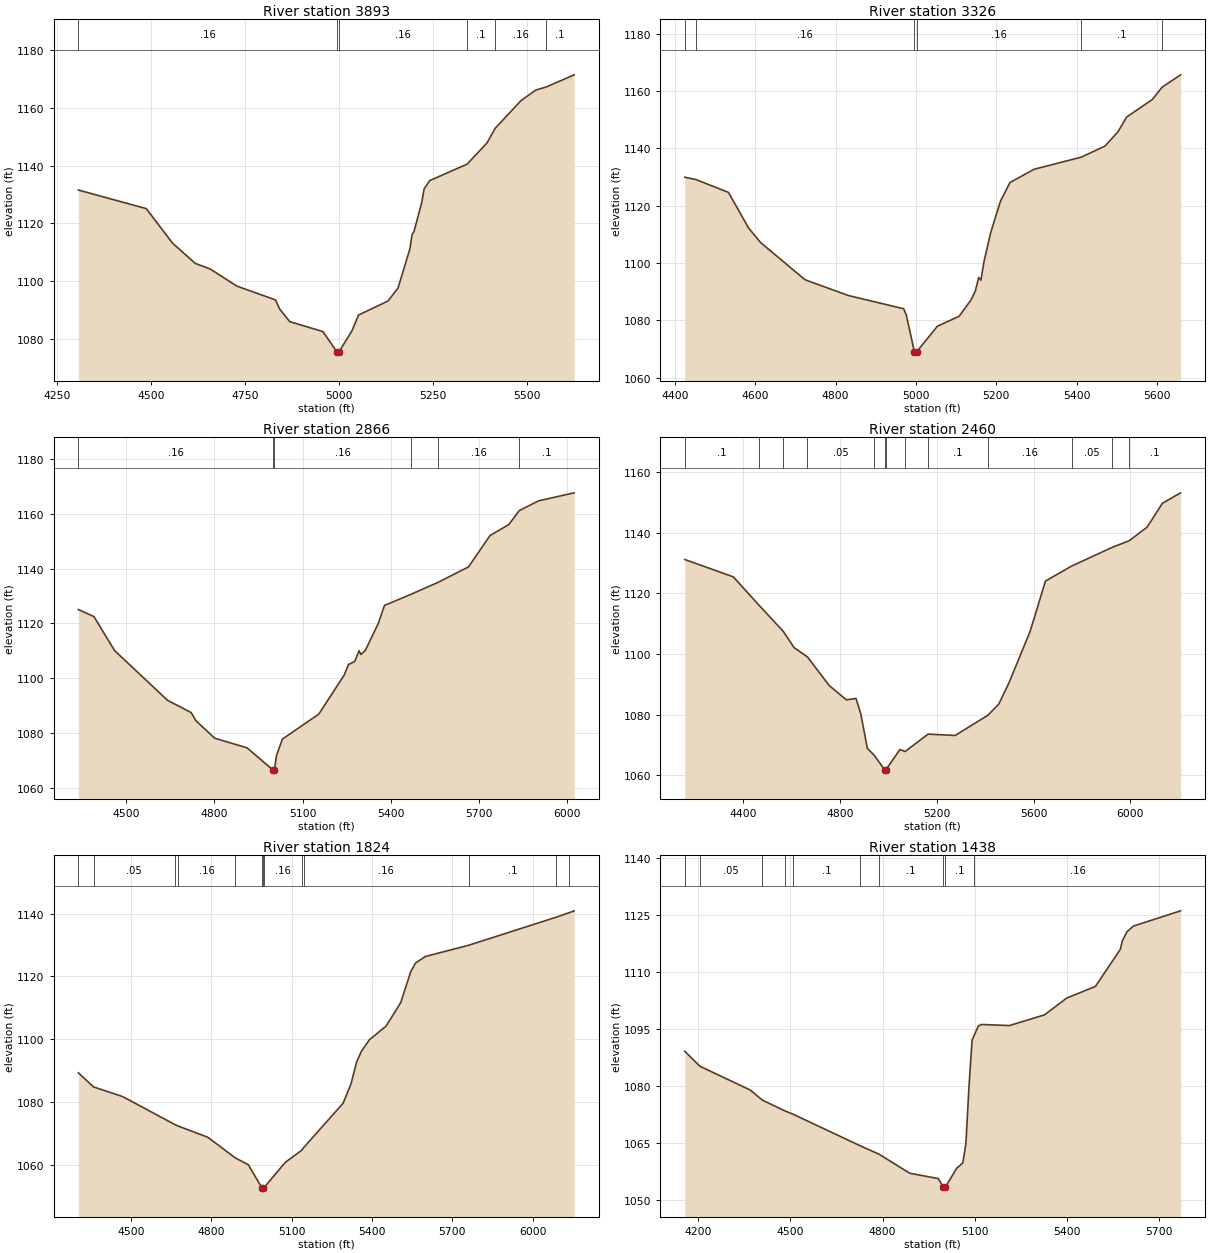
Type RM Length L Ch R = 1 ,3893    ,567,567,567
BEGIN DESCRIPTION:
UNT 1038 IN LATR 9.0
END DESCRIPTION:
XS GIS Cut Line= 4
      2933008.31     10057593.85      2932973.58     10057128.54
       2933133.3     10056635.49      2933119.41     10056302.16
#Sta/Elev= 30
  4306.9 1131.56  4487.5 1125.14  4557.7 1113.17  4617.9 1106.21    4658 1104.25
  4728.2 1098.38  4831.1  1093.6  4842.5 1090.42  4869.2 1086.08  4957.3 1082.66
  4994.2 1075.71  4996.9 1075.21  5000.2 1075.71  5034.4 1082.87  5051.9 1088.37
  5130.4 1093.21    5157 1097.69  5188.5 1111.17  5194.4 1116.18  5199.6 1117.24
    5220 1127.18  5226.4 1131.95  5241.1 1134.81  5340.8 1140.51  5393.6 1147.83
  5415.4 1152.88  5483.7 1162.41  5523.4 1166.11  5550.4 1167.12  5625.4 1171.36
#Mann= 6 ,-1 , 0
  4306.9     .16       0  4994.2     .07       0  5000.2     .16       0
  5340.8      .1       0  5415.4     .16       0  5550.4      .1       0
Bank Sta=4994.2,5000.2
XS Rating Curve= 0 ,0
Exp/Cntr=0.3,0.1

Type RM Length L Ch R = 1 ,3326    ,460,460,460
BEGIN DESCRIPTION:
UNT 1038 IN LATR 8.0
END DESCRIPTION:
XS GIS Cut Line= 3
      2933584.69     10057552.13      2933612.47     10057170.21
      2933300.02     10056378.68
#Sta/Elev= 30
  4424.9  1129.9  4452.3  1129.1  4533.6 1124.61  4583.7 1112.18  4613.8 1107.09
  4724.1 1094.15  4831.6 1088.66  4969.6 1084.04  4976.1 1081.86  4996.3 1069.06
  4999.1 1068.56  5002.3 1069.06  5053.5 1077.95  5107.6 1081.41  5137.3 1087.12
  5148.1 1090.31  5156.3 1094.94  5161.7 1093.99  5169.6 1100.54  5186.1 1110.57
  5210.4 1121.53  5234.1 1128.05  5294.3 1132.69  5411.3 1136.88  5470.6 1140.77
  5502.9 1145.74  5524.4 1150.88  5588.9 1157.07  5612.6 1161.29  5658.8 1165.61
#Mann= 6 ,-1 , 0
  4424.9      .1       0  4452.3     .16       0  4996.3     .07       0
  5002.3     .16       0  5411.3      .1       0  5612.6     .16       0
Bank Sta=4996.3,5002.3
XS Rating Curve= 0 ,0
Exp/Cntr=0.3,0.1

Type RM Length L Ch R = 1 ,2866    ,406,406,406
BEGIN DESCRIPTION:
UNT 1038 IN LATR 7.0
END DESCRIPTION:
XS GIS Cut Line= 4
      2933952.75     10057586.86      2933973.58      10057184.1
      2933994.41     10056774.38      2933494.39     10056059.06
#Sta/Elev= 30
  4337.6  1125.1  4390.8  1122.5  4460.9 1110.08  4641.1 1091.88  4721.2 1087.43
  4737.5 1084.44  4801.3 1078.03  4911.5 1074.51  4998.6 1066.49  5001.3 1065.99
  5004.6 1066.49  5011.6 1071.68  5031.6  1077.7  5155.4 1086.84  5241.8 1101.12
  5256.6 1105.01  5277.5 1106.05  5292.3 1110.04  5298.4 1108.64  5313.3 1110.08
  5357.8    1120  5378.7 1126.57  5467.8 1130.61  5559.4 1134.95  5664.7 1140.69
  5737.6 1152.14  5801.6 1156.16  5837.5 1161.29  5902.8 1164.84  6023.9 1167.77
#Mann= 6 ,-1 , 0
  4337.6     .16       0  4998.6     .07       0  5004.6     .16       0
  5467.8     .05       0  5559.4     .16       0  5837.5      .1       0
Bank Sta=4998.6,5004.6
XS Rating Curve= 0 ,0
Exp/Cntr=0.3,0.1

Type RM Length L Ch R = 1 ,2460    ,636,636,636
BEGIN DESCRIPTION:
UNT 1038 IN LATR 6.0
END DESCRIPTION:
XS GIS Cut Line= 4
      2934299.98     10057850.73      2934404.14     10057295.21
      2934355.53     10056850.77      2933779.14     10055989.66
#Sta/Elev= 30
  4158.7 1131.17  4359.1 1125.45    4467 1115.96  4566.3 1107.41  4610.1 1102.13
  4665.6 1099.04  4755.6 1089.59  4826.5 1084.89  4866.2 1085.36  4886.3 1080.15
  4912.8 1068.92  4940.9 1066.66  4983.9 1061.89  4986.7 1061.39  4989.9 1061.89
  5047.3  1068.5  5069.1 1067.87  5163.8 1073.59  5275.7 1073.15  5411.2 1079.83
  5456.2 1083.54  5498.3 1090.57  5585.4 1107.46  5648.8 1124.07  5757.4 1129.03
  5923.8 1135.16  5994.6 1137.36  6068.8 1141.85  6131.8 1149.71  6207.2 1153.16
#Mann= 13 ,-1 , 0
  4158.7      .1       0    4467     .05       0  4566.3      .1       0
  4665.6     .05       0  4940.9      .1       0  4983.9     .07       0
  4989.9      .1       0  5069.1     .16       0  5163.8      .1       0
  5411.2     .16       0  5757.4     .05       0  5923.8     .16       0
  5994.6      .1       0
Bank Sta=4983.9,4989.9
XS Rating Curve= 0 ,0
Exp/Cntr=0.3,0.1

Type RM Length L Ch R = 1 ,1824    ,504,504,504
BEGIN DESCRIPTION:
UNT 1038 IN LATR 4.0
END DESCRIPTION:
XS GIS Cut Line= 4
      2934931.92      10057135.5      2934813.86     10056572.99
      2934411.08     10056413.27      2934119.43     10055621.64
#Sta/Elev= 30
    4303  1089.3  4359.9 1084.79  4468.3 1081.72  4664.1 1072.76  4673.6 1072.39
  4786.2 1068.76  4889.7 1062.14  4937.4 1060.02  4988.1 1052.71  4990.9 1052.21
  4994.1 1052.71  4997.1 1052.73  5075.5 1060.72  5137.5 1064.63  5144.5 1065.46
  5291.6 1079.56  5321.2 1085.75  5342.5 1092.77  5360.3 1096.17  5390.7 1099.87
  5451.6 1104.12  5491.7 1109.54  5507.2 1111.73    5545 1121.66  5562.8 1124.31
  5598.5 1126.35  5761.3 1129.96  6087.7 1138.89  6133.6 1140.25  6154.7 1140.92
#Mann= 13 ,-1 , 0
    4303     .16       0  4359.9     .05       0  4664.1      .1       0
  4673.6     .16       0  4889.7      .1       0  4988.1     .07       0
  4994.1      .1       0  4997.1     .16       0  5137.5      .1       0
  5144.5     .16       0  5761.3      .1       0  6087.7     .05       0
  6133.6      .1       0
Bank Sta=4988.1,4994.1
XS Rating Curve= 0 ,0
Exp/Cntr=0.3,0.1

Type RM Length L Ch R = 1 ,1438    ,118,118,118
BEGIN DESCRIPTION:
Mapping XS 3bd47895
END DESCRIPTION:
XS GIS Cut Line= 3
      2934968.15     10057136.96      2934919.54     10056109.22
      2934596.61     10055623.09
#Sta/Elev= 30
  4156.9 1089.23  4206.1 1085.29  4370.4    1079  4409.5 1076.36    4482 1073.56
  4508.1  1072.7    4727 1064.36  4788.4 1062.15  4888.5 1057.12    4981 1055.73
  4998.1 1053.44  5000.8 1052.94  5004.1 1053.44  5041.1 1058.42  5061.1 1059.86
  5071.1 1064.93  5081.2 1080.06  5091.2 1092.17  5098.1 1093.46  5111.2 1095.83
  5121.2 1096.29  5212.6    1096  5326.9 1098.83    5399 1103.24  5492.5 1106.32
  5573.4 1116.09  5579.4 1118.19  5594.5 1120.65  5615.5 1122.19  5769.4 1126.21
#Mann= 10 ,-1 , 0
  4156.9      .1       0  4206.1     .05       0  4409.5     .16       0
    4482     .05       0  4508.1      .1       0    4727     .16       0
  4788.4      .1       0  4998.1     .07       0  5004.1      .1       0
  5098.1     .16       0
Bank Sta=4998.1,5004.1
XS Rating Curve= 0 ,0
Exp/Cntr=0.3,0.1

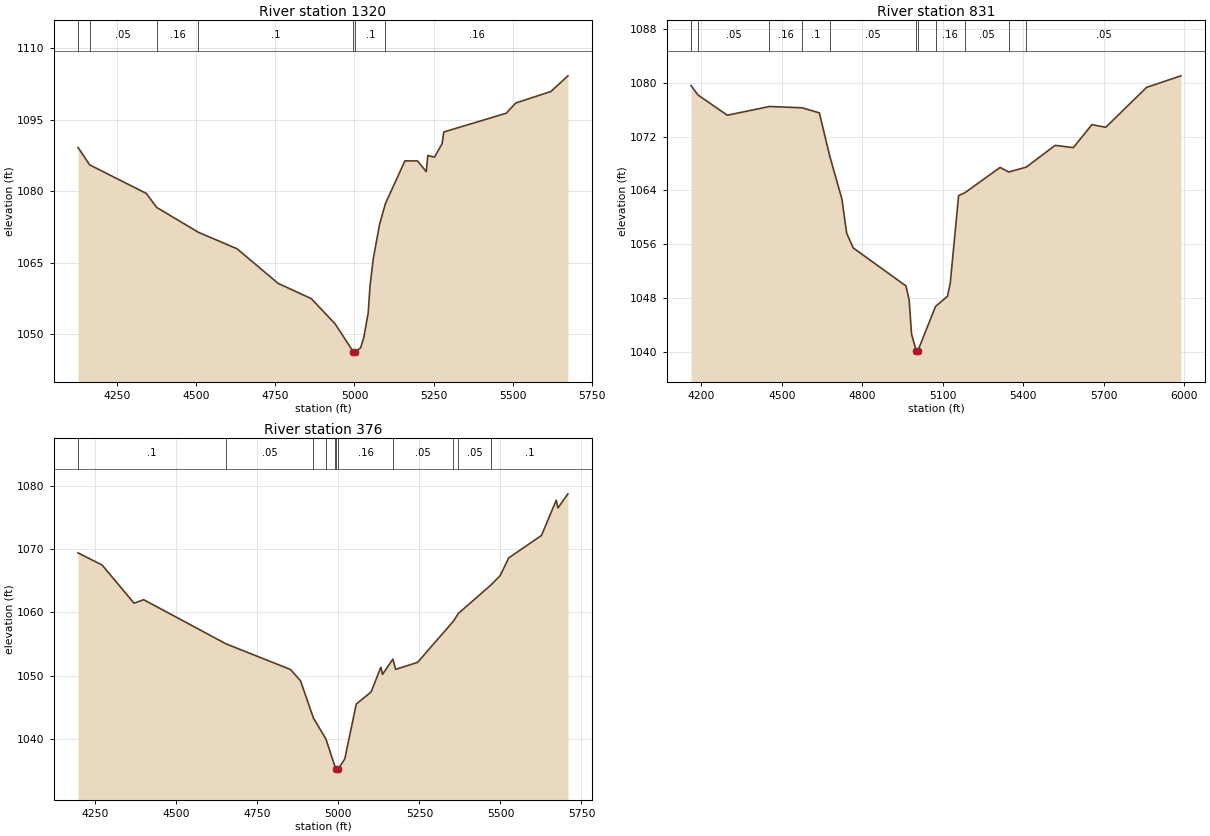
Type RM Length L Ch R = 1 ,1320    ,489,489,489
BEGIN DESCRIPTION:
UNT 1038 IN LATR 3.0
END DESCRIPTION:
XS GIS Cut Line= 4
      2935001.36     10057135.49      2935043.03     10056399.38
      2935022.19     10056010.49      2934876.35     10055614.63
#Sta/Elev= 30
  4126.1 1089.17  4162.9 1085.53  4341.8 1079.54  4374.8  1076.6  4506.6 1071.39
  4628.7 1067.94  4758.9 1060.67  4863.4 1057.49  4939.1 1052.17  4996.2 1046.35
    4999 1045.85  5002.2 1046.35  5019.3 1047.16  5029.3  1049.3  5043.2  1054.4
  5049.3 1060.24  5059.3 1065.82  5079.3 1073.02  5097.6 1077.37  5159.5 1086.37
  5199.5 1086.34  5226.8  1084.1  5231.8 1087.49  5252.8 1087.14    5277 1089.97
  5282.4 1092.42  5479.5 1096.34    5510  1098.5  5621.1 1100.91  5674.7 1104.19
#Mann= 7 ,-1 , 0
  4126.1      .1       0  4162.9     .05       0  4374.8     .16       0
  4506.6      .1       0  4996.2     .07       0  5002.2      .1       0
  5097.6     .16       0
Bank Sta=4996.2,5002.2
XS Rating Curve= 0 ,0
Exp/Cntr=0.3,0.1

Type RM Length L Ch R = 1 ,831     ,455,455,455
BEGIN DESCRIPTION:
UNT 1038 IN LATR 2.0
END DESCRIPTION:
XS GIS Cut Line= 4
      2935251.37     10057197.96      2935452.75     10056586.88
      2935591.64     10056038.27      2935335.37     10055477.25
#Sta/Elev= 30
  4161.1 1079.56  4187.2 1078.17  4296.4 1075.17  4453.4 1076.47  4575.5 1076.27
  4639.4 1075.52  4677.7 1069.17  4723.6 1062.71  4741.1 1057.67  4765.7 1055.47
  4962.5 1049.82  4974.2 1047.71  4983.1 1042.67  5000.7  1040.2  5003.5  1039.7
  5006.7  1040.2  5072.4 1046.77  5117.2  1048.3  5127.5 1050.29  5158.5 1063.24
  5181.8 1063.66  5313.2 1067.42  5345.3 1066.74    5411 1067.47  5518.3  1070.7
  5586.2 1070.36  5655.3 1073.77  5706.9 1073.38  5859.1  1079.3  5987.2 1081.02
#Mann= 11 ,-1 , 0
  4161.1      .1       0  4187.2     .05       0  4453.4     .16       0
  4575.5      .1       0  4677.7     .05       0  5000.7    .035       0
  5006.7     .05       0  5072.4     .16       0  5181.8     .05       0
  5345.3      .1       0    5411     .05       0
Bank Sta=5000.7,5006.7
XS Rating Curve= 0 ,0
Exp/Cntr=0.3,0.1

Type RM Length L Ch R = 1 ,376     ,0,0,0
BEGIN DESCRIPTION:
UNT 1038 IN LATR 1.0
END DESCRIPTION:
XS GIS Cut Line= 4
      2935577.73     10057204.96      2935862.47     10056795.21
      2935994.41     10056288.27       2935897.2     10055809.13
#Sta/Elev= 30
  4196.5 1069.39  4270.8 1067.47  4369.4 1061.45  4399.1    1062  4653.7 1055.02
    4852 1050.99    4883 1049.21  4922.8 1043.34  4961.4 1040.02    4988 1035.88
  4993.7 1035.29  4996.4 1034.79  4999.7 1035.29  5019.8  1036.9  5055.1 1045.53
  5100.8 1047.44    5131 1051.35  5136.1 1050.21  5167.9 1052.62  5176.7 1051.01
  5244.3 1052.11    5355 1058.62    5370 1059.82  5471.2 1064.35  5499.4 1065.82
  5525.4 1068.59  5626.7 1072.15  5672.2 1077.71  5677.3 1076.47  5708.2 1078.71
#Mann= 11 ,-1 , 0
  4196.5      .1       0  4653.7     .05       0  4922.8      .1       0
  4961.4     .05       0    4988     .16       0  4993.7     .07       0
  4999.7     .16       0  5167.9     .05       0    5355      .1       0
    5370     .05       0  5471.2      .1       0
Bank Sta=4993.7,4999.7
XS Rating Curve= 0 ,0
Exp/Cntr=0.3,0.1

Chan Stop Cuts=-1
Use User Specified Reach Order=0
Composite Channel Slope=5