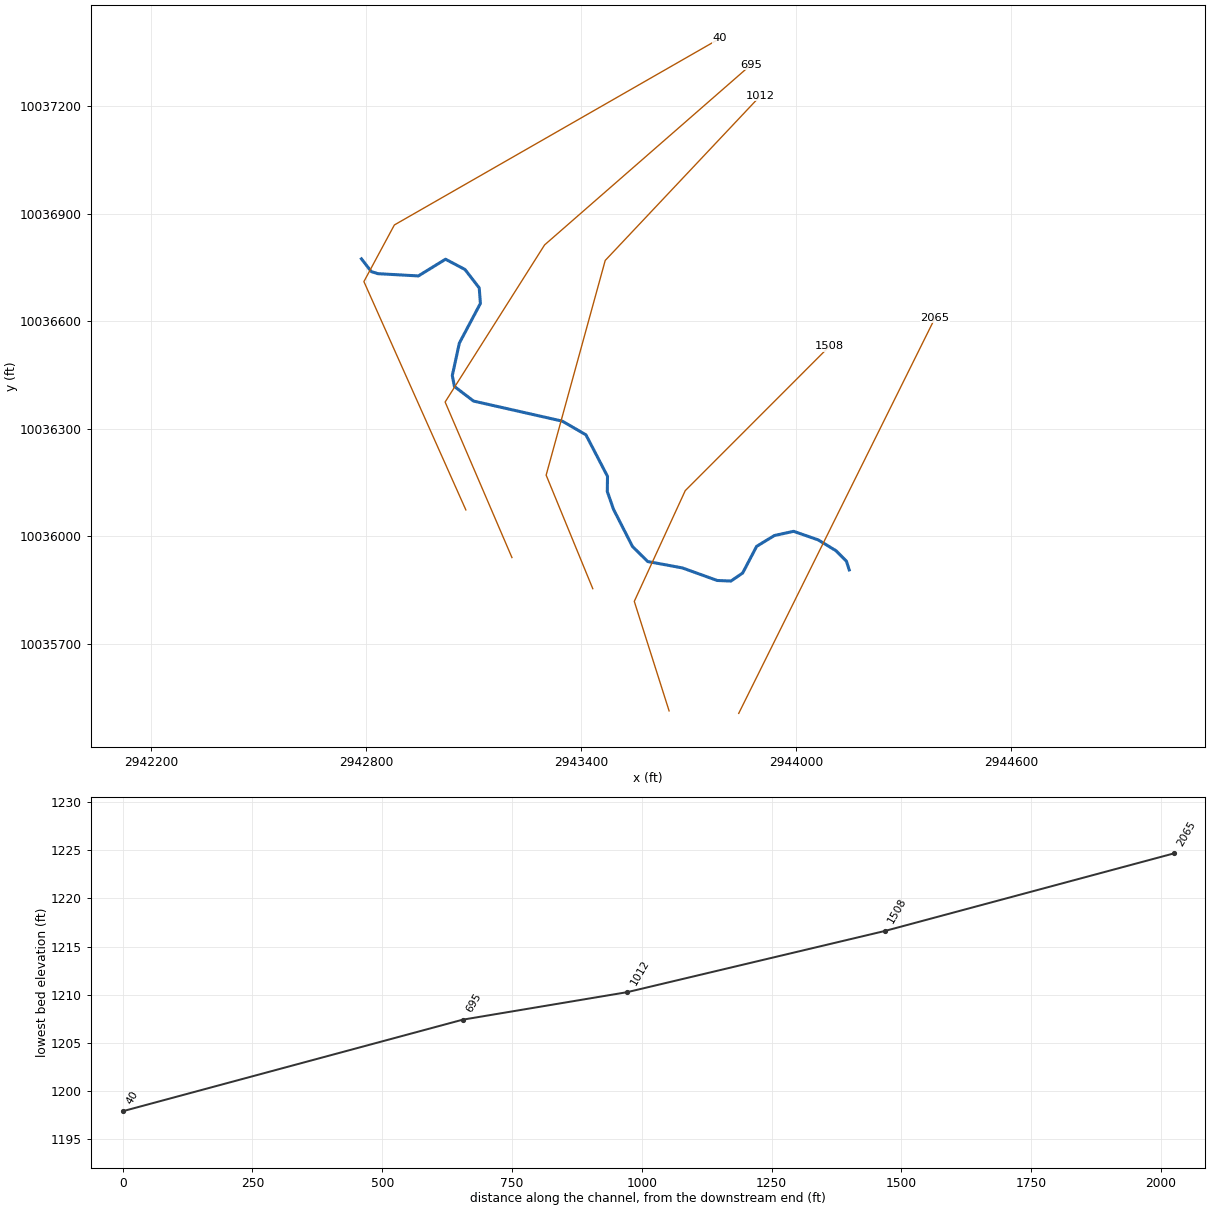
--- UNT 1040 IN LATR.prj (project) ---

Proj Title=UNT 1040 IN LATR Base Level Engineering
Current Plan=p01
Default Exp/Contr=0.3,0.1
English Units
Geom File=g01
Flow File=f01
Plan File=p01
BEGIN DESCRIPTION:
UNT 1040 IN LATR
END DESCRIPTION:

--- UNT 1040 IN LATR.p01 (plan) ---

Plan Title=Multiple Run
Short Identifier=Multiple
Geom File=g01
Flow File=f01
Subcritical Flow
K Sum by GR= 0
Std Step Tol= 0.01
Critical Tol= 0.01
Num of Std Step Trials= 20
Max Error Tol= 0.3
Flow Tol Ratio= 0.001
Split Flow NTrial= 30
Split Flow Tol= 0.02
Split Flow Ratio= 0.02
Log Output Level= 0
Friction Slope Method= 1
Unsteady Friction Slope Method= 2
Unsteady Bridges Friction Slope Method= 1
Parabolic Critical Depth
Global Vel Dist=  1 , 1 , 1
Global Log Level= 0
CheckData=True
Encroach Param= -1, 0, 0, 0
BEGIN DESCRIPTION:
Multiple Run
END DESCRIPTION:

--- UNT 1040 IN LATR.f01 (steady flow) ---

Flow Title=Multiple
Number of Profiles=7
Profile Names=10-year,25-year,50-year,1pct_min,100-year,1pct_plu,500-year
River Rch & RM= UNT 1040 IN LATR,Reach-1,2065
     924    1343    1708    1592    2153    2912    3431
Boundary for River Rch & Prof#=UNT 1040 IN LATR,Reach-1,1
Up Type=0
Dn Type=3
Dn Slope=0.005
Boundary for River Rch & Prof#=UNT 1040 IN LATR,Reach-1,2
Up Type=0
Dn Type=3
Dn Slope=0.005
Boundary for River Rch & Prof#=UNT 1040 IN LATR,Reach-1,3
Up Type=0
Dn Type=3
Dn Slope=0.005
Boundary for River Rch & Prof#=UNT 1040 IN LATR,Reach-1,4
Up Type=0
Dn Type=3
Dn Slope=0.005
Boundary for River Rch & Prof#=UNT 1040 IN LATR,Reach-1,5
Up Type=0
Dn Type=3
Dn Slope=0.005
Boundary for River Rch & Prof#=UNT 1040 IN LATR,Reach-1,6
Up Type=0
Dn Type=3
Dn Slope=0.005
Boundary for River Rch & Prof#=UNT 1040 IN LATR,Reach-1,7
Up Type=0
Dn Type=3
Dn Slope=0.005

--- UNT 1040 IN LATR.g01 (geometry) ---

Geom Title=Existing Conditions

River Reach=UNT 1040 IN LATR,Reach-1
Reach XY= 30
      2944148.46     10035905.60      2944140.61     10035930.05
      2944111.59     10035959.12      2944061.41     10035989.47
      2943993.21     10036013.26      2943939.43     10036001.47
      2943889.91     10035971.31      2943850.95     10035896.97
      2943818.17     10035874.50      2943779.87     10035876.07
      2943682.41     10035911.17      2943585.79     10035928.95
      2943543.29     10035970.83      2943490.27     10036074.57
      2943472.85     10036124.46      2943473.48     10036166.57
      2943413.25     10036282.48      2943347.25     10036320.67
      2943099.50     10036376.65      2943046.00     10036417.33
      2943040.03     10036447.81      2943059.69     10036538.27
      2943118.54     10036649.13      2943115.26     10036692.33
      2943075.54     10036743.80      2943021.19     10036772.47
      2942945.37     10036725.88      2942832.61     10036732.13
      2942813.78     10036737.98      2942786.38     10036773.53

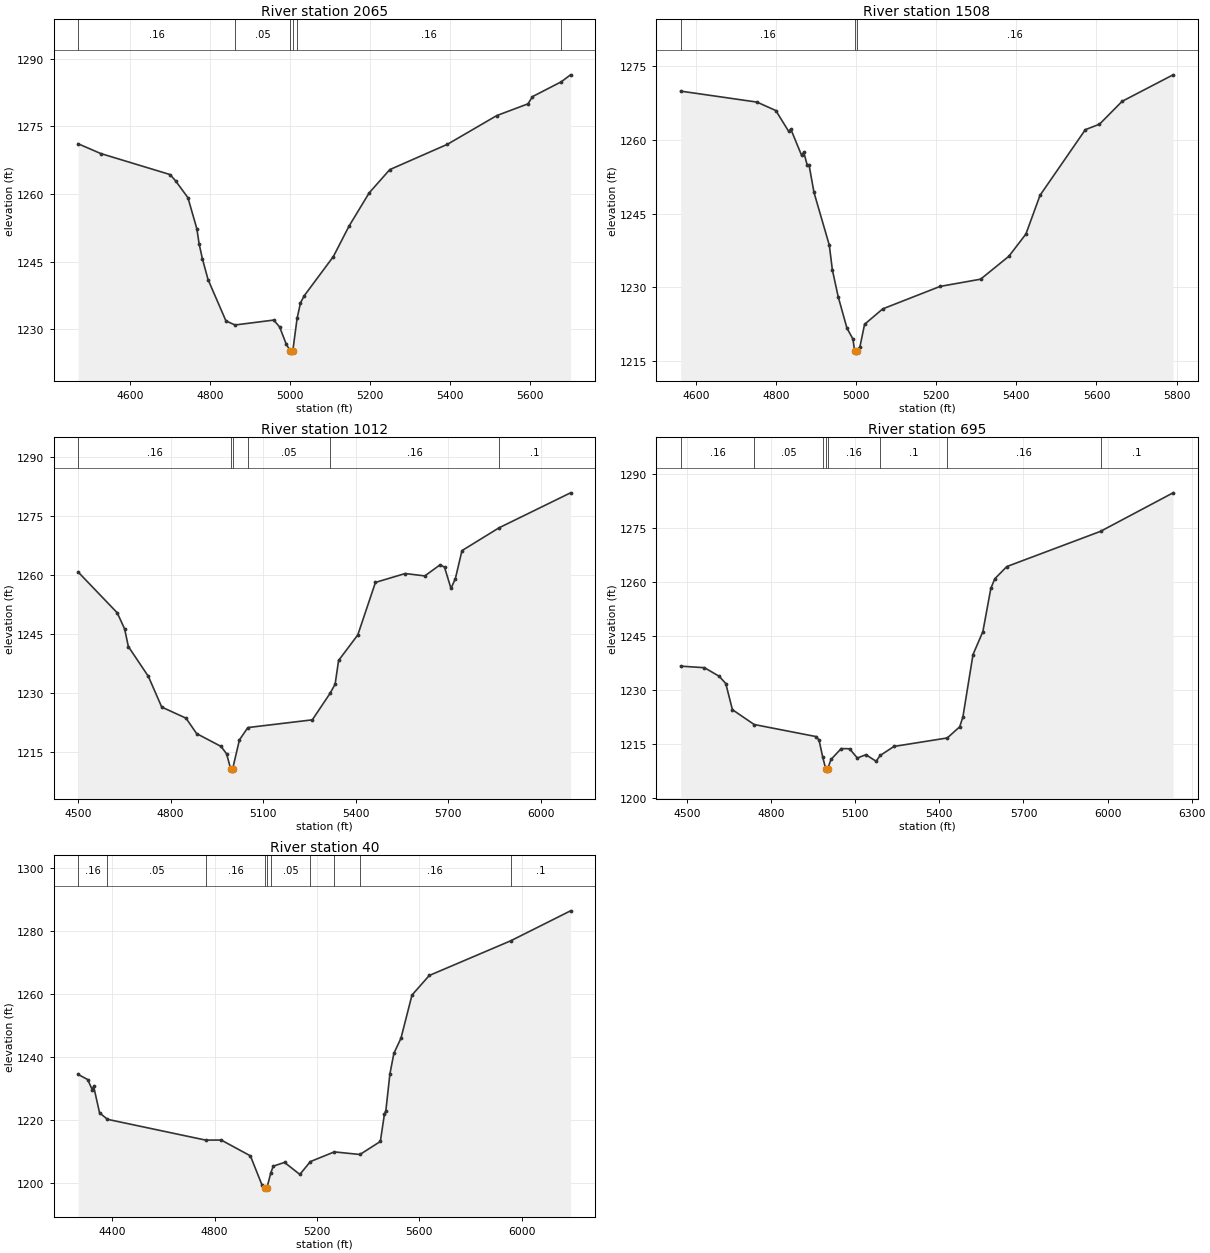
Type RM Length L Ch R = 1,2065,557,557,557
BEGIN DESCRIPTION:
UNT 1040 IN LATR 3.0
END DESCRIPTION:
XS GIS Cut Line= 2
      2943839.88     10035505.25      2944388.34     10036609.10
#Sta/Elev= 30
  4469.2 1271.15  4525.6 1268.99  4699.2 1264.32  4713.2 1262.91  4744.0 1259.18
  4766.4 1252.26  4772.0 1248.94  4780.2 1245.62  4794.4 1240.99  4839.2 1231.82
  4861.9 1230.92  4958.8 1232.01  4973.6 1230.47  4990.4 1226.60  5000.5 1225.17
  5003.2 1224.67  5006.5 1225.17  5017.3 1232.38  5025.8 1235.83  5035.3 1237.43
  5108.0 1246.10  5147.3 1252.87  5197.7 1260.25  5249.2 1265.41  5393.7 1271.04
  5517.1 1277.41  5595.3 1280.02  5606.5 1281.62  5678.5 1284.91  5701.8 1286.46
#Mann=6,-1,0
  4469.2    0.16       0  4861.9    0.05       0  5000.5   0.035       0
  5006.5    0.05       0  5017.3    0.16       0  5678.5     0.1       0
Bank Sta=5000.5,5006.5
Exp/Cntr=0.3,0.1

Type RM Length L Ch R = 1,1508,496,496,496
BEGIN DESCRIPTION:
UNT 1040 IN LATR 2.0
END DESCRIPTION:
XS GIS Cut Line= 4
      2943645.45     10035512.23      2943548.23     10035817.78
      2943690.59     10036126.81      2944092.95     10036529.16
#Sta/Elev= 30
  4561.5 1269.94  4752.0 1267.71  4799.1 1265.99  4831.3 1261.74  4836.5 1262.22
  4863.5 1256.86  4868.8 1257.52  4877.4 1254.92  4882.1 1254.92  4894.4 1249.33
  4932.7 1238.59  4940.3 1233.58  4954.8 1228.12  4976.8 1221.69  4991.8 1219.47
  4995.8 1217.11  4998.5 1216.61  5001.8 1217.11  5009.2 1217.90  5020.8 1222.48
  5066.2 1225.62  5209.4 1230.19  5310.6 1231.66  5381.3 1236.33  5423.8 1240.85
  5459.1 1248.74  5572.3 1262.10  5607.6 1263.21  5664.2 1267.87  5791.4 1273.26
#Mann=3,-1,0
  4561.5    0.16       0  4995.8    0.07       0  5001.8    0.16       0
Bank Sta=4995.8,5001.8
Exp/Cntr=0.3,0.1

Type RM Length L Ch R = 1,1012,317,317,317
BEGIN DESCRIPTION:
Mapping XS 787011c2
END DESCRIPTION:
XS GIS Cut Line= 4
      2943432.32     10035853.20      2943302.11     10036170.05
      2943467.04     10036769.01      2943900.92     10037228.93
#Sta/Elev= 30
  4500.6 1260.80  4627.3 1250.45  4651.3 1246.34  4663.3 1241.89  4728.2 1234.31
  4771.5 1226.52  4850.2 1223.71  4884.6 1219.79  4963.8 1216.53  4981.8 1214.64
  4995.2 1210.76  4997.9 1210.26  5001.2 1210.76  5023.3 1218.18  5050.7 1221.32
  5259.7 1223.28  5317.2 1230.01  5333.6 1232.34  5344.8 1238.35  5407.1 1244.84
  5464.3 1258.17  5560.7 1260.42  5624.3 1259.82  5674.0 1262.64  5688.2 1262.04
  5709.2 1256.63  5723.4 1259.14  5744.8 1266.24  5865.0 1272.03  6096.7 1280.91
#Mann=6,-1,0
  4500.6    0.16       0  4995.2    0.07       0  5001.2    0.16       0
  5050.7    0.05       0  5317.2    0.16       0  5865.0     0.1       0
Bank Sta=4995.2,5001.2
Exp/Cntr=0.3,0.1

Type RM Length L Ch R = 1,695,655,655,655
BEGIN DESCRIPTION:
Mapping XS b29364db
END DESCRIPTION:
XS GIS Cut Line= 4
      2943206.60     10035940.06      2943019.99     10036374.05
      2943297.77     10036812.41      2943874.24     10037315.20
#Sta/Elev= 30
  4477.4 1236.54  4562.2 1236.11  4614.7 1233.73  4638.2 1231.71  4661.8 1224.46
  4739.4 1220.34  4961.7 1216.97  4971.1 1215.94  4983.9 1211.31  4995.2 1207.90
  4997.9 1207.40  5001.2 1207.90  5013.4 1210.64  5049.9 1213.66  5079.7 1213.61
  5107.5 1211.04  5138.0 1211.96  5174.4 1210.14  5189.0 1211.75  5238.0 1214.25
  5428.4 1216.61  5472.6 1219.71  5484.0 1222.44  5520.1 1239.77  5555.2 1246.11
  5583.7 1258.14  5597.9 1260.80  5640.6 1264.18  5975.0 1273.96  6233.7 1284.65
#Mann=8,-1,0
  4477.4    0.16       0  4739.4    0.05       0  4983.9    0.16       0
  4995.2    0.07       0  5001.2    0.16       0  5189.0     0.1       0
  5428.4    0.16       0  5975.0     0.1       0
Bank Sta=4995.2,5001.2
Exp/Cntr=0.3,0.1

Type RM Length L Ch R = 1,40,0,0,0
BEGIN DESCRIPTION:
UNT 1040 IN LATR 1.0
END DESCRIPTION:
XS GIS Cut Line= 4
      2943077.89     10036072.97      2942793.18     10036710.08
      2942878.25     10036868.07      2943787.86     10037388.84
#Sta/Elev= 30
  4266.2 1234.42  4303.5 1232.79  4321.2 1229.55  4326.7 1230.64  4349.9 1222.18
  4380.9 1220.12  4764.2 1213.51  4825.6 1213.52  4939.7 1208.49  4985.5 1199.12
  4998.7 1198.39  5001.4 1197.89  5004.7 1198.39  5019.5 1203.08  5029.3 1205.21
  5073.1 1206.40  5133.1 1202.57  5174.2 1206.66  5267.9 1209.75  5368.1 1208.92
  5447.9 1213.07  5463.7 1221.69  5469.5 1222.91  5485.3 1234.60  5500.9 1241.16
  5528.5 1245.94  5571.6 1259.69  5639.2 1265.93  5957.9 1276.98  6191.6 1286.52
#Mann=10,-1,0
  4266.2    0.16       0  4380.9    0.05       0  4764.2    0.16       0
  4998.7    0.07       0  5004.7    0.16       0  5019.5    0.05       0
  5174.2    0.16       0  5267.9     0.1       0  5368.1    0.16       0
  5957.9     0.1       0
Bank Sta=4998.7,5004.7
Exp/Cntr=0.3,0.1

Chan Stop Cuts=-1