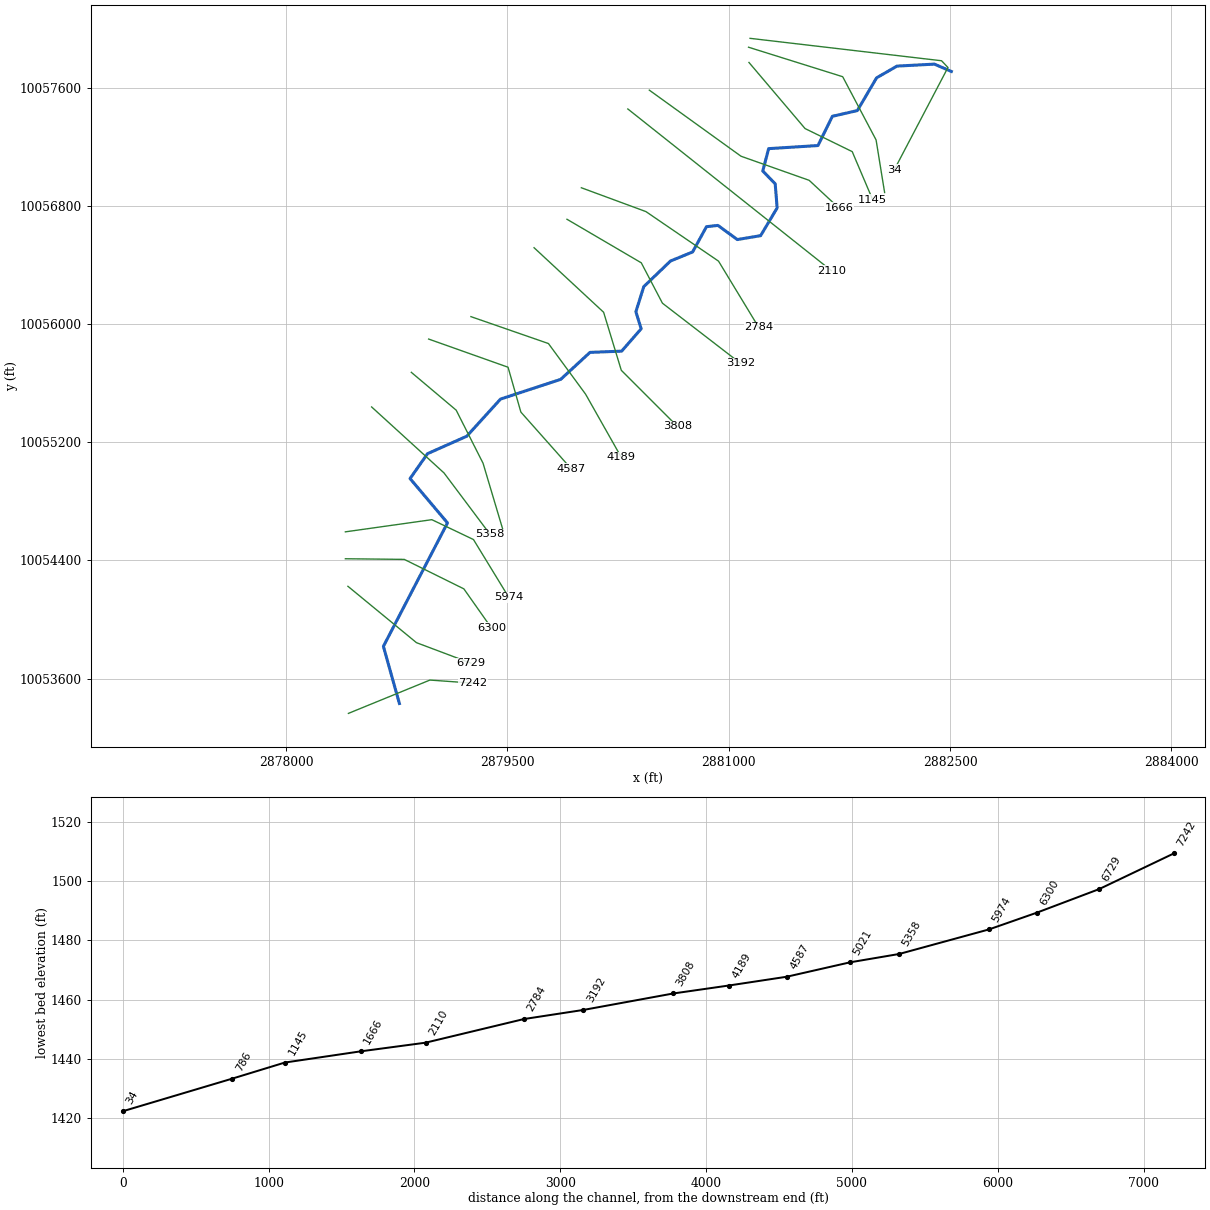
--- UNT 1047 IN LATR.prj (project) ---

Proj Title=UNT 1047 IN LATR Base Level Engineering
Current Plan=p01
Default Exp/Contr=0.3,0.1
English Units
Geom File=g01
Flow File=f01
Plan File=p01
BEGIN DESCRIPTION:
UNT 1047 IN LATR
END DESCRIPTION:

--- UNT 1047 IN LATR.p01 (plan) ---

Plan Title=Multiple Run
Short Identifier=Multiple
Geom File=g01
Flow File=f01
Subcritical Flow
K Sum by GR= 0
Std Step Tol= 0.01
Critical Tol= 0.01
Num of Std Step Trials= 20
Max Error Tol= 0.3
Flow Tol Ratio= 0.001
Split Flow NTrial= 30
Split Flow Tol= 0.02
Split Flow Ratio= 0.02
Log Output Level= 0
Friction Slope Method= 1
Unsteady Friction Slope Method= 2
Unsteady Bridges Friction Slope Method= 1
Parabolic Critical Depth
Global Vel Dist=  1 , 1 , 1
Global Log Level= 0
CheckData=True
Encroach Param= -1, 0, 0, 0
BEGIN DESCRIPTION:
Multiple Run
END DESCRIPTION:

--- UNT 1047 IN LATR.f01 (steady flow) ---

Flow Title=Multiple
Program Version=4.10
Number of Profiles= 7
Profile Names=10-year,25-year,50-year,1pct_min,100-year,1pct_plu,500-year
River Rch & RM=UNT 1047 IN LATR,Reach-1         ,7242
    1003    1474    1890    1775    2401    3247    3888
River Rch & RM=UNT 1047 IN LATR,Reach-1         ,6729
    1268    1879    2421    2283    3088    4176    5039
Boundary for River Rch & Prof#=UNT 1047 IN LATR,Reach-1         , 1
Up Type= 0
Dn Type= 3
Dn Slope=0.0148
Boundary for River Rch & Prof#=UNT 1047 IN LATR,Reach-1         , 2
Up Type= 0
Dn Type= 3
Dn Slope=0.0148
Boundary for River Rch & Prof#=UNT 1047 IN LATR,Reach-1         , 3
Up Type= 0
Dn Type= 3
Dn Slope=0.0148
Boundary for River Rch & Prof#=UNT 1047 IN LATR,Reach-1         , 4
Up Type= 0
Dn Type= 3
Dn Slope=0.0148
Boundary for River Rch & Prof#=UNT 1047 IN LATR,Reach-1         , 5
Up Type= 0
Dn Type= 3
Dn Slope=0.0148
Boundary for River Rch & Prof#=UNT 1047 IN LATR,Reach-1         , 6
Up Type= 0
Dn Type= 3
Dn Slope=0.0148
Boundary for River Rch & Prof#=UNT 1047 IN LATR,Reach-1         , 7
Up Type= 0
Dn Type= 3
Dn Slope=0.0148
DSS Import GetInterval= 0
DSS Import GetPeak= 0
DSS Import FillOption= 0

--- UNT 1047 IN LATR.g01 (geometry) ---

Geom Title=Existing Conditions

River Reach=UNT 1047 IN LATR,Reach-1
Reach XY= 30
      2878768.47     10053430.84      2878660.00     10053818.00
      2879094.33     10054654.58      2878840.68     10054955.08
      2878959.00     10055123.65      2879224.99     10055241.93
      2879453.51     10055493.50      2879861.66     10055627.40
      2880059.83     10055809.95      2880274.43     10055818.44
      2880406.57     10055969.94      2880370.92     10056085.59
      2880424.18     10056255.28      2880605.56     10056429.26
      2880755.25     10056490.37      2880849.21     10056661.75
      2880926.81     10056670.38      2881058.24     10056574.54
      2881216.18     10056600.94      2881328.06     10056788.95
      2881314.85     10056952.37      2881230.63     10057039.02
      2881270.42     10057190.58      2881604.78     10057211.61
      2881702.29     10057409.71      2881871.51     10057448.53
      2882001.82     10057670.27      2882140.06     10057749.88
      2882393.63     10057763.31      2882508.47     10057713.73

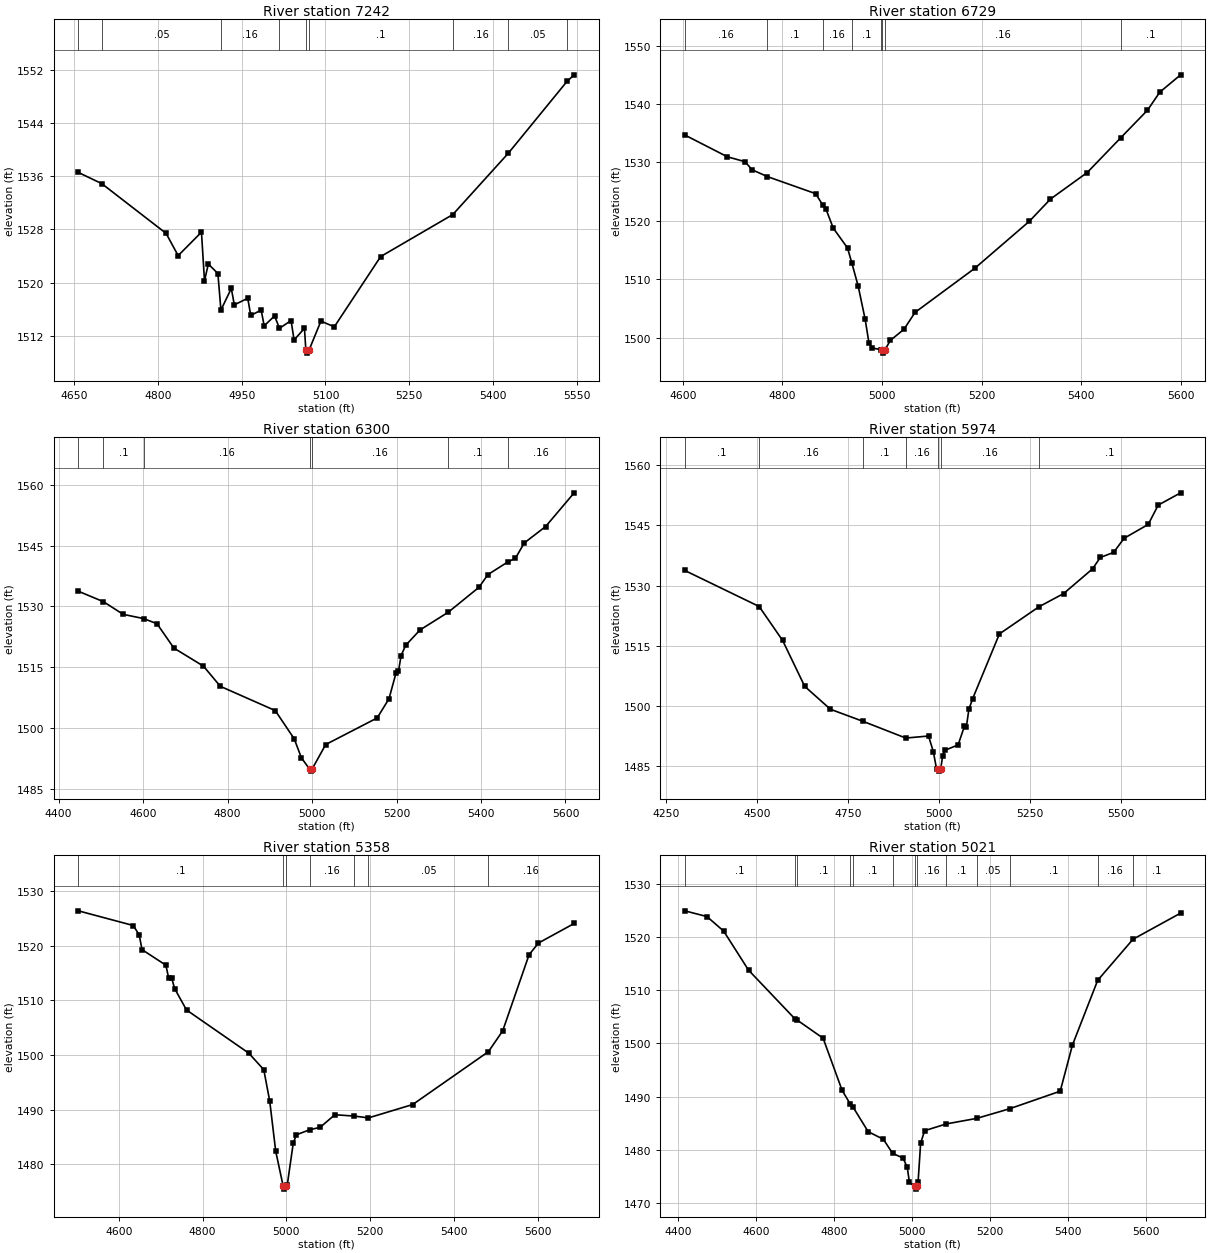
Type RM Length L Ch R = 1,7242,513,513,513
BEGIN DESCRIPTION:
UNT 1047 IN LATR 16.0
END DESCRIPTION:
XS GIS Cut Line= 3
      2878423.14     10053363.93      2878975.19     10053589.62
      2879265.15     10053568.90
#Sta/Elev= 30
  4657.8 1536.57  4699.7 1534.89  4814.8 1527.41  4836.4 1524.06  4878.1 1527.59
  4883.5 1520.29  4890.4 1522.80  4907.5 1521.37  4912.9 1515.87  4931.5 1519.13
  4936.9 1516.66  4960.9 1517.65  4966.3 1515.06  4984.9 1515.88  4990.3 1513.51
  5008.9 1514.99  5017.7 1513.13  5038.4 1514.30  5043.8 1511.37  5062.4 1513.14
  5064.8 1509.90  5067.5 1509.40  5070.8 1509.90  5091.8 1514.21  5115.8 1513.36
  5198.7 1523.92  5327.8 1530.24  5427.0 1539.45  5532.1 1550.26  5544.9 1551.25
#Mann=9,-1,0
  4657.8    0.16       0  4699.7    0.05       0  4912.9    0.16       0
  5017.7     0.1       0  5064.8    0.07       0  5070.8     0.1       0
  5327.8    0.16       0  5427.0    0.05       0  5532.1     0.1       0
Bank Sta=5064.8,5070.8
Exp/Cntr=0.3,0.1

Type RM Length L Ch R = 1,6729,429,429,429
BEGIN DESCRIPTION:
UNT 1047 IN LATR 15.0
END DESCRIPTION:
XS GIS Cut Line= 3
      2878419.64     10054225.03      2878884.05     10053843.09
      2879252.97     10053704.20
#Sta/Elev= 30
  4604.2 1534.71  4689.8 1530.97  4725.0 1530.14  4739.3 1528.75  4770.1 1527.58
  4867.1 1524.65  4881.0 1522.72  4887.9 1521.96  4902.2 1518.76  4930.9 1515.35
  4939.5 1512.80  4952.3 1508.81  4966.1 1503.22  4973.9 1499.10  4980.4 1498.21
  4998.4 1497.91  4999.6 1497.83  5002.4 1497.33  5005.6 1497.83  5017.0 1499.52
  5044.3 1501.42  5066.5 1504.31  5186.3 1511.86  5295.7 1519.90  5338.4 1523.73
  5412.2 1528.28  5479.4 1534.23  5533.1 1538.95  5558.0 1542.06  5599.7 1545.02
#Mann=8,-1,0
  4604.2    0.16       0  4770.1     0.1       0  4881.0    0.16       0
  4939.5     0.1       0  4998.4    0.16       0  4999.6    0.07       0
  5005.6    0.16       0  5479.4     0.1       0
Bank Sta=4999.6,5005.6
Exp/Cntr=0.3,0.1

Type RM Length L Ch R = 1,6300,326,326,326
BEGIN DESCRIPTION:
UNT 1047 IN LATR 14.0
END DESCRIPTION:
XS GIS Cut Line= 4
      2878402.24     10054411.66      2878801.58     10054407.32
      2879205.23     10054207.67      2879391.85     10053942.92
#Sta/Elev= 30
  4446.9 1533.73  4506.3 1531.15  4553.1 1528.02  4601.5 1526.98  4633.1 1525.71
  4673.1 1519.70  4743.1 1515.24  4783.1 1510.26  4913.0 1504.28  4957.9 1497.31
  4974.8 1492.64  4994.2 1489.84  4996.9 1489.34  5000.2 1489.84  5032.4 1495.90
  5154.2 1502.46  5182.2 1507.19  5199.1 1513.65  5204.7 1514.01  5210.9 1517.85
  5221.5 1520.35  5255.6 1524.17  5322.5 1528.55  5395.4 1534.72  5416.3 1537.83
  5463.4 1540.95  5481.6 1541.88  5502.5 1545.65  5553.0 1549.70  5620.5 1558.01
#Mann=7,-1,0
  4446.9    0.16       0  4506.3     0.1       0  4601.5    0.16       0
  4994.2    0.07       0  5000.2    0.16       0  5322.5     0.1       0
  5463.4    0.16       0
Bank Sta=4994.2,5000.2
Exp/Cntr=0.3,0.1

Type RM Length L Ch R = 1,5974,616,616,616
BEGIN DESCRIPTION:
UNT 1047 IN LATR 13.0
END DESCRIPTION:
XS GIS Cut Line= 4
      2878402.26     10054593.95      2878988.21     10054676.42
      2879270.33     10054541.87      2879509.06     10054151.23
#Sta/Elev= 30
  4302.0 1533.78  4506.3 1524.79  4570.8 1516.31  4631.4 1504.87  4702.1 1499.15
  4792.5 1496.11  4909.1 1491.97  4971.6 1492.48  4984.7 1488.59  4993.7 1484.23
  4998.9 1484.22  5001.6 1483.72  5004.9 1484.22  5010.3 1487.45  5015.9 1488.89
  5052.8 1490.26  5070.0 1494.86  5075.5 1494.71  5082.4 1499.14  5092.7 1501.78
  5166.3 1517.95  5274.9 1524.72  5342.7 1528.02  5422.1 1534.18  5443.4 1537.02
  5480.1 1538.29  5508.8 1541.81  5575.0 1545.26  5602.6 1550.09  5664.1 1553.15
#Mann=7,-1,0
  4302.0     0.1       0  4506.3    0.16       0  4792.5     0.1       0
  4909.1    0.16       0  4998.9    0.07       0  5004.9    0.16       0
  5274.9     0.1       0
Bank Sta=4998.9,5004.9
Exp/Cntr=0.3,0.1

Type RM Length L Ch R = 1,5358,337,337,337
BEGIN DESCRIPTION:
UNT 1047 IN LATR 12.0
END DESCRIPTION:
XS GIS Cut Line= 3
      2878580.22     10055440.31      2879070.68     10054993.26
      2879382.36     10054577.68
#Sta/Elev= 30
  4503.7 1526.40  4634.8 1523.71  4648.9 1521.99  4655.7 1519.29  4712.5 1516.45
  4719.2 1514.12  4726.6 1514.05  4733.4 1512.17  4761.8 1508.24  4910.4 1500.33
  4946.2 1497.30  4960.4 1491.54  4974.6 1482.40  4992.6 1475.92  4995.3 1475.42
  4998.6 1475.92  5002.3 1476.20  5016.5 1483.83  5023.9 1485.37  5055.9 1486.30
  5080.7 1486.74  5115.8 1489.05  5162.3 1488.80  5196.0 1488.47  5301.6 1490.92
  5482.2 1500.60  5516.2 1504.40  5579.2 1518.35  5601.6 1520.50  5686.8 1524.08
#Mann=7,-1,0
  4503.7     0.1       0  4992.6    0.07       0  4998.6     0.1       0
  5055.9    0.16       0  5162.3     0.1       0  5196.0    0.05       0
  5482.2    0.16       0
Bank Sta=4992.6,4998.6
Exp/Cntr=0.3,0.1

Type RM Length L Ch R = 1,5021,434,434,434
BEGIN DESCRIPTION:
UNT 1047 IN LATR 11.0
END DESCRIPTION:
XS GIS Cut Line= 4
      2878849.30     10055674.71      2879153.14     10055418.61
      2879335.44     10055058.37      2879469.72     10054607.87
#Sta/Elev= 30
  4417.5 1524.88  4474.3 1523.80  4517.2 1521.07  4580.9 1513.74  4701.1 1504.49
  4704.4 1504.42  4772.1 1500.95  4820.8 1491.16  4842.2 1488.53  4849.2 1487.97
  4887.6 1483.40  4926.6 1481.96  4950.1 1479.34  4977.2 1478.42  4987.8 1476.69
  4993.4 1473.87  5007.1 1473.10  5009.8 1472.60  5013.1 1473.10  5015.7 1474.03
  5022.1 1481.22  5032.4 1483.58  5087.9 1484.85  5165.9 1485.89  5250.4 1487.70
  5380.0 1491.00  5411.3 1499.66  5476.1 1511.83  5566.6 1519.54  5688.7 1524.45
#Mann=13,-1,0
  4417.5     0.1       0  4701.1    0.05       0  4704.4     0.1       0
  4842.2    0.05       0  4849.2     0.1       0  4950.1    0.16       0
  5007.1    0.07       0  5013.1    0.16       0  5087.9     0.1       0
  5165.9    0.05       0  5250.4     0.1       0  5476.1    0.16       0
  5566.6     0.1       0
Bank Sta=5007.1,5013.1
Exp/Cntr=0.3,0.1

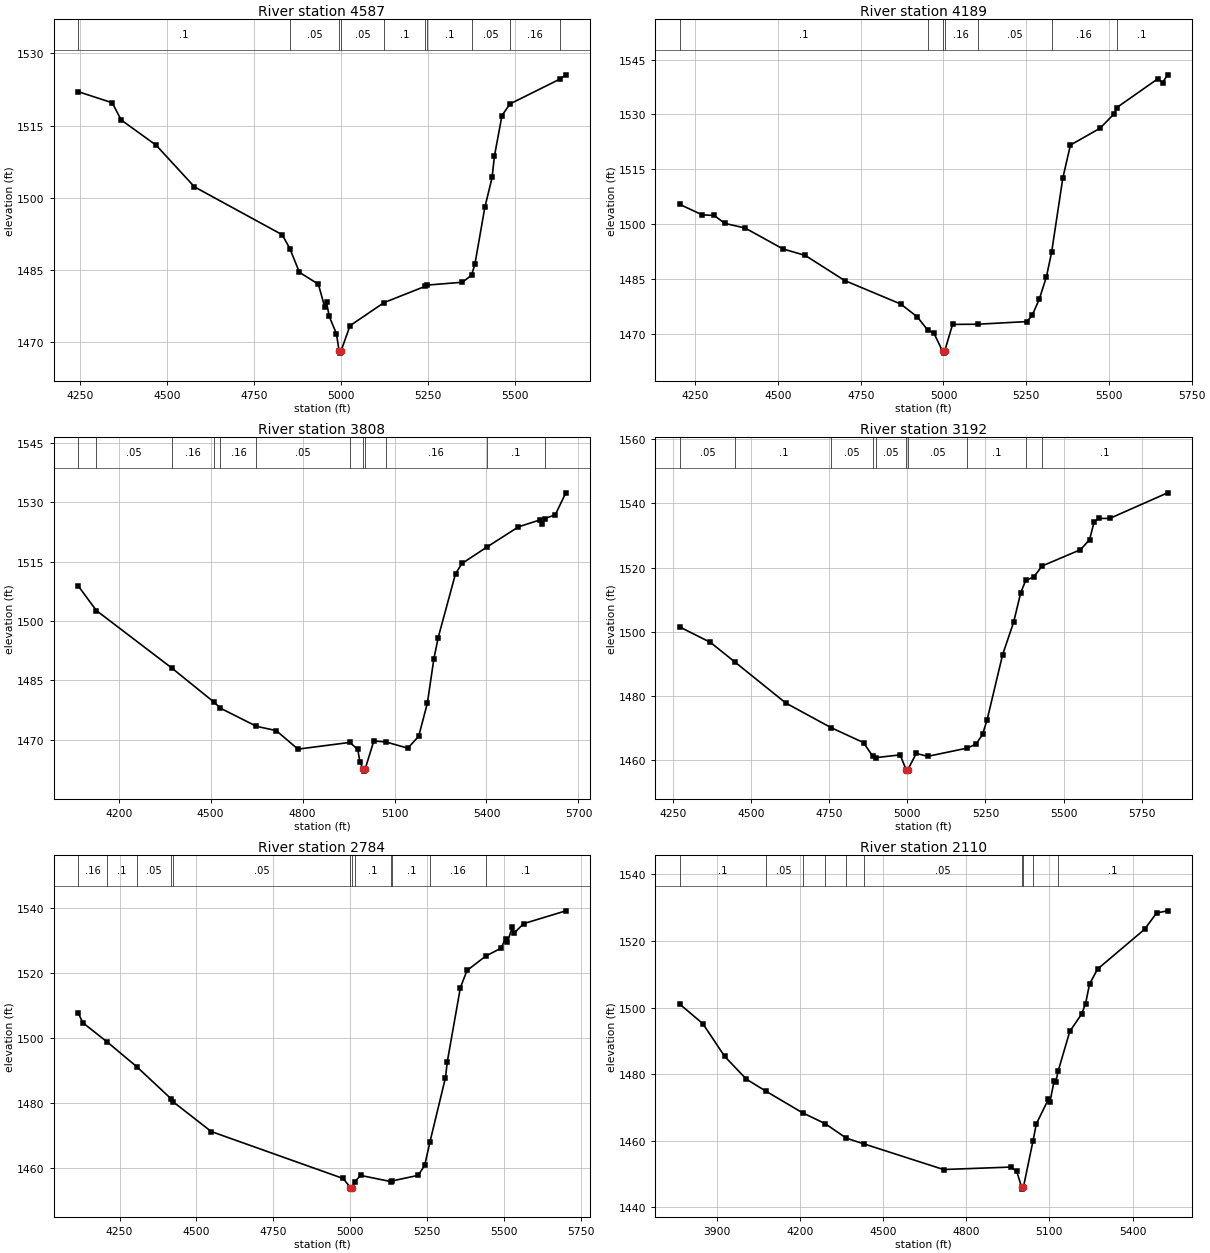
Type RM Length L Ch R = 1,4587,398,398,398
BEGIN DESCRIPTION:
UNT 1047 IN LATR 10.0
END DESCRIPTION:
XS GIS Cut Line= 4
      2878966.55     10055900.36      2879504.71     10055709.41
      2879591.51     10055405.59      2879933.92     10055019.84
#Sta/Elev= 30
  4243.0 1522.08  4341.7 1519.75  4367.3 1516.18  4467.9 1510.93  4578.0 1502.28
  4830.3 1492.33  4852.3 1489.46  4879.7 1484.53  4934.3 1482.05  4952.5 1477.32
  4957.7 1478.32  4965.5 1475.36  4986.3 1471.76  4993.7 1468.23  4996.5 1467.73
  4999.7 1468.23  5025.3 1473.43  5122.9 1478.22  5240.3 1481.58  5247.9 1481.87
  5348.5 1482.46  5374.6 1483.92  5384.4 1486.23  5412.9 1498.01  5433.8 1504.23
  5440.5 1508.68  5462.2 1517.09  5485.0 1519.51  5629.0 1524.68  5645.8 1525.56
#Mann=10,-1,0
  4243.0     0.1       0  4852.3    0.05       0  4993.7   0.035       0
  4999.7    0.05       0  5122.9     0.1       0  5240.3    0.05       0
  5247.9     0.1       0  5374.6    0.05       0  5485.0    0.16       0
  5629.0     0.1       0
Bank Sta=4993.7,4999.7
Exp/Cntr=0.3,0.1

Type RM Length L Ch R = 1,4189,381,381,381
BEGIN DESCRIPTION:
UNT 1047 IN LATR 9.0
END DESCRIPTION:
XS GIS Cut Line= 4
      2879252.97     10056052.29      2879778.14     10055870.00
      2880029.88     10055527.12      2880272.57     10055098.08
#Sta/Elev= 30
  4203.2 1505.41  4271.1 1502.55  4307.6 1502.38  4338.7 1500.24  4400.9 1498.94
  4514.8 1493.25  4582.4 1491.46  4701.6 1484.60  4870.9 1478.18  4921.1 1474.65
  4951.9 1471.11  4971.2 1470.21  4997.5 1465.26  5000.3 1464.76  5003.5 1465.26
  5027.6 1472.61  5103.7 1472.66  5252.1 1473.38  5268.0 1475.08  5289.7 1479.53
  5311.3 1485.67  5326.8 1492.30  5360.7 1512.62  5383.7 1521.63  5473.0 1526.21
  5516.3 1530.21  5523.6 1531.86  5647.9 1539.74  5662.0 1538.70  5677.4 1540.82
#Mann=7,-1,0
  4203.2     0.1       0  4951.9    0.16       0  4997.5    0.07       0
  5003.5    0.16       0  5103.7    0.05       0  5326.8    0.16       0
  5523.6     0.1       0
Bank Sta=4997.5,5003.5
Exp/Cntr=0.3,0.1

Type RM Length L Ch R = 1,3808,616,616,616
BEGIN DESCRIPTION:
UNT 1047 IN LATR 8.0
END DESCRIPTION:
XS GIS Cut Line= 4
      2879680.92     10056519.31      2880152.28     10056081.80
      2880272.07     10055688.57      2880652.08     10055308.56
#Sta/Elev= 30
  4067.2 1508.94  4127.3 1502.62  4373.3 1488.11  4511.5 1479.46  4532.1 1477.96
  4649.7 1473.38  4714.0 1472.31  4784.9 1467.62  4954.1 1469.32  4980.1 1467.55
  4987.1 1464.38  4998.0 1462.57  5000.7 1462.07  5004.0 1462.57  5032.4 1469.69
  5071.8 1469.44  5143.5 1467.86  5178.8 1470.89  5207.1 1479.22  5228.3 1490.41
  5242.5 1495.81  5299.0 1511.93  5320.2 1514.51  5400.6 1518.61  5504.1 1523.74
  5574.8 1525.51  5581.9 1524.37  5589.8 1525.84  5624.3 1526.78  5658.8 1532.34
#Mann=12,-1,0
  4067.2     0.1       0  4127.3    0.05       0  4373.3    0.16       0
  4511.5     0.1       0  4532.1    0.16       0  4649.7    0.05       0
  4954.1     0.1       0  4998.0    0.07       0  5004.0     0.1       0
  5071.8    0.16       0  5400.6     0.1       0  5589.8    0.16       0
Bank Sta=4998,5004
Exp/Cntr=0.3,0.1

Type RM Length L Ch R = 1,3192,408,408,408
BEGIN DESCRIPTION:
UNT 1047 IN LATR 7.0
END DESCRIPTION:
XS GIS Cut Line= 4
      2879904.03     10056712.00      2880407.48     10056416.87
      2880550.71     10056143.43      2881080.21     10055735.46
#Sta/Elev= 30
  4272.3 1501.48  4370.2 1496.68  4450.1 1490.44  4611.4 1477.76  4756.8 1470.05
  4860.5 1465.39  4889.0 1461.23  4898.7 1460.70  4977.2 1461.58  4996.3 1457.01
  4999.1 1456.51  5002.3 1457.01  5028.8 1462.04  5065.5 1461.12  5191.6 1463.69
  5220.0 1464.92  5240.8 1467.94  5255.3 1472.42  5305.1 1492.82  5340.4 1502.99
  5363.1 1512.16  5378.9 1515.99  5404.8 1517.07  5431.3 1520.49  5554.2 1525.58
  5583.3 1528.71  5597.8 1534.23  5612.3 1535.35  5647.6 1535.33  5833.0 1543.32
#Mann=10,-1,0
  4272.3    0.05       0  4450.1     0.1       0  4756.8    0.05       0
  4889.0     0.1       0  4898.7    0.05       0  4996.3   0.035       0
  5002.3    0.05       0  5191.6     0.1       0  5378.9    0.16       0
  5431.3     0.1       0
Bank Sta=4996.3,5002.3
Exp/Cntr=0.3,0.1

Type RM Length L Ch R = 1,2784,674,674,674
BEGIN DESCRIPTION:
UNT 1047 IN LATR 6.0
END DESCRIPTION:
XS GIS Cut Line= 4
      2880001.23     10056925.56      2880438.73     10056764.09
      2880930.92     10056428.16      2881203.60     10055978.89
#Sta/Elev= 30
  4114.4 1507.74  4130.8 1504.56  4209.9 1498.67  4305.4 1491.11  4416.9 1481.27
  4423.8 1480.31  4548.5 1471.13  4977.2 1456.71  5001.2 1453.93  5004.0 1453.43
  5007.2 1453.93  5015.1 1455.68  5034.1 1457.65  5134.8 1455.71  5138.1 1455.98
  5221.4 1457.66  5242.8 1460.71  5260.2 1468.03  5310.5 1487.72  5316.4 1492.62
  5359.1 1515.42  5380.7 1520.68  5441.5 1525.09  5490.9 1527.51  5506.4 1530.43
  5512.2 1529.43  5527.7 1533.91  5533.5 1532.12  5564.5 1535.06  5702.2 1539.02
#Mann=12,-1,0
  4114.4    0.16       0  4209.9     0.1       0  4305.4    0.05       0
  4416.9     0.1       0  4423.8    0.05       0  5001.2   0.035       0
  5007.2    0.05       0  5015.1     0.1       0  5134.8    0.05       0
  5138.1     0.1       0  5260.2    0.16       0  5441.5     0.1       0
Bank Sta=5001.2,5007.2
Exp/Cntr=0.3,0.1

Type RM Length L Ch R = 1,2110,444,444,444
BEGIN DESCRIPTION:
UNT 1047 IN LATR 5.0
END DESCRIPTION:
XS GIS Cut Line= 2
      2880316.37     10057459.38      2881695.04     10056364.25
#Sta/Elev= 30
  3766.1 1501.02  3849.7 1495.13  3928.2 1485.32  4006.7 1478.47  4076.3 1474.91
  4209.2 1468.38  4290.8 1465.12  4367.6 1460.75  4430.8 1459.04  4718.0 1451.34
  4959.9 1452.07  4982.0 1450.86  5000.1 1445.95  5002.9 1445.45  5006.1 1445.95
  5041.1 1459.99  5052.8 1465.01  5096.1 1472.40  5102.5 1471.76  5116.9 1477.92
  5123.3 1477.65  5131.6 1480.88  5173.6 1492.82  5216.2 1498.02  5230.6 1501.13
  5245.0 1507.06  5273.9 1511.55  5443.7 1523.51  5487.0 1528.41  5526.8 1529.05
#Mann=10,-1,0
  3766.1     0.1       0  4076.3    0.05       0  4209.2     0.1       0
  4290.8    0.05       0  4367.6     0.1       0  4430.8    0.05       0
  5000.1   0.035       0  5006.1    0.05       0  5041.1    0.16       0
  5131.6     0.1       0
Bank Sta=5000.1,5006.1
Exp/Cntr=0.3,0.1

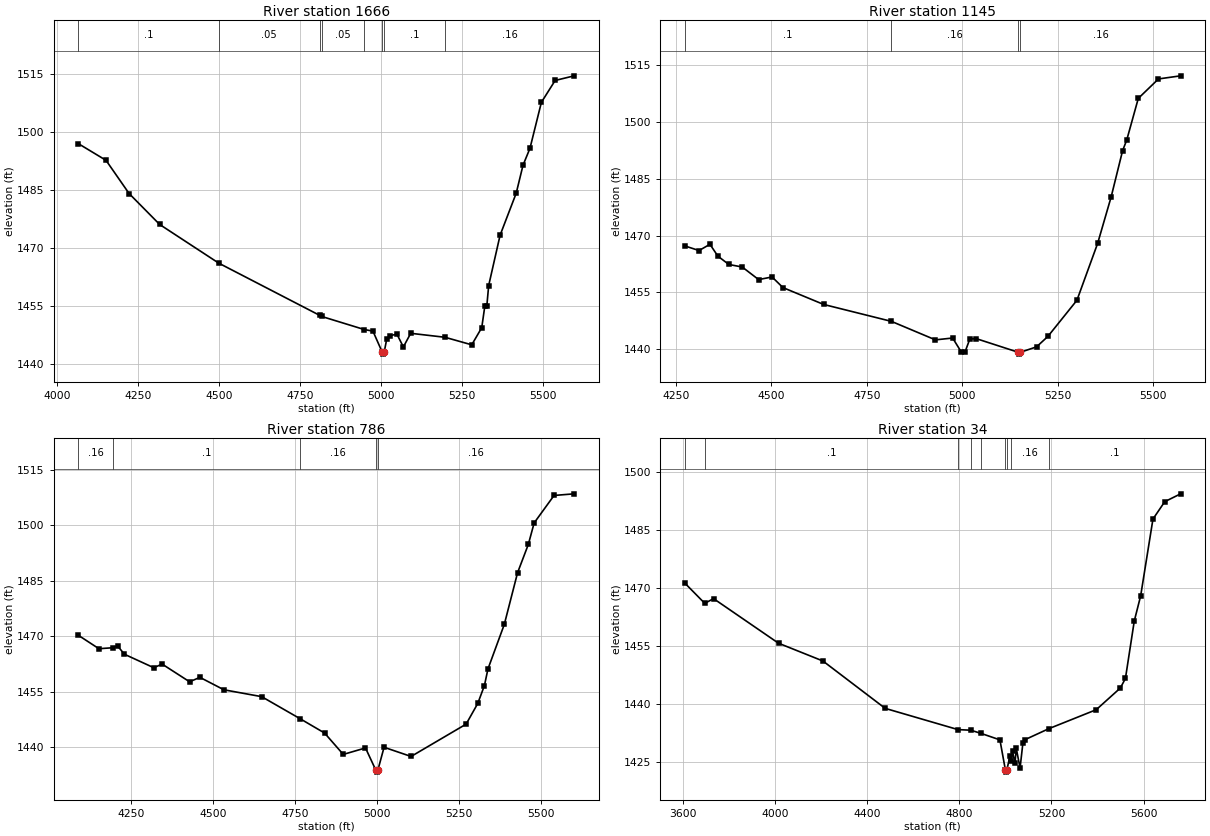
Type RM Length L Ch R = 1,1666,521,521,521
BEGIN DESCRIPTION:
UNT 1047 IN LATR 3.0
END DESCRIPTION:
XS GIS Cut Line= 4
      2880461.74     10057587.01      2881083.27     10057139.09
      2881545.07     10056975.90      2881746.27     10056788.58
#Sta/Elev= 30
  4066.4 1497.01  4151.9 1492.69  4223.1 1484.10  4317.5 1476.09  4500.1 1466.07
  4811.7 1452.56  4817.7 1452.28  4949.5 1448.89  4975.9 1448.49  5004.7 1443.03
  5007.5 1442.53  5010.7 1443.03  5018.7 1446.52  5028.9 1447.33  5050.1 1447.68
  5069.9 1444.39  5092.6 1447.92  5198.4 1446.89  5281.0 1444.94  5311.9 1449.38
  5321.5 1455.03  5327.6 1455.03  5333.3 1460.29  5368.5 1473.30  5418.3 1484.19
  5439.3 1491.42  5460.8 1495.81  5496.0 1507.70  5538.5 1513.36  5597.2 1514.56
#Mann=8,-1,0
  4066.4     0.1       0  4500.1    0.05       0  4811.7     0.1       0
  4817.7    0.05       0  4949.5     0.1       0  5004.7    0.07       0
  5010.7     0.1       0  5198.4    0.16       0
Bank Sta=5004.7,5010.7
Exp/Cntr=0.3,0.1

Type RM Length L Ch R = 1,1145,359,359,359
BEGIN DESCRIPTION:
UNT 1047 IN LATR 2.0
END DESCRIPTION:
XS GIS Cut Line= 4
      2881137.10     10057774.49      2881517.29     10057326.59
      2881836.74     10057170.34      2881975.62     10056843.97
#Sta/Elev= 30
  4273.5 1467.28  4310.8 1466.06  4339.3 1467.71  4360.2 1464.57  4388.7 1462.39
  4423.9 1461.71  4466.7 1458.40  4501.9 1459.09  4530.4 1456.29  4637.0 1451.84
  4814.3 1447.38  4929.5 1442.50  4974.6 1442.99  4997.1 1439.31  5007.0 1439.32
  5019.6 1442.74  5036.5 1442.82  5146.1 1439.24  5148.8 1438.74  5152.1 1439.24
  5194.1 1440.65  5223.8 1443.40  5299.9 1452.95  5354.2 1467.98  5389.6 1480.26
  5419.4 1492.40  5430.3 1495.22  5460.5 1506.19  5513.3 1511.32  5571.3 1512.14
#Mann=4,-1,0
  4273.5     0.1       0  4814.3    0.16       0  5146.1    0.07       0
  5152.1    0.16       0
Bank Sta=5146.1,5152.1
Exp/Cntr=0.3,0.1

Type RM Length L Ch R = 1,786,752,752,752
BEGIN DESCRIPTION:
Mapping XS 6803ddf7
END DESCRIPTION:
XS GIS Cut Line= 4
      2881134.23     10057877.79      2881772.20     10057677.97
      2881998.49     10057249.46      2882056.27     10056893.14
#Sta/Elev= 30
  4087.9 1470.28  4150.8 1466.65  4192.3 1466.91  4207.6 1467.42  4228.6 1465.16
  4318.3 1461.52  4343.8 1462.50  4427.7 1457.72  4459.1 1458.92  4532.5 1455.56
  4647.7 1453.71  4765.9 1447.71  4839.8 1443.89  4896.9 1438.11  4964.8 1439.86
  4996.5 1433.83  4999.3 1433.33  5002.5 1433.83  5021.5 1440.04  5104.0 1437.56
  5272.1 1446.29  5307.6 1451.87  5327.9 1456.68  5338.8 1461.19  5388.7 1473.22
  5429.2 1487.17  5462.1 1494.82  5479.8 1500.61  5540.6 1508.03  5602.0 1508.47
#Mann=5,-1,0
  4087.9    0.16       0  4192.3     0.1       0  4765.9    0.16       0
  4996.5    0.07       0  5002.5    0.16       0
Bank Sta=4996.5,5002.5
Exp/Cntr=0.3,0.1

Type RM Length L Ch R = 1,34,0,0,0
BEGIN DESCRIPTION:
UNT 1047 IN LATR 1.0
END DESCRIPTION:
XS GIS Cut Line= 4
      2881144.42     10057938.00      2882442.16     10057786.09
      2882485.57     10057740.51      2882121.67     10057047.37
#Sta/Elev= 30
  3608.5 1471.23  3695.1 1465.98  3733.4 1467.20  4015.3 1455.66  4208.0 1451.06
  4478.5 1438.79  4794.4 1433.30  4850.0 1433.14  4893.2 1432.34  4976.5 1430.64
  5000.4 1422.79  5003.1 1422.29  5006.4 1422.79  5019.6 1426.38  5025.0 1425.05
  5031.1 1427.69  5041.8 1424.61  5047.5 1428.42  5063.9 1423.34  5076.1 1429.77
  5085.9 1430.71  5188.5 1433.53  5394.6 1438.45  5499.2 1444.06  5521.3 1446.54
  5559.7 1461.41  5587.4 1467.92  5640.8 1487.80  5692.0 1492.30  5760.9 1494.33
#Mann=9,-1,0
  3608.5    0.16       0  3695.1     0.1       0  4794.4    0.05       0
  4850.0    0.16       0  4893.2     0.1       0  5000.4    0.07       0
  5006.4     0.1       0  5025.0    0.16       0  5188.5     0.1       0
Bank Sta=5000.4,5006.4
Exp/Cntr=0.3,0.1

Chan Stop Cuts=-1