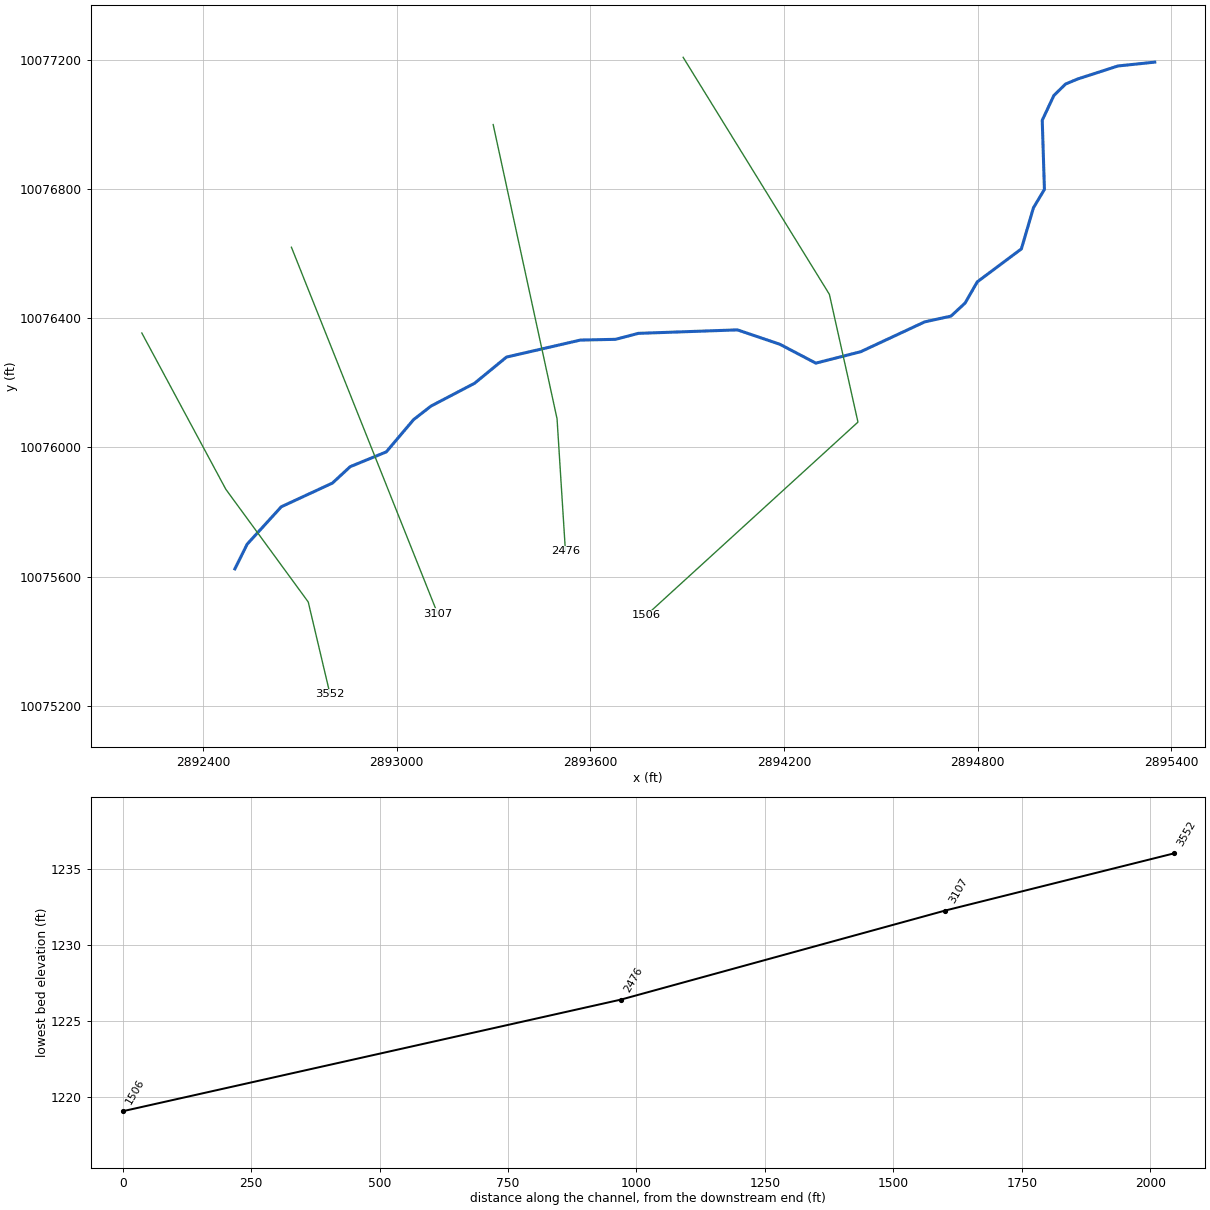
--- UNT 1049 IN LATR.prj (project) ---

Proj Title=UNT 1049 IN LATR Base Level Engineering
Current Plan=p01
Default Exp/Contr=0.3,0.1
English Units
Geom File=g01
Flow File=f01
Plan File=p01
BEGIN DESCRIPTION:
UNT 1049 IN LATR
END DESCRIPTION:

--- UNT 1049 IN LATR.p01 (plan) ---

Plan Title=Multiple Run
Short Identifier=Multiple
Geom File=g01
Flow File=f01
Subcritical Flow
K Sum by GR= 0
Std Step Tol= 0.01
Critical Tol= 0.01
Num of Std Step Trials= 20
Max Error Tol= 0.3
Flow Tol Ratio= 0.001
Split Flow NTrial= 30
Split Flow Tol= 0.02
Split Flow Ratio= 0.02
Log Output Level= 0
Friction Slope Method= 1
Unsteady Friction Slope Method= 2
Unsteady Bridges Friction Slope Method= 1
Parabolic Critical Depth
Global Vel Dist=  1 , 1 , 1
Global Log Level= 0
CheckData=True
Encroach Param= -1, 0, 0, 0
BEGIN DESCRIPTION:
Multiple Run
END DESCRIPTION:

--- UNT 1049 IN LATR.f01 (steady flow) ---

Flow Title=Multiple
Number of Profiles=7
Profile Names=10-year,25-year,50-year,1pct_min,100-year,1pct_plu,500-year
River Rch & RM= UNT 1049 IN LATR,Reach-1,3552
     847    1214    1528    1408    1904    2575    2966
Boundary for River Rch & Prof#=UNT 1049 IN LATR,Reach-1,1
Up Type=0
Dn Type=3
Dn Slope=0.005
Boundary for River Rch & Prof#=UNT 1049 IN LATR,Reach-1,2
Up Type=0
Dn Type=3
Dn Slope=0.005
Boundary for River Rch & Prof#=UNT 1049 IN LATR,Reach-1,3
Up Type=0
Dn Type=3
Dn Slope=0.005
Boundary for River Rch & Prof#=UNT 1049 IN LATR,Reach-1,4
Up Type=0
Dn Type=3
Dn Slope=0.005
Boundary for River Rch & Prof#=UNT 1049 IN LATR,Reach-1,5
Up Type=0
Dn Type=3
Dn Slope=0.005
Boundary for River Rch & Prof#=UNT 1049 IN LATR,Reach-1,6
Up Type=0
Dn Type=3
Dn Slope=0.005
Boundary for River Rch & Prof#=UNT 1049 IN LATR,Reach-1,7
Up Type=0
Dn Type=3
Dn Slope=0.005

--- UNT 1049 IN LATR.g01 (geometry) ---

Geom Title=Existing Conditions

River Reach=UNT 1049 IN LATR,Reach-1
Reach XY= 30
      2892498.47     10075623.73      2892536.53     10075700.19
      2892642.22     10075816.14      2892800.77     10075889.61
      2892855.74     10075940.40      2892967.57     10075986.16
      2893052.09     10076086.09      2893106.07     10076128.09
      2893241.31     10076198.90      2893340.03     10076279.96
      2893568.87     10076332.58      2893677.97     10076334.94
      2893748.60     10076353.43      2894055.61     10076364.20
      2894186.85     10076319.63      2894298.34     10076261.18
      2894437.32     10076296.48      2894635.71     10076389.02
      2894717.27     10076406.88      2894760.82     10076447.29
      2894798.71     10076513.10      2894935.20     10076615.07
      2894972.46     10076742.10      2895006.60     10076799.58
      2894999.82     10077013.53      2895035.81     10077090.30
      2895072.16     10077125.88      2895109.40     10077141.41
      2895234.27     10077181.82      2895348.47     10077193.73

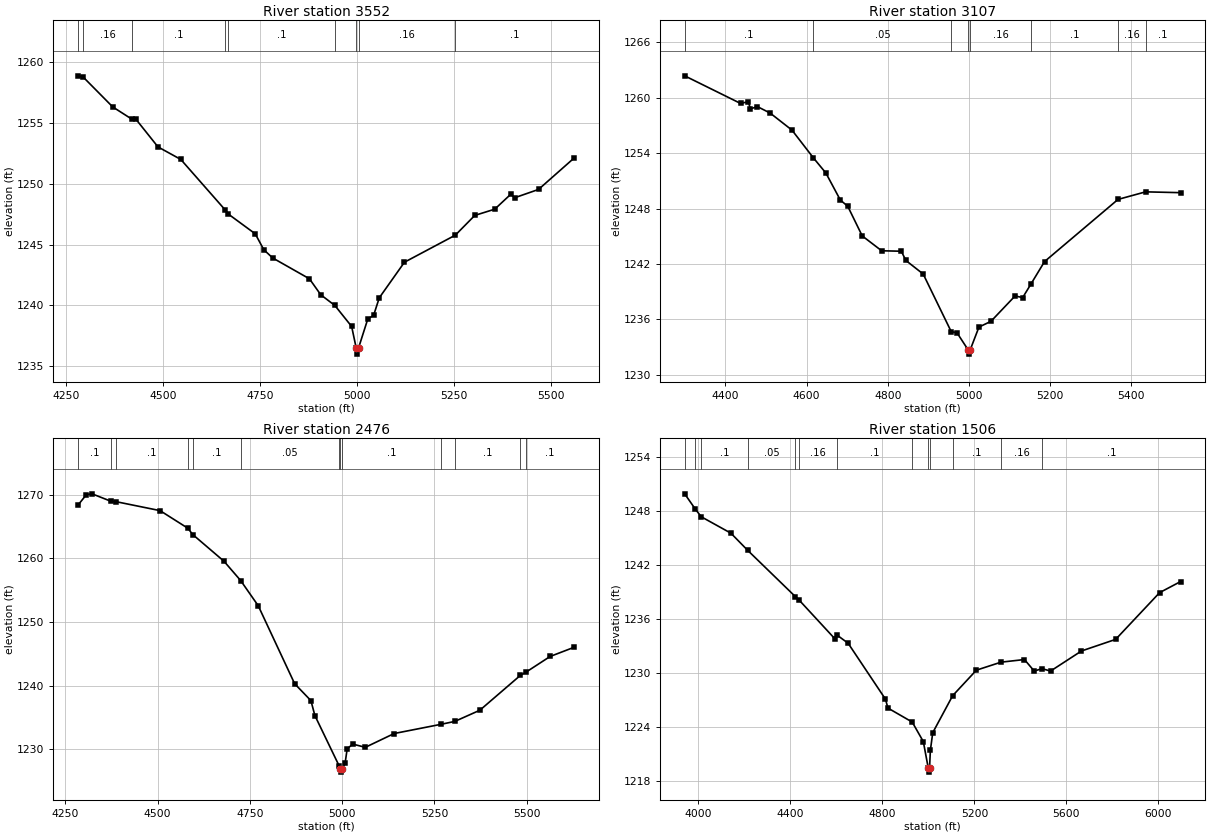
Type RM Length L Ch R = 1,3552,445,445,445
BEGIN DESCRIPTION:
UNT 1049 IN LATR 4.0
END DESCRIPTION:
XS GIS Cut Line= 4
      2892210.17     10076354.53      2892470.58     10075870.16
      2892725.79     10075521.20      2892793.47     10075234.85
#Sta/Elev= 30
  4282.1 1258.84  4295.5 1258.72  4370.9 1256.29  4420.4 1255.28  4430.6 1255.28
  4487.4 1253.01  4546.2 1251.98  4660.9 1247.82  4667.6 1247.52  4737.7 1245.88
  4759.9 1244.57  4782.6 1243.90  4877.2 1242.19  4906.4 1240.88  4942.7 1240.00
  4985.9 1238.28  4997.6 1236.51  5000.3 1236.01  5003.6 1236.51  5027.6 1238.91
  5042.3 1239.18  5057.0 1240.63  5121.8 1243.55  5252.8 1245.77  5302.9 1247.39
  5354.2 1247.90  5395.3 1249.12  5405.6 1248.84  5466.9 1249.52  5558.6 1252.10
#Mann=9,-1,0
  4282.1     0.1       0  4295.5    0.16       0  4420.4     0.1       0
  4660.9    0.05       0  4667.6     0.1       0  4942.7    0.16       0
  4997.6    0.07       0  5003.6    0.16       0  5252.8     0.1       0
Bank Sta=4997.6,5003.6
Exp/Cntr=0.3,0.1

Type RM Length L Ch R = 1,3107,631,631,631
BEGIN DESCRIPTION:
UNT 1049 IN LATR 3.0
END DESCRIPTION:
XS GIS Cut Line= 2
      2892673.72     10076620.12      2893126.81     10075484.79
#Sta/Elev= 30
  4299.4 1262.38  4437.2 1259.39  4456.1 1259.58  4461.5 1258.80  4478.5 1259.05
  4510.0 1258.35  4563.9 1256.50  4616.8 1253.49  4647.4 1251.86  4683.1 1248.93
  4701.3 1248.26  4737.0 1245.05  4784.9 1243.44  4833.4 1243.39  4844.6 1242.39
  4887.3 1240.92  4956.3 1234.69  4970.8 1234.55  4997.5 1232.75  5000.2 1232.25
  5003.5 1232.75  5024.7 1235.18  5054.3 1235.80  5113.8 1238.55  5132.5 1238.37
  5152.9 1239.84  5186.4 1242.27  5367.5 1249.00  5435.6 1249.82  5521.8 1249.73
#Mann=8,-1,0
  4299.4     0.1       0  4616.8    0.05       0  4956.3    0.16       0
  4997.5    0.07       0  5003.5    0.16       0  5152.9     0.1       0
  5367.5    0.16       0  5435.6     0.1       0
Bank Sta=4997.5,5003.5
Exp/Cntr=0.3,0.1

Type RM Length L Ch R = 1,2476,970,970,970
BEGIN DESCRIPTION:
UNT 1049 IN LATR 2.0
END DESCRIPTION:
XS GIS Cut Line= 3
      2893298.71     10077000.35      2893496.62     10076088.91
      2893522.59     10075678.71
#Sta/Elev= 30
  4284.8 1268.41  4307.1 1270.02  4322.3 1270.14  4374.8 1268.94  4386.2 1268.92
  4506.5 1267.50  4581.9 1264.73  4595.1 1263.74  4679.8 1259.54  4724.9 1256.51
  4772.5 1252.55  4871.2 1240.29  4915.3 1237.63  4926.0 1235.29  4992.1 1227.33
  4994.6 1226.89  4997.4 1226.39  5000.6 1226.89  5007.9 1227.80  5013.5 1230.03
  5028.3 1230.80  5062.7 1230.29  5140.9 1232.46  5267.2 1233.90  5305.0 1234.36
  5373.0 1236.12  5482.8 1241.60  5497.6 1242.09  5563.3 1244.57  5628.5 1246.02
#Mann=13,-1,0
  4284.8     0.1       0  4374.8    0.05       0  4386.2     0.1       0
  4581.9    0.05       0  4595.1     0.1       0  4724.9    0.05       0
  4992.1     0.1       0  4994.6    0.07       0  5000.6     0.1       0
  5267.2    0.16       0  5305.0     0.1       0  5482.8    0.16       0
  5497.6     0.1       0
Bank Sta=4994.6,5000.6
Exp/Cntr=0.3,0.1

Type RM Length L Ch R = 1,1506,0,0,0
BEGIN DESCRIPTION:
UNT 1049 IN LATR 1.0
END DESCRIPTION:
XS GIS Cut Line= 4
      2893887.26     10077208.68      2894340.37     10076474.33
      2894428.91     10076078.49      2893773.03     10075479.87
#Sta/Elev= 30
  3940.0 1249.94  3986.6 1248.23  4012.2 1247.39  4141.0 1245.57  4214.2 1243.66
  4421.6 1238.52  4438.1 1238.13  4592.1 1233.87  4600.7 1234.29  4650.7 1233.35
  4812.8 1227.15  4824.0 1226.15  4929.4 1224.60  4977.7 1222.43  4998.8 1219.54
  5001.6 1219.04  5004.8 1219.54  5008.4 1221.47  5018.7 1223.42  5105.3 1227.53
  5208.4 1230.36  5315.6 1231.25  5417.4 1231.54  5460.0 1230.26  5493.6 1230.53
  5530.9 1230.26  5665.3 1232.49  5814.0 1233.78  6005.2 1238.97  6096.5 1240.20
#Mann=13,-1,0
  3940.0     0.1       0  3986.6    0.05       0  4012.2     0.1       0
  4214.2    0.05       0  4421.6     0.1       0  4438.1    0.16       0
  4600.7     0.1       0  4929.4    0.16       0  4998.8    0.07       0
  5004.8    0.16       0  5105.3     0.1       0  5315.6    0.16       0
  5493.6     0.1       0
Bank Sta=4998.8,5004.8
Exp/Cntr=0.3,0.1

Chan Stop Cuts=-1