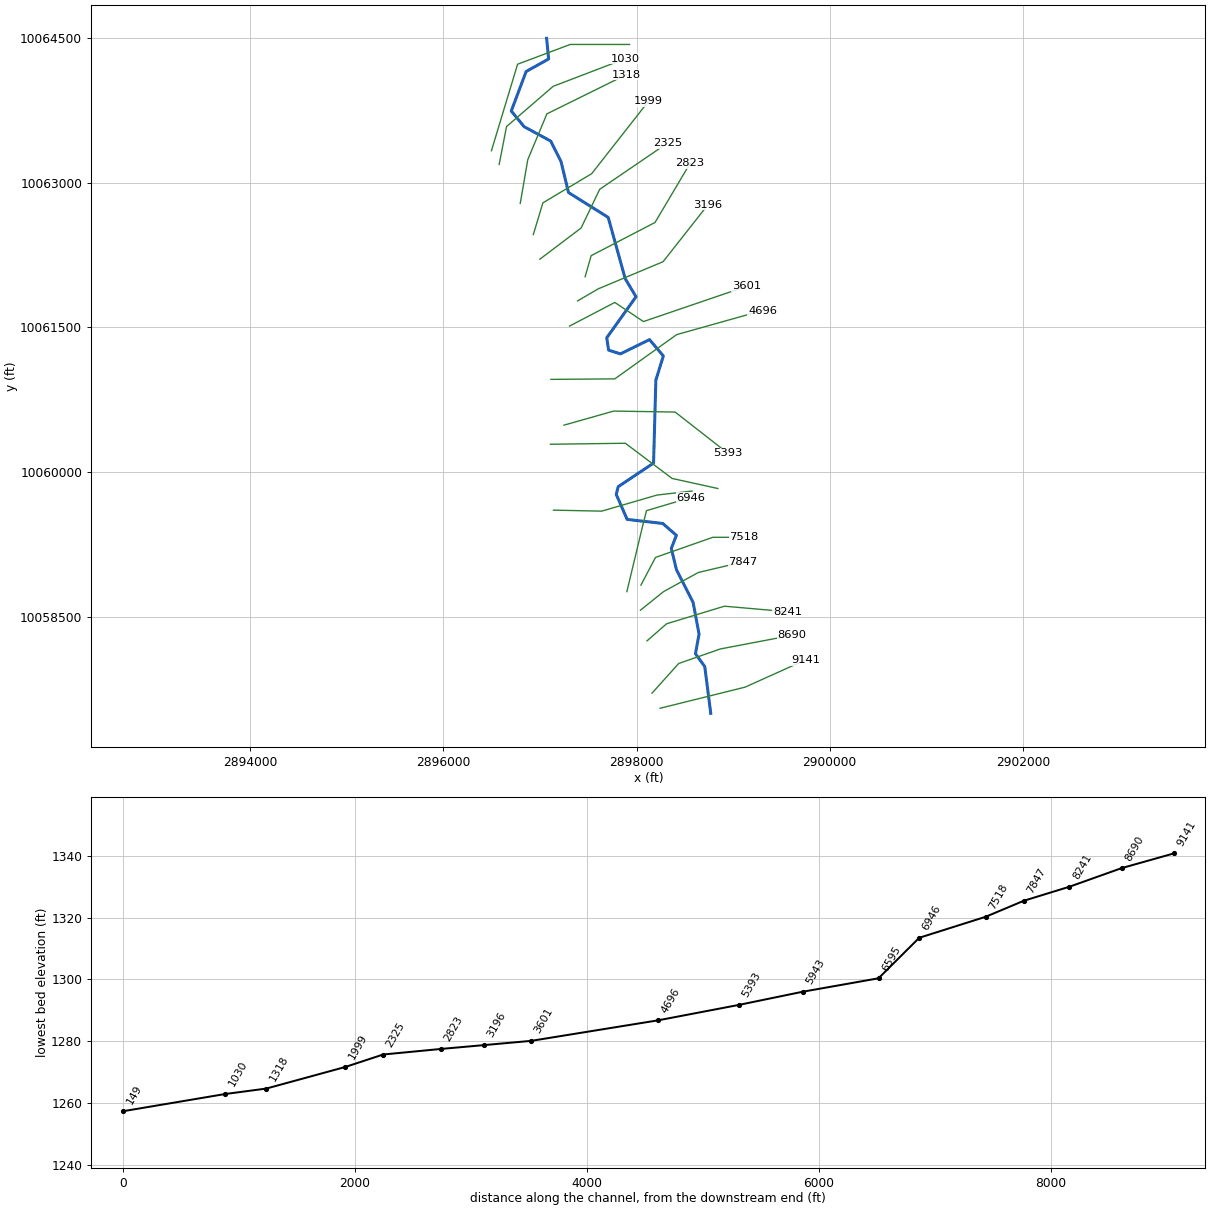
--- UNT 1051 IN LATR.prj (project) ---

Proj Title=UNT 1051 IN LATR Base Level Engineering
Current Plan=p01
Default Exp/Contr=0.3,0.1
English Units
Geom File=g01
Flow File=f01
Plan File=p01
Y Axis Title=Elevation
X Axis Title(PF)=Main Channel Distance
X Axis Title(XS)=Station
BEGIN DESCRIPTION:
UNT 1051 IN LATR
END DESCRIPTION:
DSS Export Rating Curves= 0
DSS Export Rating Curve Sorted= 0
DSS Export Volume Flow Curves= 0
DXF OffsetX= 0
DXF OffsetY= 0
DXF ScaleX= 1
DXF ScaleY= 10

--- UNT 1051 IN LATR.p01 (plan) ---

Plan Title=Multiple Run
Short Identifier=Multiple
Geom File=g01
Flow File=f01
Subcritical Flow
K Sum by GR= 0
Std Step Tol= 0.01
Critical Tol= 0.01
Num of Std Step Trials= 20
Max Error Tol= 0.3
Flow Tol Ratio= 0.001
Split Flow NTrial= 30
Split Flow Tol= 0.02
Split Flow Ratio= 0.02
Log Output Level= 0
Friction Slope Method= 1
Unsteady Friction Slope Method= 2
Unsteady Bridges Friction Slope Method= 1
Parabolic Critical Depth
Global Vel Dist=  1 , 1 , 1
Global Log Level= 0
CheckData=True
Encroach Param= -1, 0, 0, 0
BEGIN DESCRIPTION:
Multiple Run
END DESCRIPTION:

--- UNT 1051 IN LATR.f01 (steady flow) ---

Flow Title=Multiple
Number of Profiles=7
Profile Names=10-year,25-year,50-year,1pct_min,100-year,1pct_plu,500-year
River Rch & RM= UNT 1051 IN LATR,Reach-1,9141
     907    1311    1662    1543    2086    2821    3298
River Rch & RM= UNT 1051 IN LATR,Reach-1,6595
    1990    3027    3972    3810    5153    6969    8705
River Rch & RM= UNT 1051 IN LATR,Reach-1,1999
    1991    3023    3961    3794    5131    6938    8641
Boundary for River Rch & Prof#=UNT 1051 IN LATR,Reach-1,1
Up Type=0
Dn Type=3
Dn Slope=0.005
Boundary for River Rch & Prof#=UNT 1051 IN LATR,Reach-1,2
Up Type=0
Dn Type=3
Dn Slope=0.005
Boundary for River Rch & Prof#=UNT 1051 IN LATR,Reach-1,3
Up Type=0
Dn Type=3
Dn Slope=0.005
Boundary for River Rch & Prof#=UNT 1051 IN LATR,Reach-1,4
Up Type=0
Dn Type=3
Dn Slope=0.005
Boundary for River Rch & Prof#=UNT 1051 IN LATR,Reach-1,5
Up Type=0
Dn Type=3
Dn Slope=0.005
Boundary for River Rch & Prof#=UNT 1051 IN LATR,Reach-1,6
Up Type=0
Dn Type=3
Dn Slope=0.005
Boundary for River Rch & Prof#=UNT 1051 IN LATR,Reach-1,7
Up Type=0
Dn Type=3
Dn Slope=0.005

--- UNT 1051 IN LATR.g01 (geometry) ---

Geom Title=Existing Conditions
Program Version=4.10

River Reach=UNT 1051 IN LATR,Reach-1
Reach XY= 30
      2898768.47     10057502.51      2898706.35     10057988.02
      2898610.11     10058119.46      2898647.16     10058323.38
      2898585.33      10058652.7      2898412.98     10058990.89
       2898360.1     10059210.94      2898412.42     10059346.52
      2898271.32     10059469.24      2897902.62     10059511.48
      2897789.92     10059769.69      2897809.62       10059850.
      2898176.09     10060094.89      2898199.85     10060953.49
      2898277.38     10061203.87      2898134.51     10061373.44
      2897832.83      10061225.9      2897710.65     10061264.35
      2897691.27     10061392.43      2897994.49     10061817.23
       2897882.2     10062005.28      2897706.64     10062639.03
      2897295.23     10062896.85      2897217.46     10063218.32
      2897110.52     10063430.01      2896835.74     10063578.61
      2896702.65     10063740.93      2896856.32     10064150.13
      2897089.39     10064279.92      2897068.47     10064493.73

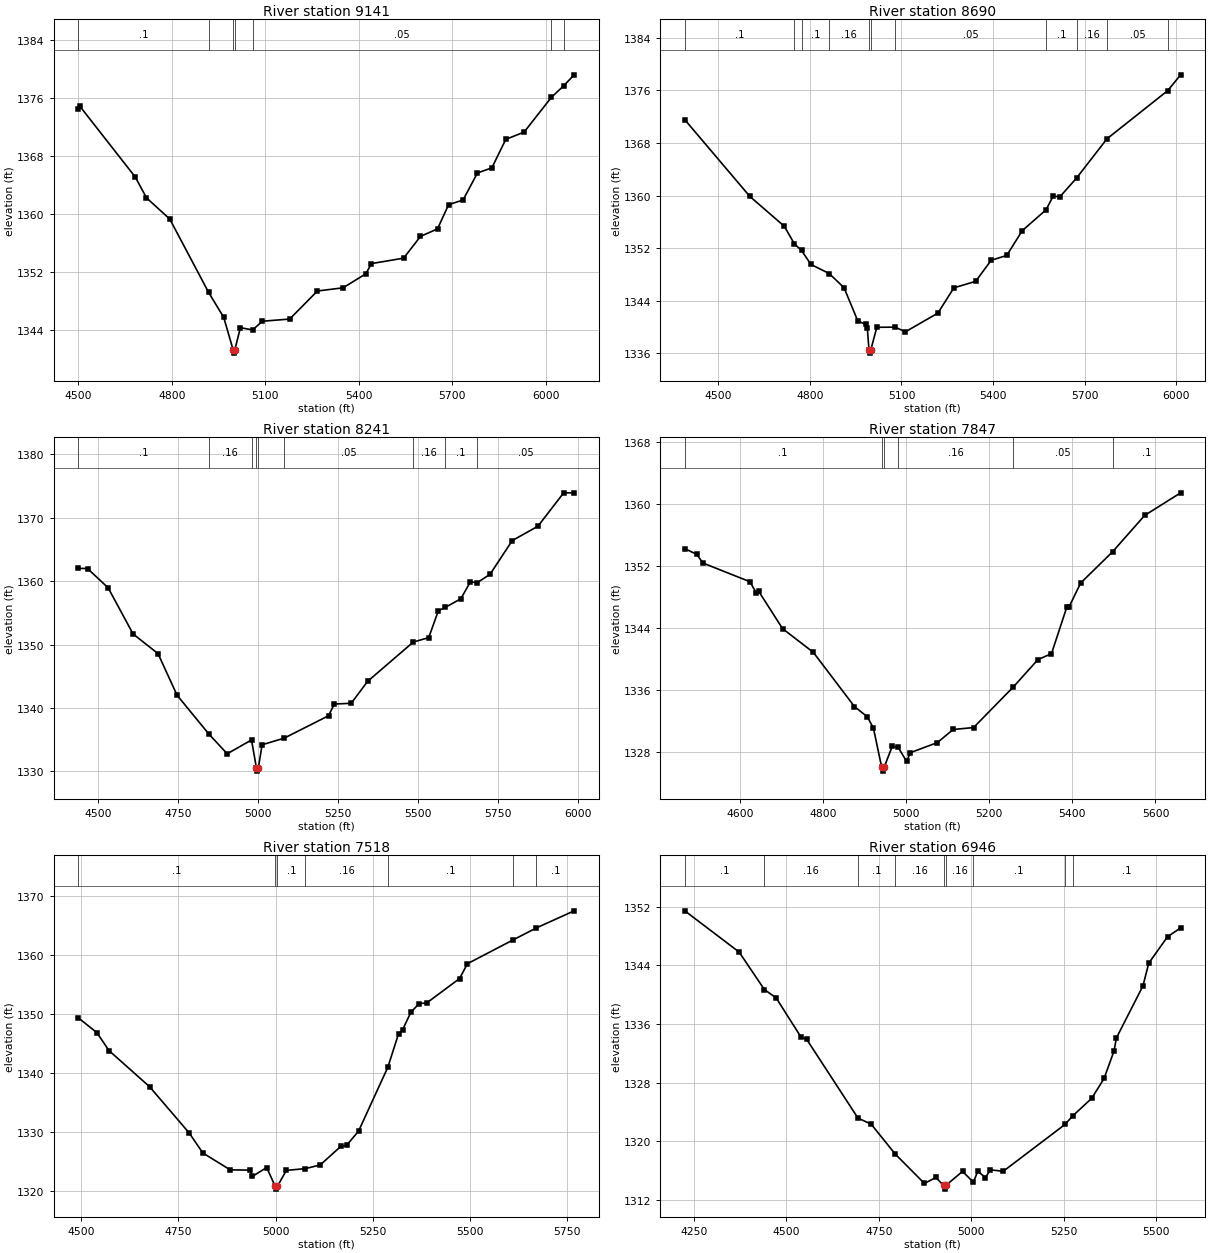
Type RM Length L Ch R = 1 ,9141    ,451,451,451
BEGIN DESCRIPTION:
UNT 1051 IN LATR 17.0
END DESCRIPTION:
XS GIS Cut Line= 3
      2898243.46     10057555.34      2899123.63     10057774.08
      2899748.62     10058055.32
#Sta/Elev= 30
  4499.6 1374.46  4504.8 1374.84  4682.3  1365.1  4718.5 1362.22  4793.3 1359.29
  4918.1 1349.17  4966.5 1345.73  4996.4  1341.3  4999.1  1340.8  5002.4  1341.3
    5020 1344.31  5059.5    1344  5090.5  1345.2  5178.4  1345.5  5267.3 1349.37
  5349.7 1349.81  5423.1 1351.75  5440.8 1353.15  5544.3  1353.9  5598.3  1356.9
  5653.1 1357.94  5688.7 1361.28    5735 1361.92  5781.3 1365.65  5827.6 1366.36
  5872.4 1370.29  5931.2 1371.29  6018.7 1376.08  6058.3 1377.68  6091.9 1379.19
#Mann= 7 ,-1 , 0
  4499.6      .1       0  4918.1     .16       0  4996.4     .07       0
  5002.4     .16       0  5059.5     .05       0  6018.7      .1       0
  6058.3     .05       0
Bank Sta=4996.4,5002.4
XS Rating Curve= 0 ,0
Exp/Cntr=0.3,0.1

Type RM Length L Ch R = 1 ,8690    ,449,449,449
BEGIN DESCRIPTION:
UNT 1051 IN LATR 16.0
END DESCRIPTION:
XS GIS Cut Line= 4
      2898160.08     10057711.57      2898436.13     10058018.87
      2898868.42     10058169.91      2899607.97     10058310.53
#Sta/Elev= 30
  4390.5 1371.53  4603.4 1359.87  4716.3 1355.33  4749.3 1352.66  4772.8 1351.64
  4803.6 1349.52  4863.6 1348.13    4912 1345.98  4957.2 1340.91    4983 1340.41
  4988.3  1339.8  4993.7 1336.53  4996.5 1336.03  4999.7 1336.53  5019.3 1339.96
  5078.9 1339.98  5113.2 1339.28  5219.2 1342.11  5271.7 1345.96    5343 1346.95
  5393.9 1350.15  5444.8 1350.89  5495.7 1354.66  5573.6 1357.83  5597.5 1359.97
  5617.8 1359.75  5673.3 1362.65  5772.9 1368.62  5972.1 1375.96  6014.3 1378.36
#Mann= 11 ,-1 , 0
  4390.5      .1       0  4749.3     .16       0  4772.8      .1       0
  4863.6     .16       0  4993.7     .07       0  4999.7     .16       0
  5078.9     .05       0  5573.6      .1       0  5673.3     .16       0
  5772.9     .05       0  5972.1      .1       0
Bank Sta=4993.7,4999.7
XS Rating Curve= 0 ,0
Exp/Cntr=0.3,0.1

Type RM Length L Ch R = 1 ,8241    ,394,394,394
BEGIN DESCRIPTION:
UNT 1051 IN LATR 15.0
END DESCRIPTION:
XS GIS Cut Line= 4
      2898108.01     10058253.24      2898311.13     10058430.33
      2898910.09     10058612.62      2899561.11     10058555.33
#Sta/Elev= 30
    4438 1362.03  4466.7    1362  4531.2 1358.95  4609.1 1351.67  4686.9 1348.57
  4746.5    1342  4846.2 1335.85  4903.1 1332.76  4979.1 1334.94  4994.4 1330.52
  4997.1 1330.02  5000.4 1330.52  5012.1 1334.18  5080.9 1335.22  5219.6 1338.76
  5237.8 1340.61  5290.6 1340.73    5342  1344.2  5484.6  1350.4  5532.7 1351.09
  5562.8 1355.34    5584 1355.85  5633.1 1357.23  5663.2 1359.93  5683.4 1359.74
  5724.3 1361.09  5793.7 1366.41    5874 1368.68  5954.3 1373.95  5987.1 1373.95
#Mann= 9 ,-1 , 0
    4438      .1       0  4846.2     .16       0  4979.1      .1       0
  4994.4     .07       0  5000.4      .1       0  5080.9     .05       0
  5484.6     .16       0    5584      .1       0  5683.4     .05       0
Bank Sta=4994.4,5000.4
XS Rating Curve= 0 ,0
Exp/Cntr=0.3,0.1

Type RM Length L Ch R = 1 ,7847    ,329,329,329
BEGIN DESCRIPTION:
UNT 1051 IN LATR 14.0
END DESCRIPTION:
XS GIS Cut Line= 4
      2898040.27     10058570.93      2898279.88     10058763.66
      2898639.26     10058961.58      2899102.75     10059070.94
#Sta/Elev= 30
  4466.6 1354.22  4495.7 1353.47  4510.1 1352.36  4623.7 1349.94  4638.1 1348.54
  4644.5 1348.71  4702.1 1343.88  4776.1 1340.82  4875.2 1333.81  4906.4 1332.48
  4920.9 1331.01  4940.7 1325.97  4943.5 1325.47  4946.7 1325.97    4966 1328.66
  4980.1 1328.57  5000.8 1326.72  5009.6 1327.85  5074.9 1329.16  5112.8 1330.85
    5162  1331.1  5257.3 1336.32  5317.1 1339.89  5349.6 1340.64  5386.8 1346.71
  5391.9 1346.69  5419.9 1349.78  5496.7 1353.81    5574 1358.51  5660.6 1361.43
#Mann= 6 ,-1 , 0
  4466.6      .1       0  4940.7     .07       0  4946.7      .1       0
  4980.1     .16       0  5257.3     .05       0  5496.7      .1       0
Bank Sta=4940.7,4946.7
XS Rating Curve= 0 ,0
Exp/Cntr=0.3,0.1

Type RM Length L Ch R = 1 ,7518    ,572,572,572
BEGIN DESCRIPTION:
UNT 1051 IN LATR 13.0
END DESCRIPTION:
XS GIS Cut Line= 4
      2898045.51     10058831.38      2898196.55     10059117.83
       2898790.3     10059326.16      2899113.23     10059326.16
#Sta/Elev= 30
  4492.4 1349.38  4540.3 1346.85  4571.2 1343.82  4675.6 1337.69  4777.7 1329.82
  4812.9 1326.42  4883.3 1323.55  4934.7 1323.51    4940 1322.43  4977.2 1323.95
  4998.9 1320.78  5001.7 1320.28  5004.9 1320.78  5027.6 1323.46    5077 1323.77
    5115 1324.39    5168 1327.55  5182.6 1327.71  5213.6 1330.14    5289    1341
  5316.4 1346.66  5326.9 1347.35  5348.1 1350.31  5369.3  1351.8    5389 1351.91
  5473.6 1356.06  5493.6 1358.57  5610.1 1362.58  5671.3 1364.66  5768.4 1367.56
#Mann= 7 ,-1 , 0
  4492.4      .1       0  4998.9     .07       0  5004.9      .1       0
    5077     .16       0    5289      .1       0  5610.1     .05       0
  5671.3      .1       0
Bank Sta=4998.9,5004.9
XS Rating Curve= 0 ,0
Exp/Cntr=0.3,0.1

Type RM Length L Ch R = 1 ,6946    ,351,351,351
BEGIN DESCRIPTION:
UNT 1051 IN LATR 12.0
END DESCRIPTION:
XS GIS Cut Line= 4
      2897899.67     10058763.67      2898061.13     10059435.54
       2898102.8      10059602.2      2898561.12     10059737.62
#Sta/Elev= 30
  4225.6 1351.42  4372.5  1345.8  4440.8 1340.69  4472.5 1339.56  4540.4 1334.17
  4554.8 1333.93  4693.9 1323.17  4729.6 1322.34  4794.6 1318.27  4873.6 1314.26
  4904.5 1315.08  4925.2 1313.99    4928 1313.49  4931.2 1313.99  4976.6  1315.9
    5006 1314.44  5017.8 1315.93  5038.4 1315.07  5051.9 1316.12  5086.6 1315.92
  5253.8 1322.31  5274.1 1323.45  5326.1 1325.88  5359.3 1328.57  5386.3 1332.33
  5392.6 1334.09  5464.4 1341.18  5480.1 1344.29    5531 1347.89  5566.3 1349.09
#Mann= 9 ,-1 , 0
  4225.6      .1       0  4440.8     .16       0  4693.9      .1       0
  4794.6     .16       0  4925.2     .07       0  4931.2     .16       0
    5006      .1       0  5253.8     .16       0  5274.1      .1       0
Bank Sta=4925.2,4931.2
XS Rating Curve= 0 ,0
Exp/Cntr=0.3,0.1

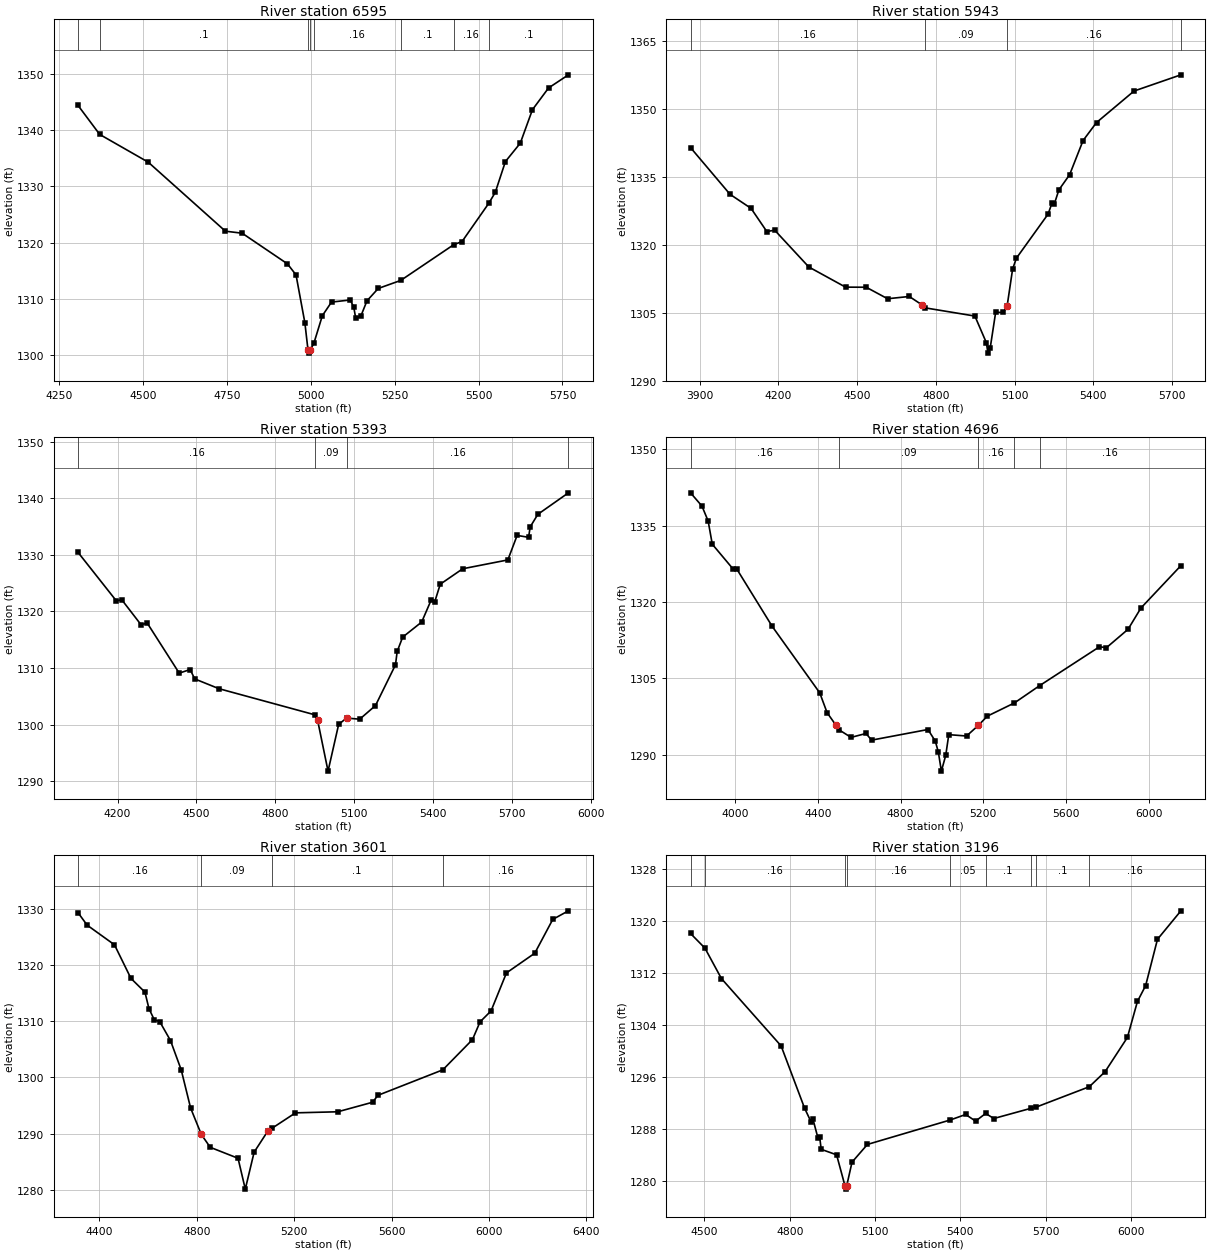
Type RM Length L Ch R = 1 ,6595    ,652,652,652
BEGIN DESCRIPTION:
UNT 1051 IN LATR 11.0
END DESCRIPTION:
XS GIS Cut Line= 4
      2897139.24     10059607.41      2897639.26     10059596.99
      2898212.17     10059763.66      2898575.12     10059805.14
#Sta/Elev= 30
  4305.7 1344.35  4370.2 1339.21    4515 1334.28    4745 1322.03    4795 1321.67
    4930 1316.23  4955.6 1314.27    4982 1305.76  4991.4 1300.88  4994.1 1300.38
  4997.4 1300.88  5008.8 1302.13  5034.1 1307.03  5061.4 1309.44  5117.4 1309.82
  5127.9  1308.5  5133.7 1306.54  5148.7 1306.93  5167.2 1309.67  5200.7 1311.86
  5267.9 1313.29    5426 1319.64  5450.6 1320.19  5530.3 1326.98  5549.7 1328.92
  5579.9 1334.39  5624.3 1337.66  5660.5  1343.6  5708.6 1347.46  5767.8 1349.79
#Mann= 8 ,-1 , 0
  4305.7     .16       0  4370.2      .1       0  4991.4     .07       0
  4997.4      .1       0  5008.8     .16       0  5267.9      .1       0
    5426     .16       0  5530.3      .1       0
Bank Sta=4991.4,4997.4
XS Rating Curve= 0 ,0
Exp/Cntr=0.3,0.1

Type RM Length L Ch R = 1 ,5943    ,550,550,550
BEGIN DESCRIPTION:
UNT 1051 IN LATR 10.0
END DESCRIPTION:
XS GIS Cut Line= 4
      2897108.02      10060289.7      2897884.05     10060300.12
      2898368.42     10059935.54      2898842.36     10059831.37
#Sta/Elev= 30
  3865.7 1341.39  4016.2 1331.08  4096.2 1327.98  4156.2 1322.87  4186.2 1323.17
  4316.2 1315.05  4456.2  1310.6  4534.8 1310.58  4616.2 1308.04  4698.8 1308.54
  4748.8 1306.63  4757.1 1306.05  4948.7 1304.22  4992.4 1298.34  4998.4 1296.04
    5007 1297.17  5027.8 1305.05    5057 1305.02  5071.5 1306.44  5092.4 1314.61
  5106.9    1317  5227.7 1326.74  5242.3 1329.17  5250.6 1328.84  5268.6 1332.06
  5309.5 1335.41  5360.7 1342.95  5411.9 1346.92  5554.7 1353.87  5733.3 1357.45
#Mann= 4 ,-1 , 0
  3865.7     .16       0  4757.1     .09       0  5071.5     .16       0
  5733.3      .1       0
Bank Sta=4748.8,5071.5
XS Rating Curve= 0 ,0
Exp/Cntr=0.3,0.1

Type RM Length L Ch R = 1 ,5393    ,697,697,697
BEGIN DESCRIPTION:
UNT 1051 IN LATR 9.0
END DESCRIPTION:
XS GIS Cut Line= 4
       2897248.6     10060487.61      2897764.26     10060633.45
      2898399.67     10060623.04        2898945.     10060197.16
#Sta/Elev= 30
  4050.1 1330.44  4195.5 1321.88  4216.2 1322.07    4289 1317.68  4313.2 1317.93
  4434.5  1309.1    4476 1309.74  4493.4 1308.08  4585.6 1306.35  4950.2 1301.73
  4960.2 1300.81    5000 1291.78  5040.3 1300.04  5070.3 1301.16  5120.3 1300.96
  5180.3 1303.37  5256.3 1310.57  5262.7 1312.93  5283.5 1315.46  5355.8 1318.13
  5391.1 1321.94  5405.6 1321.73  5426.4 1324.82  5511.8 1327.55  5683.2 1329.11
  5718.5 1333.44  5761.9 1333.11  5768.3 1334.96  5797.2 1337.17  5913.4 1340.97
#Mann= 4 ,-1 , 0
  4050.1     .16       0  4950.2     .09       0  5070.3     .16       0
  5913.4      .1       0
Bank Sta=4960.2,5070.3
XS Rating Curve= 0 ,0
Exp/Cntr=0.3,0.1

Type RM Length L Ch R = 1 ,4696    ,1095,1095,1095
BEGIN DESCRIPTION:
UNT 1051 IN LATR 8.0
END DESCRIPTION:
XS GIS Cut Line= 4
      2897113.24     10060961.58      2897774.67     10060966.79
       2898415.3     10061425.12      2899304.67     10061674.77
#Sta/Elev= 30
  3783.4 1341.48  3838.6 1338.88  3868.6 1335.94  3888.6 1331.38  3988.6 1326.54
  4008.6 1326.41  4178.6 1315.23  4408.6 1302.17  4444.2 1298.27  4487.6 1295.77
  4502.3 1294.89  4560.2 1293.41  4632.5 1294.18  4659.6 1292.87  4932.3 1294.96
  4967.9 1292.67  4982.7  1290.5  4997.2 1286.78  5018.3 1289.87    5033 1293.95
    5119 1293.68  5175.6 1295.75  5219.8 1297.59  5350.1 1300.17  5472.2 1303.57
  5762.2 1311.22  5796.2 1311.05  5900.6 1314.66  5962.9 1318.84  6156.3 1327.17
#Mann= 5 ,-1 , 0
  3783.4     .16       0  4502.3     .09       0  5175.6     .16       0
  5350.1      .1       0  5472.2     .16       0
Bank Sta=4487.6,5175.6
XS Rating Curve= 0 ,0
Exp/Cntr=0.3,0.1

Type RM Length L Ch R = 1 ,3601    ,405,405,405
BEGIN DESCRIPTION:
UNT 1051 IN LATR 7.0
END DESCRIPTION:
XS GIS Cut Line= 4
      2897305.96     10061513.68      2897774.67     10061758.45
      2898071.55     10061560.54      2899139.24     10061925.11
#Sta/Elev= 30
  4312.5  1329.3  4349.9 1327.09    4462  1323.6  4529.7 1317.62  4587.2 1315.17
  4603.6 1312.25  4625.7 1310.24  4647.8 1309.94    4692 1306.57  4736.1 1301.35
  4774.7 1294.56  4818.8 1289.85  4855.3 1287.57  4969.5 1285.62  4999.3 1280.13
  5035.6 1286.71  5092.7 1290.52  5107.7 1290.92  5205.4  1293.7    5379 1293.89
  5522.4 1295.59  5543.5 1296.81  5810.4 1301.35  5932.2 1306.73  5963.5 1309.89
  6008.5 1311.83  6071.9  1318.6  6188.1  1322.1  6262.1 1328.12  6326.3 1329.64
#Mann= 4 ,-1 , 0
  4312.5     .16       0  4818.8     .09       0  5107.7      .1       0
  5810.4     .16       0
Bank Sta=4818.8,5092.7
XS Rating Curve= 0 ,0
Exp/Cntr=0.3,0.1

Type RM Length L Ch R = 1 ,3196    ,373,373,373
BEGIN DESCRIPTION:
UNT 1051 IN LATR 6.0
END DESCRIPTION:
XS GIS Cut Line= 4
      2897389.22     10061774.06       2897602.8     10061899.08
      2898274.67     10062180.33      2898738.15     10062768.78
#Sta/Elev= 30
  4451.1 1318.11  4501.7 1315.86  4559.8 1311.17  4769.8  1300.8  4852.1 1291.24
  4875.9 1289.03  4881.3  1289.6  4899.7 1286.56  4905.1 1286.86  4910.7 1284.89
  4964.9 1284.04  4994.4 1279.26  4997.2 1278.76  5000.4 1279.26  5019.1 1282.91
  5073.3 1285.64  5365.1 1289.41  5418.8 1290.25  5453.8 1289.23  5489.2 1290.41
    5518 1289.63  5647.6 1291.19  5665.3 1291.36  5853.7 1294.52  5909.2 1296.83
  5987.8 1302.11  6023.1 1307.65    6052 1310.09  6093.6 1317.22    6176  1321.6
#Mann= 9 ,-1 , 0
  4451.1      .1       0  4501.7     .16       0  4994.4     .07       0
  5000.4     .16       0  5365.1     .05       0  5489.2      .1       0
  5647.6     .05       0  5665.3      .1       0  5853.7     .16       0
Bank Sta=4994.4,5000.4
XS Rating Curve= 0 ,0
Exp/Cntr=0.3,0.1

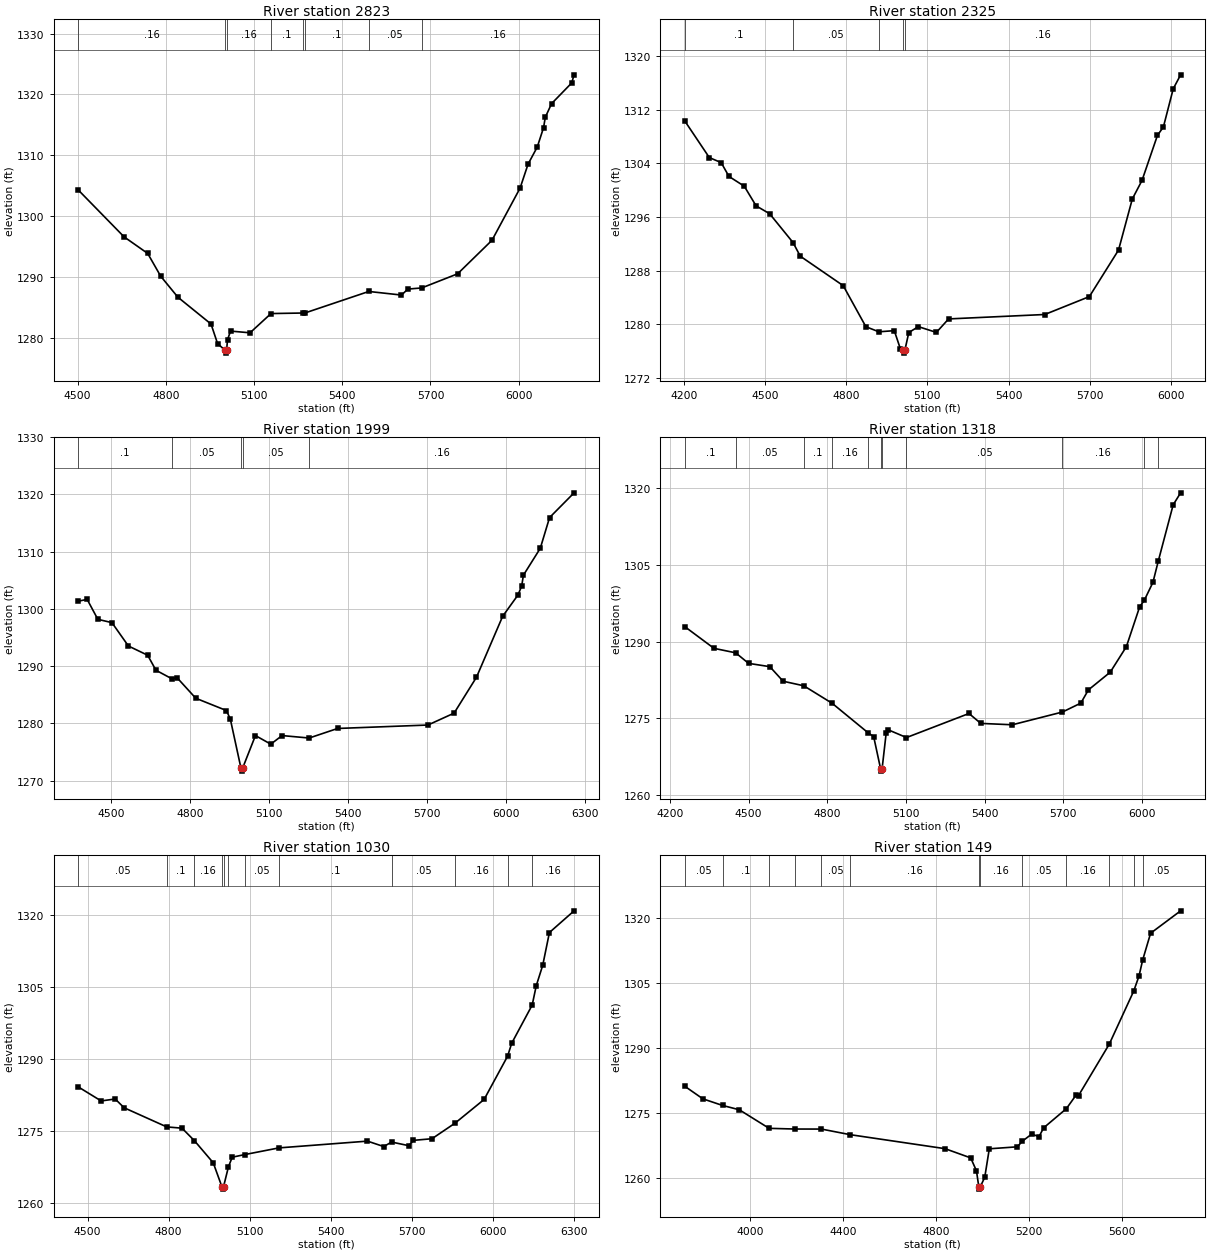
Type RM Length L Ch R = 1 ,2823    ,498,498,498
BEGIN DESCRIPTION:
UNT 1051 IN LATR 5.0
END DESCRIPTION:
XS GIS Cut Line= 4
      2897467.39     10062024.12      2897529.88     10062242.83
      2898191.34     10062586.58      2898555.21     10063199.96
#Sta/Elev= 30
  4502.4  1304.3    4658 1296.61  4738.3 1293.89  4782.5 1290.15    4841  1286.7
  4953.7 1282.29  4975.9 1279.09  5000.6 1278.01  5003.4 1277.51  5006.6 1278.01
    5010 1279.74  5020.1 1281.13  5086.4 1280.85  5157.7 1284.01  5266.5  1284.1
  5272.7  1284.1  5490.3 1287.64  5601.4 1287.05  5623.2 1288.03  5670.2 1288.22
  5792.4 1290.54  5909.3 1296.05  6004.9 1304.63  6032.1 1308.57  6063.3 1311.37
  6084.8 1314.57  6090.6 1316.26    6112  1318.5  6180.3 1321.89  6188.5 1323.23
#Mann= 8 ,-1 , 0
  4502.4     .16       0  5000.6     .07       0  5006.6     .16       0
  5157.7      .1       0  5266.5     .16       0  5272.7      .1       0
  5490.3     .05       0  5670.2     .16       0
Bank Sta=5000.6,5006.6
XS Rating Curve= 0 ,0
Exp/Cntr=0.3,0.1

Type RM Length L Ch R = 1 ,2325    ,326,326,326
BEGIN DESCRIPTION:
UNT 1051 IN LATR 4.0
END DESCRIPTION:
XS GIS Cut Line= 4
      2896998.63     10062206.37      2897425.71     10062529.29
      2897618.42     10062930.33      2898321.03     10063409.14
#Sta/Elev= 30
  4204.6 1310.31  4294.9 1304.87  4338.6 1304.12  4367.4 1302.06  4423.9  1300.6
  4467.6 1297.67  4517.5  1296.5    4604  1292.2  4630.6 1290.17  4789.3 1285.77
  4872.9 1279.65  4920.9 1278.89  4977.9 1279.06  5000.1 1276.38  5011.3 1276.21
  5014.1 1275.71  5017.3 1276.21  5031.4 1278.78  5066.7 1279.66  5133.3  1278.8
  5178.4 1280.81  5533.6 1281.47  5698.2 1284.14  5805.9 1291.08  5856.8  1298.7
  5892.7 1301.47  5949.6 1308.18  5971.6 1309.44  6007.9 1315.13  6035.2 1317.21
#Mann= 5 ,-1 , 0
  4204.6      .1       0    4604     .05       0  4920.9     .16       0
  5011.3     .07       0  5017.3     .16       0
Bank Sta=5011.3,5017.3
XS Rating Curve= 0 ,0
Exp/Cntr=0.3,0.1

Type RM Length L Ch R = 1 ,1999    ,681,681,681
BEGIN DESCRIPTION:
UNT 1051 IN LATR 3.0
END DESCRIPTION:
XS GIS Cut Line= 4
      2896930.93     10062461.61      2897029.88      10062789.7
      2897535.09     10063091.79      2898122.35     10063840.15
#Sta/Elev= 30
    4375 1301.36  4408.5 1301.67  4449.1 1298.19  4502.6 1297.61  4565.2 1293.53
  4638.3 1291.92  4669.7  1289.3  4729.7 1287.82    4750 1287.99  4820.9 1284.41
  4937.4 1282.26  4952.3 1280.75  4992.7 1272.18  4995.4 1271.68  4998.7 1272.18
  5047.6 1277.89  5105.9 1276.39  5148.7 1277.89  5251.6 1277.46  5359.6 1279.13
  5702.6 1279.73    5802 1281.81    5887 1288.08  5986.4 1298.72  6044.3 1302.42
  6058.7 1304.01  6065.1 1305.89  6129.2 1310.59  6164.5 1315.96  6257.6 1320.28
#Mann= 5 ,-1 , 0
    4375      .1       0  4729.7     .05       0  4992.7    .035       0
  4998.7     .05       0  5251.6     .16       0
Bank Sta=4992.7,4998.7
XS Rating Curve= 0 ,0
Exp/Cntr=0.3,0.1

Type RM Length L Ch R = 1 ,1318    ,355,355,355
BEGIN DESCRIPTION:
UNT 1051 IN LATR 2.0
END DESCRIPTION:
XS GIS Cut Line= 4
      2896795.51     10062784.49      2896873.63     10063237.62
      2897071.55     10063711.58      2897893.96     10064117.58
#Sta/Elev= 30
  4256.8 1292.95  4367.7 1288.72  4450.6 1287.84  4499.6 1285.78  4580.8 1285.13
  4631.5 1282.28  4710.3 1281.39  4818.3 1277.97  4955.8 1272.18  4976.8 1271.44
    5003 1265.19  5005.8 1264.69    5009 1265.19  5024.4 1272.11  5029.8 1272.83
  5101.9 1271.26  5340.3 1275.97  5385.2 1274.03  5505.6 1273.76  5696.9 1276.26
  5766.8    1278  5795.6 1280.58  5879.1 1284.06  5940.5 1289.05  5991.3 1296.87
  6008.6 1298.09  6041.8 1301.63  6062.1 1305.78    6119 1316.81  6147.4 1319.15
#Mann= 11 ,-1 , 0
  4256.8      .1       0  4450.6     .05       0  4710.3      .1       0
  4818.3     .16       0  4955.8      .1       0    5003     .07       0
    5009      .1       0  5101.9     .05       0  5696.9     .16       0
  6008.6      .1       0  6062.1     .16       0
Bank Sta=5003,5009
XS Rating Curve= 0 ,0
Exp/Cntr=0.3,0.1

Type RM Length L Ch R = 1 ,1030    ,881,881,881
BEGIN DESCRIPTION:
Mapping XS 677b8ae4
END DESCRIPTION:
XS GIS Cut Line= 4
      2896576.99     10063187.43      2896653.37     10063579.77
      2897136.01     10063996.44       2897879.1     10064281.17
#Sta/Elev= 30
  4465.9 1284.21  4550.4 1281.29  4602.1  1281.7  4635.3 1279.87  4792.9 1275.88
  4849.3 1275.62  4895.3    1273  4964.7 1268.41  4996.8 1263.42  4999.5 1262.92
  5002.8 1263.42    5021 1267.58  5034.9 1269.57  5081.4 1270.12  5207.6 1271.51
  5535.1 1272.92  5595.2 1271.79  5624.3 1272.73  5687.9 1271.97  5704.6 1273.08
  5773.6 1273.42  5859.2 1276.68  5966.3  1281.6  6053.2 1290.62  6068.3 1293.31
  6144.1 1301.27  6159.1 1305.29  6183.1 1309.56  6207.8 1316.38    6299  1320.9
#Mann= 12 ,-1 , 0
  4465.9     .05       0  4792.9      .1       0  4895.3     .16       0
  4996.8     .07       0  5002.8     .16       0    5021      .1       0
  5081.4     .05       0  5207.6      .1       0  5624.3     .05       0
  5859.2     .16       0  6053.2      .1       0  6144.1     .16       0
Bank Sta=4996.8,5002.8
XS Rating Curve= 0 ,0
Exp/Cntr=0.3,0.1

Type RM Length L Ch R = 1 ,149     ,0,0,0
BEGIN DESCRIPTION:
UNT 1051 IN LATR 1.0
END DESCRIPTION:
XS GIS Cut Line= 4
      2896497.12     10063329.76      2896767.96     10064225.61
       2897313.1     10064430.47      2897927.65     10064430.47
#Sta/Elev= 30
    3720 1281.11  3797.3 1278.22  3882.1 1276.69  3954.2 1275.69  4082.4  1271.4
  4192.2 1271.24  4307.4 1271.23  4431.7 1269.93  4839.4  1266.7  4949.6 1264.57
  4974.5 1261.57  4984.6 1257.85  4987.3 1257.35  4990.6 1257.85  5010.1 1260.09
  5029.7 1266.67  5150.6 1267.13  5171.1  1268.4  5211.9 1270.06  5243.6 1269.49
  5263.6 1271.52  5361.3 1275.95  5403.6 1279.13  5413.6 1278.98  5545.6 1290.84
  5650.8  1303.1  5673.6 1306.58  5689.6 1310.32  5723.6 1316.49  5852.8 1321.67
#Mann= 13 ,-1 , 0
    3720     .05       0  3882.1      .1       0  4082.4     .05       0
  4192.2      .1       0  4307.4     .05       0  4431.7     .16       0
  4984.6     .07       0  4990.6     .16       0  5171.1     .05       0
  5361.3     .16       0  5545.6      .1       0  5650.8     .16       0
  5689.6     .05       0
Bank Sta=4984.6,4990.6
XS Rating Curve= 0 ,0
Exp/Cntr=0.3,0.1

Chan Stop Cuts=-1
Use User Specified Reach Order=0
Composite Channel Slope=5