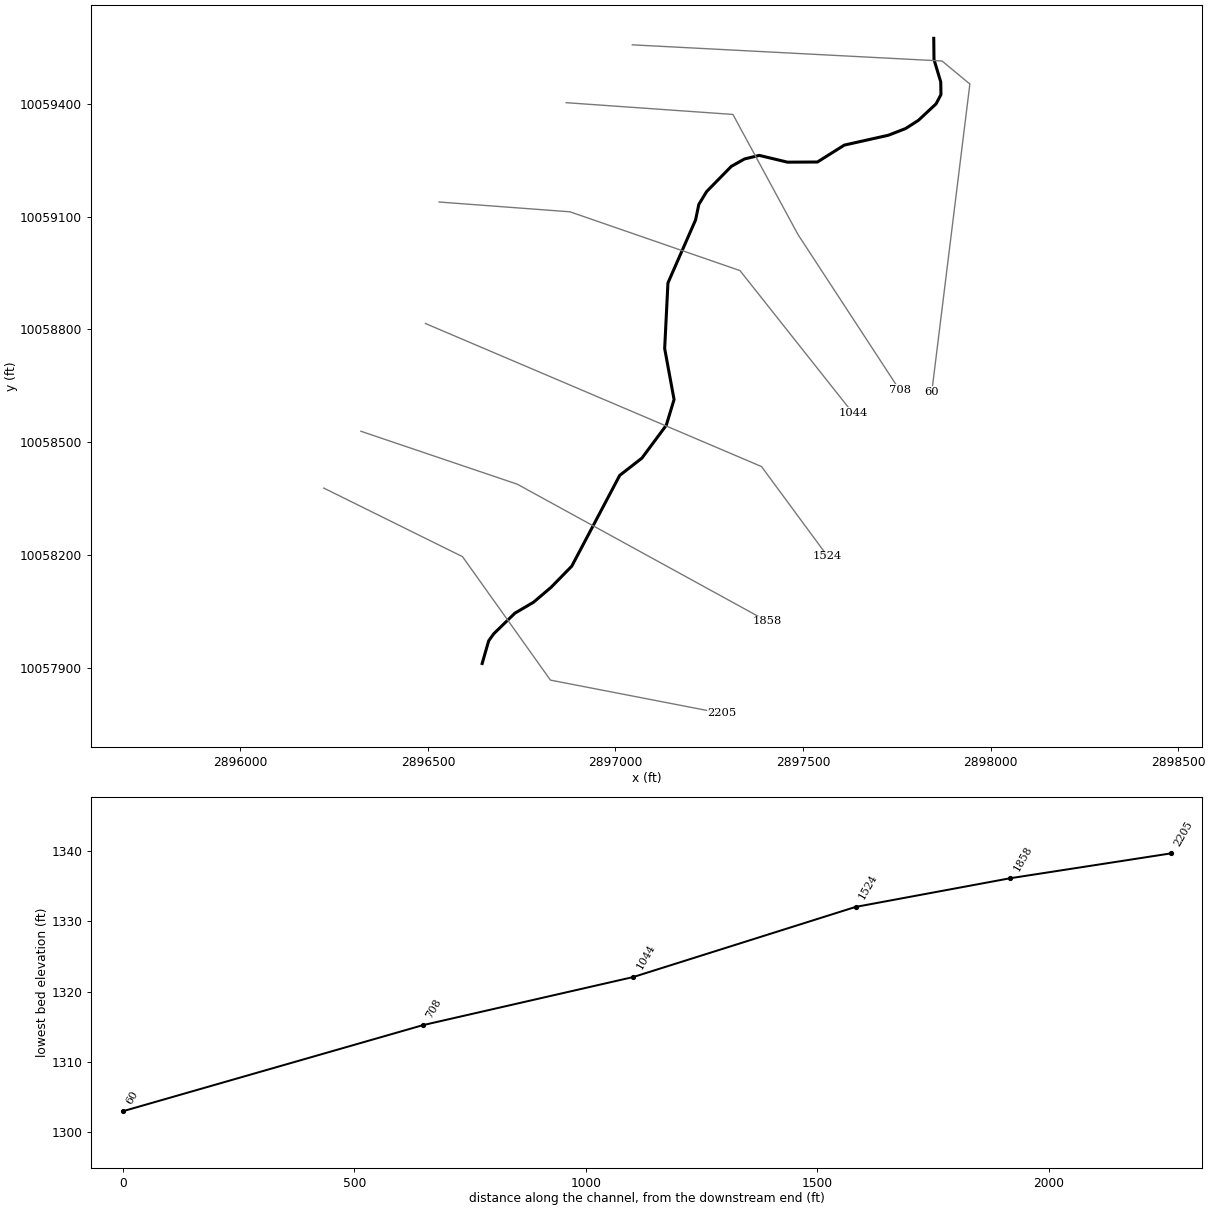
--- UNT 1052 IN LATR.prj (project) ---

Proj Title=UNT 1052 IN LATR Base Level Engineering
Current Plan=p01
Default Exp/Contr=0.3,0.1
English Units
Geom File=g01
Flow File=f01
Plan File=p01
Y Axis Title=Elevation
X Axis Title(PF)=Main Channel Distance
X Axis Title(XS)=Station
BEGIN DESCRIPTION:
UNT 1052 IN LATR
END DESCRIPTION:
DSS Export Rating Curves= 0
DSS Export Rating Curve Sorted= 0
DSS Export Volume Flow Curves= 0
DXF OffsetX= 0
DXF OffsetY= 0
DXF ScaleX= 1
DXF ScaleY= 10

--- UNT 1052 IN LATR.p01 (plan) ---

Plan Title=Multiple Run
Short Identifier=Multiple
Geom File=g01
Flow File=f01
Subcritical Flow
K Sum by GR= 0
Std Step Tol= 0.01
Critical Tol= 0.01
Num of Std Step Trials= 20
Max Error Tol= 0.3
Flow Tol Ratio= 0.001
Split Flow NTrial= 30
Split Flow Tol= 0.02
Split Flow Ratio= 0.02
Log Output Level= 0
Friction Slope Method= 1
Unsteady Friction Slope Method= 2
Unsteady Bridges Friction Slope Method= 1
Parabolic Critical Depth
Global Vel Dist=  1 , 1 , 1
Global Log Level= 0
CheckData=True
Encroach Param= -1, 0, 0, 0
BEGIN DESCRIPTION:
Multiple Run
END DESCRIPTION:

--- UNT 1052 IN LATR.f01 (steady flow) ---

Flow Title=Multiple
Program Version=4.10
Number of Profiles= 7
Profile Names=10-year,25-year,50-year,1pct_min,100-year,1pct_plu,500-year
River Rch & RM=UNT 1052 IN LATR,Reach-1         ,2205
    1089    1609    2072    1956    2645    3577    4320
Boundary for River Rch & Prof#=UNT 1052 IN LATR,Reach-1         , 1
Up Type= 0
Dn Type= 3
Dn Slope=0.0179
Boundary for River Rch & Prof#=UNT 1052 IN LATR,Reach-1         , 2
Up Type= 0
Dn Type= 3
Dn Slope=0.0179
Boundary for River Rch & Prof#=UNT 1052 IN LATR,Reach-1         , 3
Up Type= 0
Dn Type= 3
Dn Slope=0.0179
Boundary for River Rch & Prof#=UNT 1052 IN LATR,Reach-1         , 4
Up Type= 0
Dn Type= 3
Dn Slope=0.0179
Boundary for River Rch & Prof#=UNT 1052 IN LATR,Reach-1         , 5
Up Type= 0
Dn Type= 3
Dn Slope=0.0179
Boundary for River Rch & Prof#=UNT 1052 IN LATR,Reach-1         , 6
Up Type= 0
Dn Type= 3
Dn Slope=0.0179
Boundary for River Rch & Prof#=UNT 1052 IN LATR,Reach-1         , 7
Up Type= 0
Dn Type= 3
Dn Slope=0.0179
DSS Import GetInterval= 0
DSS Import GetPeak= 0
DSS Import FillOption= 0

--- UNT 1052 IN LATR.g01 (geometry) ---

Geom Title=Existing Conditions
Program Version=4.10

River Reach=UNT 1052 IN LATR,Reach-1
Reach XY= 30
       2896644.7     10057912.06      2896662.07     10057972.26
      2896675.75     10057991.22      2896731.94     10058045.78
      2896781.61     10058074.86      2896828.72     10058114.78
      2896883.57     10058170.78      2897011.35     10058412.01
      2897070.51     10058457.89      2897135.38     10058545.06
      2897156.26     10058613.67      2897131.19      10058749.2
      2897139.91     10058923.53      2897213.57     10059091.04
      2897222.19     10059132.22      2897243.17      10059166.6
      2897308.73     10059233.33      2897343.86     10059253.06
      2897383.45     10059262.56      2897458.61     10059244.57
      2897538.35     10059245.02      2897610.04     10059289.93
      2897727.47     10059316.14       2897773.4     10059333.93
      2897807.71     10059355.89      2897854.58     10059399.52
      2897867.66      10059424.2      2897867.12     10059457.75
      2897849.12     10059517.36      2897848.47     10059573.73

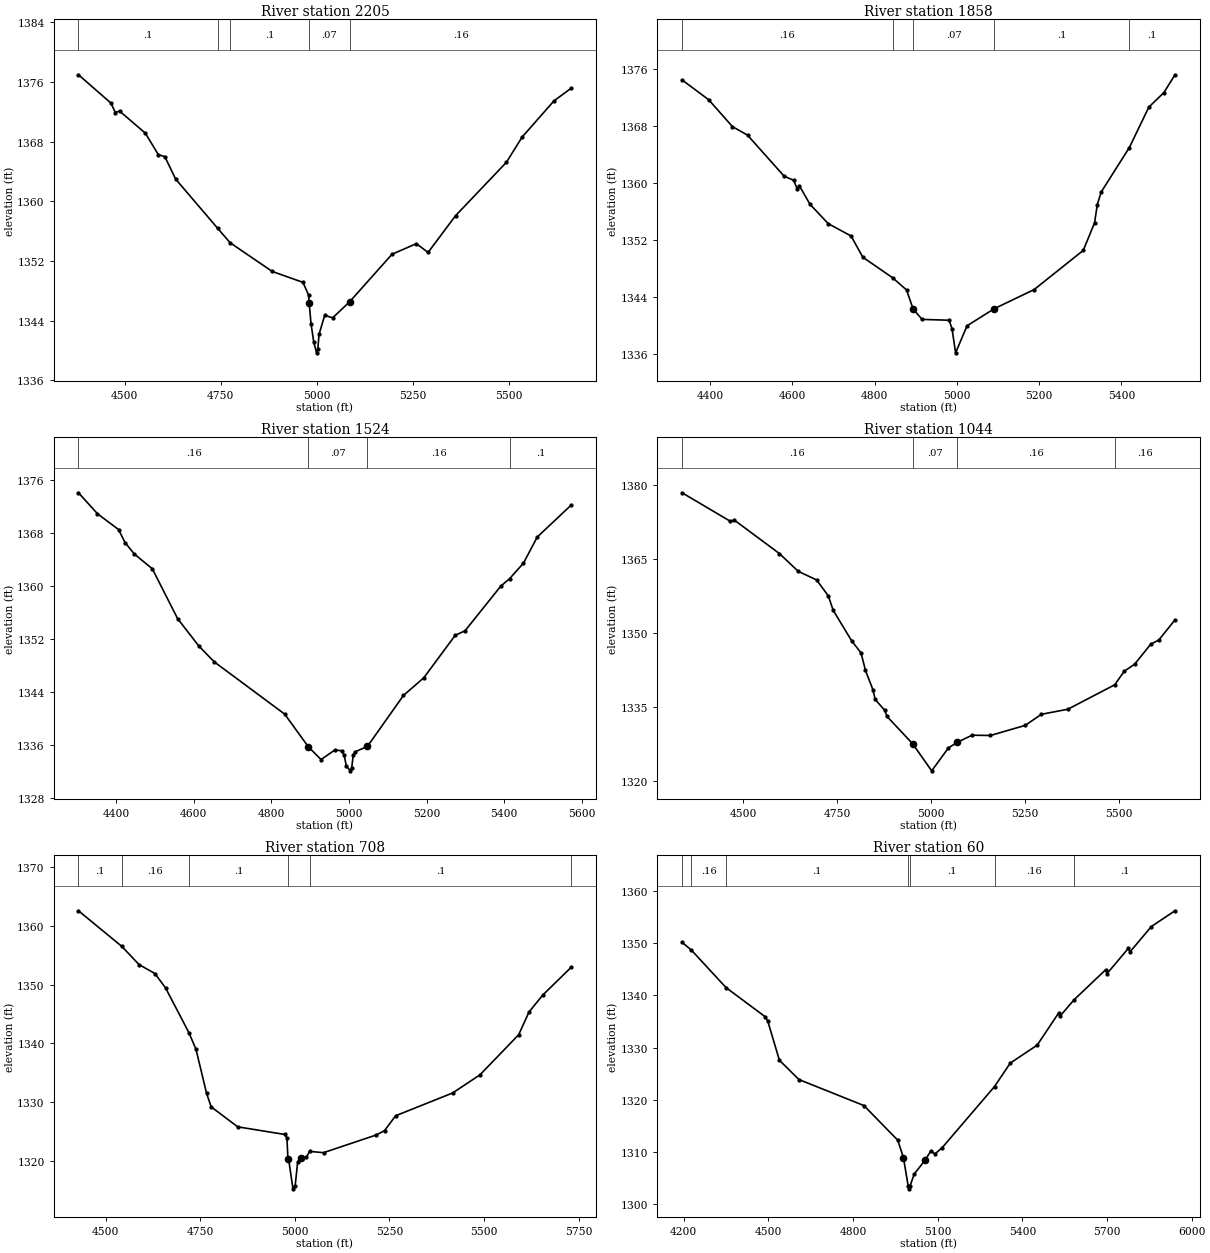
Type RM Length L Ch R = 1 ,2205    ,347,347,347
BEGIN DESCRIPTION:
UNT 1052 IN LATR 5.0
END DESCRIPTION:
XS GIS Cut Line= 4
      2896222.57     10058378.25      2896592.38     10058195.95
      2896826.76     10057867.83      2897284.26     10057779.44
#Sta/Elev= 30
  4380.4 1376.98  4464.6 1373.19  4476.2 1371.92  4487.1 1372.12  4554.2 1369.15
    4588 1366.27  4604.9    1366    4633 1362.99  4742.5 1356.38  4774.6 1354.46
  4884.1 1350.61    4964 1349.15  4978.7 1347.43    4980 1346.43  4984.9 1343.63
  4992.1 1341.13  4999.4  1339.7  5002.6  1340.2  5005.8 1342.19  5020.5 1344.72
  5041.4  1344.4  5085.6 1346.56  5195.4 1352.91  5258.8 1354.34  5289.3 1353.16
  5360.6 1358.08    5493 1365.25  5533.8 1368.63  5616.6 1373.48  5661.9  1375.2
#Mann= 5 ,-1 , 0
  4380.4      .1       0  4742.5     .16       0  4774.6      .1       0
  4978.7     .07       0  5085.6     .16       0
Bank Sta=4980,5085.6
XS Rating Curve= 0 ,0
Exp/Cntr=0.3,0.1

Type RM Length L Ch R = 1 ,1858    ,334,334,334
BEGIN DESCRIPTION:
UNT 1052 IN LATR 4.0
END DESCRIPTION:
XS GIS Cut Line= 3
      2896321.54     10058529.29      2896738.21     10058388.66
      2897404.17     10058024.47
#Sta/Elev= 30
  4331.5 1374.51  4396.3 1371.72    4454 1367.95  4490.7 1366.75  4579.8 1360.98
  4602.7 1360.41  4611.3 1359.25  4616.6 1359.66  4642.8 1357.02  4687.1 1354.31
  4742.5 1352.58  4771.2 1349.59  4843.6 1346.71  4877.6 1344.99  4893.7 1342.27
  4915.5 1340.86    4981 1340.74  4988.1 1339.54  4996.8 1336.16  5024.6 1339.96
  5090.7 1342.36  5187.8 1345.05  5307.2 1350.55  5334.8 1354.43  5341.4 1356.99
  5350.9 1358.76  5419.3    1365  5466.8 1370.69  5503.6 1372.74  5530.3 1375.23
#Mann= 5 ,-1 , 0
  4331.5     .16       0  4843.6      .1       0  4893.7     .07       0
  5090.7      .1       0  5419.3      .1       0
Bank Sta=4893.7,5090.7
XS Rating Curve= 0 ,0
Exp/Cntr=0.3,0.1

Type RM Length L Ch R = 1 ,1524    ,480,480,480
BEGIN DESCRIPTION:
UNT 1052 IN LATR 3.0
END DESCRIPTION:
XS GIS Cut Line= 3
      2896493.44     10058815.74      2897389.26     10058435.54
      2897565.34     10058197.31
#Sta/Elev= 30
  4303.6  1374.1  4352.5 1370.93  4406.8 1368.54  4423.5 1366.57  4447.2 1364.86
  4493.7 1362.61  4558.9 1355.07  4613.2 1350.96  4652.8 1348.56  4834.7 1340.64
  4895.7 1335.69  4928.3 1333.78  4963.9 1335.22  4982.1  1335.1  4987.5 1334.48
  4993.5 1332.76  5004.1 1332.07  5007.3 1332.57  5011.2 1334.44  5016.6 1334.96
  5047.8 1335.77  5140.4 1343.46  5193.1 1346.15  5273.6 1352.54  5299.2 1353.25
    5391 1359.98    5414 1361.13  5449.5 1363.46    5485 1367.41    5573 1372.27
#Mann= 4 ,-1 , 0
  4303.6     .16       0  4895.7     .07       0  5047.8     .16       0
    5414      .1       0
Bank Sta=4895.7,5047.8
XS Rating Curve= 0 ,0
Exp/Cntr=0.3,0.1

Type RM Length L Ch R = 1 ,1044    ,455,455,455
BEGIN DESCRIPTION:
UNT 1052 IN LATR 2.0
END DESCRIPTION:
XS GIS Cut Line= 4
      2896529.85     10059138.66      2896878.84     10059112.62
      2897331.96     10058956.37      2897632.76     10058577.78
#Sta/Elev= 30
  4336.7 1378.49  4465.4  1372.7  4475.7 1372.96    4596 1366.16  4646.2 1362.55
  4695.1 1360.81  4726.3 1357.57  4739.2 1354.65  4788.7 1348.42  4813.2 1346.03
  4825.2 1342.46  4844.9 1338.56  4851.1 1336.56  4876.7 1334.34  4882.3 1333.14
  4950.7 1327.58  5001.6 1322.08  5045.9 1326.71  5069.5 1327.87  5109.4 1329.31
  5157.8 1329.25  5250.6  1331.3  5293.8 1333.55  5364.3 1334.58  5489.1 1339.54
  5514.2 1342.27  5542.1 1343.72  5585.4 1347.81  5606.2 1348.59  5649.5  1352.7
#Mann= 4 ,-1 , 0
  4336.7     .16       0  4950.7     .07       0  5069.5     .16       0
  5489.1     .16       0
Bank Sta=4950.7,5069.5
XS Rating Curve= 0 ,0
Exp/Cntr=0.3,0.1

Type RM Length L Ch R = 1 ,708     ,648,648,648
BEGIN DESCRIPTION:
Mapping XS 23645ade
END DESCRIPTION:
XS GIS Cut Line= 4
      2896868.62     10059402.69       2897313.1     10059371.44
      2897486.71     10059051.99      2897757.54      10058638.8
#Sta/Elev= 30
  4427.8 1362.56  4542.4 1356.49    4588 1353.39    4630 1351.87  4658.2  1349.4
  4719.8 1341.79  4738.4 1338.98  4766.4 1331.48  4778.5 1329.17  4848.7 1325.77
  4973.2 1324.47  4978.9 1323.87 4981.48 1320.36 4983.07 1320.36  4994.8 1315.21
  5000.7 1315.77  5007.3 1319.79 5014.89 1320.51  5030.1 1320.56  5038.7 1321.59
  5075.6 1321.37  5213.6 1324.35    5237 1325.12  5266.1 1327.65  5416.8 1331.53
  5489.2 1334.62  5591.7 1341.46  5618.8 1345.31    5655 1348.19    5731 1352.97
#Mann= 6 ,-1 , 0
  4427.8      .1       0  4542.4     .16       0  4719.8      .1       0
 4981.48     .07       0  5038.7      .1       0    5731      .1       0
Bank Sta=4981.48,5014.89
XS Rating Curve= 0 ,0
Exp/Cntr=0.3,0.1

Type RM Length L Ch R = 1 ,60      ,0,0,0
BEGIN DESCRIPTION:
UNT 1052 IN LATR 1.0
END DESCRIPTION:
XS GIS Cut Line= 4
      2897044.95     10059556.46      2897870.52     10059513.49
      2897944.73     10059452.29      2897843.31     10058634.43
#Sta/Elev= 30
  4193.9 1350.14    4227 1348.65  4349.8 1341.47  4487.8 1335.92  4497.8 1335.03
  4538.9 1327.56    4608 1323.87  4838.3 1318.89  4958.4 1312.25  4978.5 1308.92
  4995.5 1303.44  4998.2 1302.94  5001.5 1303.44    5017 1305.79  5054.9 1308.41
  5075.7 1310.19  5090.1 1309.62    5116 1310.83  5301.4 1322.53  5357.2 1327.02
  5452.5 1330.45  5528.4 1336.59  5533.4 1336.01  5583.5 1339.15  5695.3 1344.89
  5700.3 1344.15  5776.2 1349.02  5781.3 1348.29  5857.2 1353.16  5940.9 1356.18
#Mann= 7 ,-1 , 0
  4193.9      .1       0    4227     .16       0  4349.8      .1       0
  4995.5     .07       0  5001.5      .1       0  5301.4     .16       0
  5583.5      .1       0
Bank Sta=4978.5,5054.9
XS Rating Curve= 0 ,0
Exp/Cntr=0.3,0.1

Chan Stop Cuts=-1
Use User Specified Reach Order=0
Composite Channel Slope=5