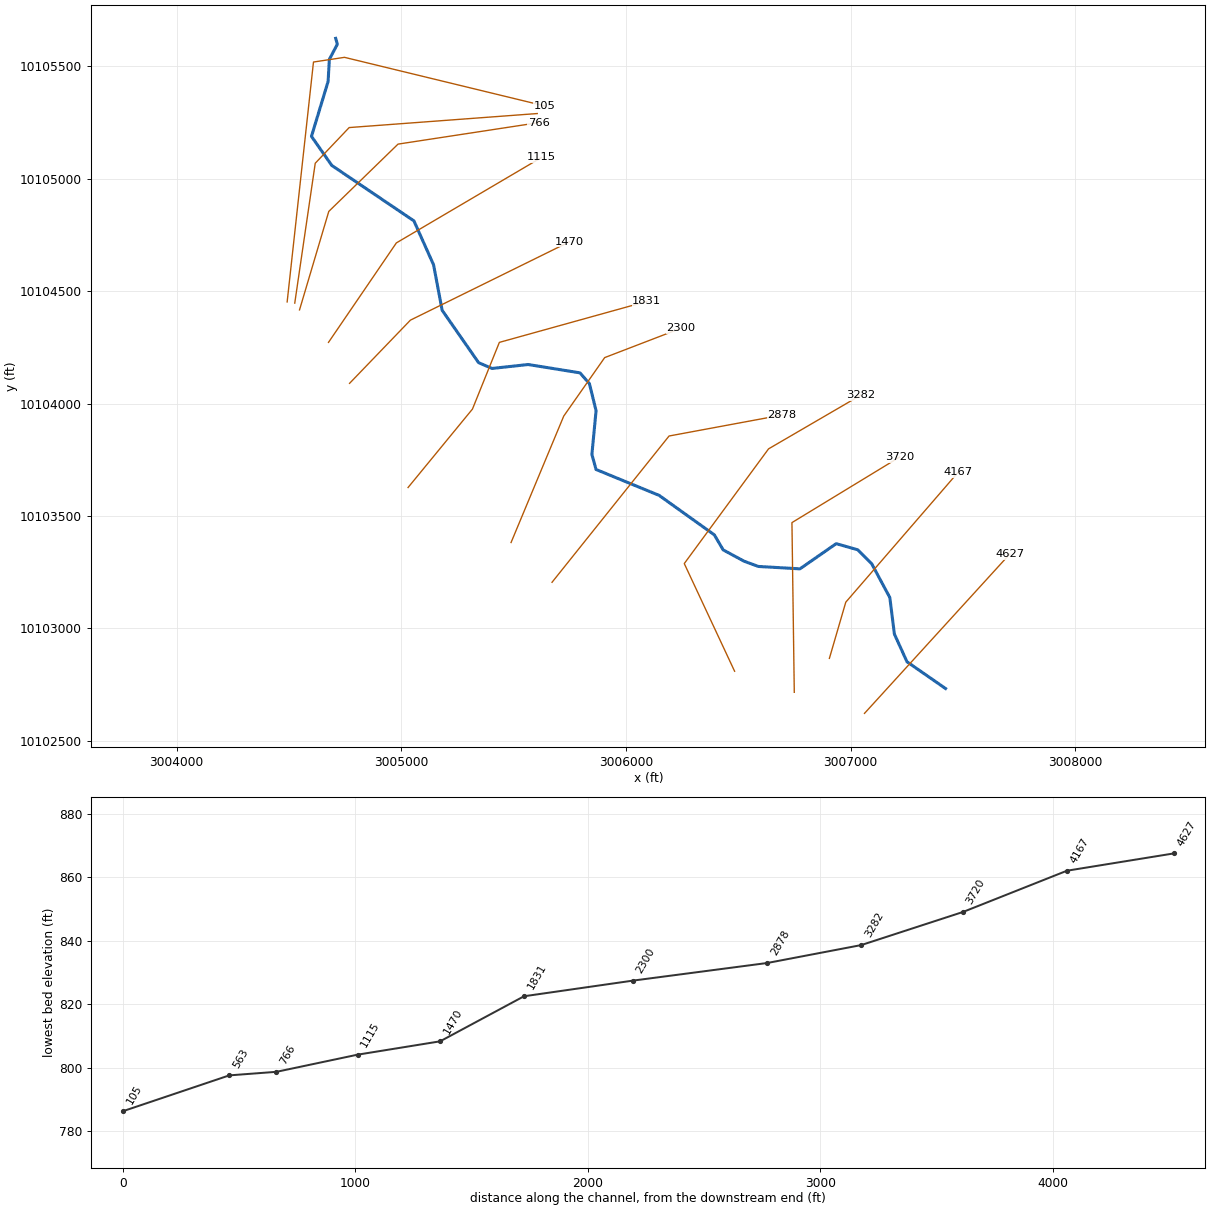
--- UNT 1054 IN LATR.prj (project) ---

Proj Title=UNT 1054 IN LATR Base Level Engineering
Current Plan=p01
Default Exp/Contr=0.3,0.1
English Units
Geom File=g01
Flow File=f01
Plan File=p01
Y Axis Title=Elevation
X Axis Title(PF)=Main Channel Distance
X Axis Title(XS)=Station
BEGIN DESCRIPTION:
UNT 1054 IN LATR
END DESCRIPTION:
DSS Export Rating Curves= 0
DSS Export Rating Curve Sorted= 0
DSS Export Volume Flow Curves= 0
DXF OffsetX= 0
DXF OffsetY= 0
DXF ScaleX= 1
DXF ScaleY= 10

--- UNT 1054 IN LATR.p01 (plan) ---

Plan Title=Multiple Run
Short Identifier=Multiple
Geom File=g01
Flow File=f01
Subcritical Flow
K Sum by GR= 0
Std Step Tol= 0.01
Critical Tol= 0.01
Num of Std Step Trials= 20
Max Error Tol= 0.3
Flow Tol Ratio= 0.001
Split Flow NTrial= 30
Split Flow Tol= 0.02
Split Flow Ratio= 0.02
Log Output Level= 0
Friction Slope Method= 1
Unsteady Friction Slope Method= 2
Unsteady Bridges Friction Slope Method= 1
Parabolic Critical Depth
Global Vel Dist=  1 , 1 , 1
Global Log Level= 0
CheckData=True
Encroach Param= -1, 0, 0, 0
BEGIN DESCRIPTION:
Multiple Run
END DESCRIPTION:

--- UNT 1054 IN LATR.f01 (steady flow) ---

Flow Title=Multiple
Program Version=4.10
Number of Profiles= 7
Profile Names=10-year,25-year,50-year,1pct_min,100-year,1pct_plu,500-year
River Rch & RM=UNT 1054 IN LATR,Reach-1         ,4627
     961    1403    1789    1670    2259    3055    3615
Boundary for River Rch & Prof#=UNT 1054 IN LATR,Reach-1         , 1
Up Type= 0
Dn Type= 3
Dn Slope=0.024
Boundary for River Rch & Prof#=UNT 1054 IN LATR,Reach-1         , 2
Up Type= 0
Dn Type= 3
Dn Slope=0.024
Boundary for River Rch & Prof#=UNT 1054 IN LATR,Reach-1         , 3
Up Type= 0
Dn Type= 3
Dn Slope=0.024
Boundary for River Rch & Prof#=UNT 1054 IN LATR,Reach-1         , 4
Up Type= 0
Dn Type= 3
Dn Slope=0.024
Boundary for River Rch & Prof#=UNT 1054 IN LATR,Reach-1         , 5
Up Type= 0
Dn Type= 3
Dn Slope=0.024
Boundary for River Rch & Prof#=UNT 1054 IN LATR,Reach-1         , 6
Up Type= 0
Dn Type= 3
Dn Slope=0.024
Boundary for River Rch & Prof#=UNT 1054 IN LATR,Reach-1         , 7
Up Type= 0
Dn Type= 3
Dn Slope=0.024
DSS Import GetInterval= 0
DSS Import GetPeak= 0
DSS Import FillOption= 0

--- UNT 1054 IN LATR.g01 (geometry) ---

Geom Title=Existing Conditions
Program Version=4.10

River Reach=UNT 1054 IN LATR,Reach-1
Reach XY= 30
        3007422.     10102731.55       3007250.4     10102850.65
      3007194.39     10102973.65      3007173.97     10103136.58
      3007093.52     10103286.52      3007031.21     10103348.98
      3006935.39     10103376.26      3006773.99     10103264.21
      3006588.93     10103274.85      3006525.57     10103298.15
      3006432.29     10103348.58        3006393.     10103415.47
      3006147.43     10103591.06      3005866.53     10103706.41
       3005848.1     10103773.63      3005866.67     10103967.89
      3005837.11     10104088.29        3005795.     10104136.45
      3005564.37     10104173.56       3005403.8     10104156.01
      3005343.85     10104181.84      3005181.62     10104415.04
      3005143.55     10104617.09      3005056.02     10104812.76
      3004690.48     10105059.54      3004600.08     10105188.89
      3004674.14      10105433.3      3004679.69     10105531.54
      3004715.31     10105598.91      3004707.87     10105625.17

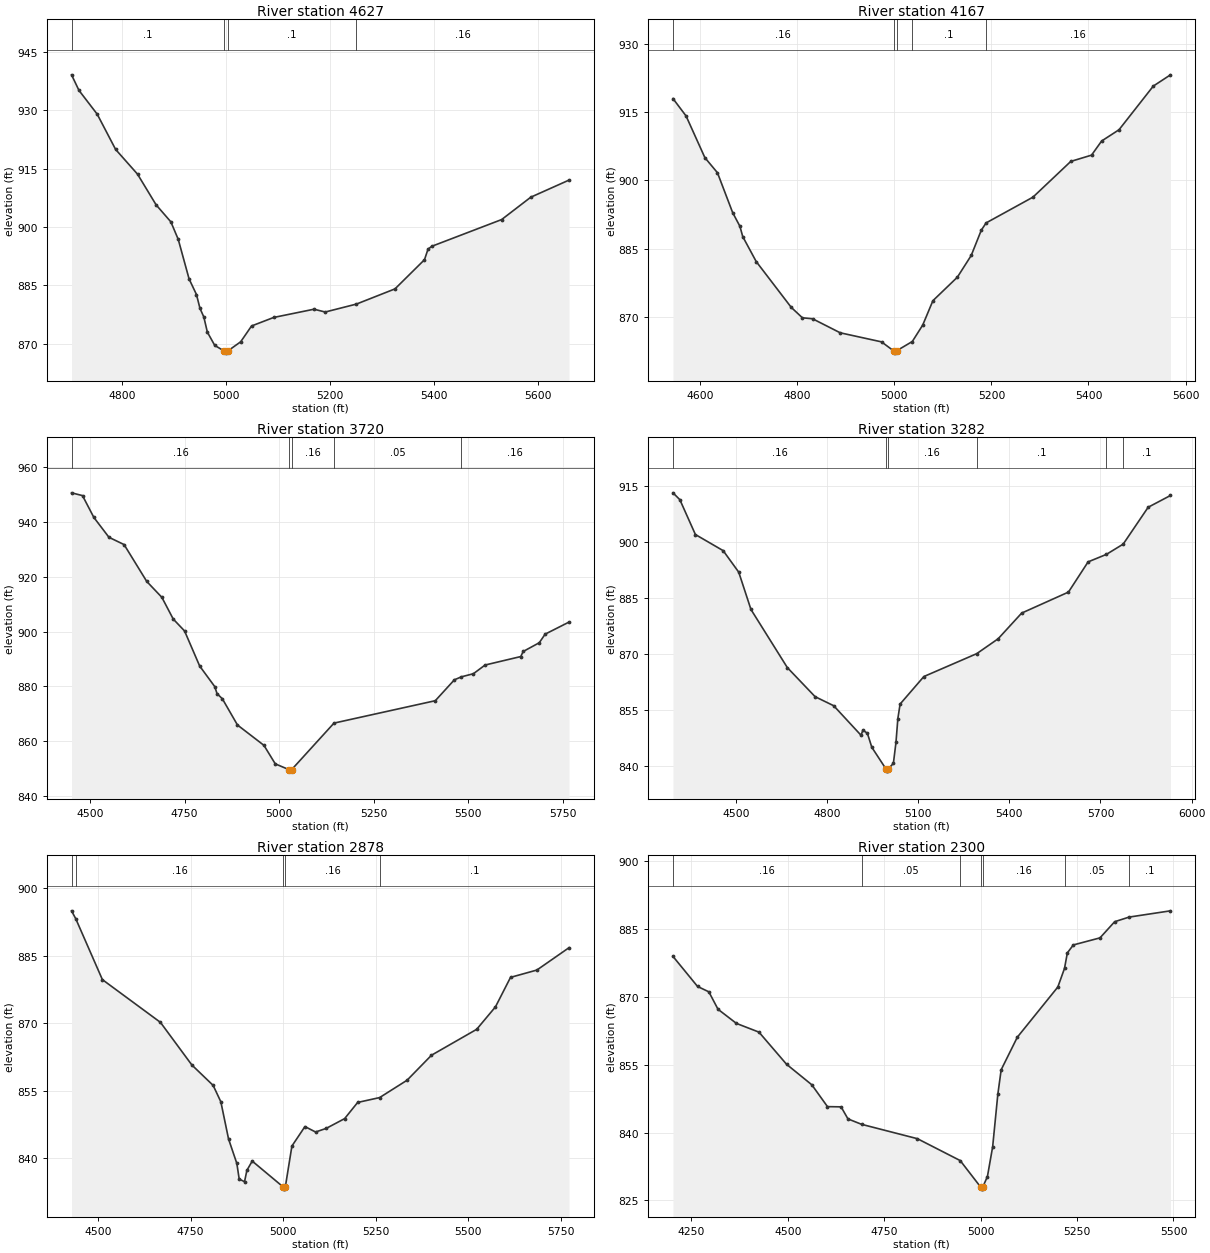
Type RM Length L Ch R = 1 ,4627    ,460,460,460
BEGIN DESCRIPTION:
UNT 1054 IN LATR 10.0
END DESCRIPTION:
XS GIS Cut Line= 2
      3007061.27     10102620.99      3007706.86     10103329.06
#Sta/Elev= 30
  4702.2  939.11  4716.5  935.11  4751.6     929  4787.1  919.93  4829.3  913.57
  4865.1  905.68  4893.5  901.31  4907.7  896.81  4928.6  886.63  4942.8  882.63
  4949.6  879.05    4957  876.85  4963.8  872.95    4978  869.55  4996.6  868.06
  4999.3  867.56  5002.6  868.06    5028  870.48  5048.9  874.54  5091.5  876.73
  5169.2  878.85  5190.8  878.13  5250.9  880.17  5325.2  884.08    5382  891.58
  5388.8   894.3  5396.1  895.03  5530.6   901.9  5586.7  907.65  5660.4  912.05
#Mann= 4 ,-1 , 0
  4702.2      .1       0  4996.6     .07       0  5002.6      .1       0
  5250.9     .16       0
Bank Sta=4996.6,5002.6
XS Rating Curve= 0 ,0
Exp/Cntr=0.3,0.1

Type RM Length L Ch R = 1 ,4167    ,447,447,447
BEGIN DESCRIPTION:
UNT 1054 IN LATR 9.0
END DESCRIPTION:
XS GIS Cut Line= 3
      3006905.03     10102865.76      3006977.95      10103115.8
      3007477.95     10103693.92
#Sta/Elev= 30
  4544.1  917.96  4571.1  914.14  4609.8     905  4635.7  901.69    4667  892.95
    4682  889.93  4687.8  887.68  4715.5  882.21  4787.7  872.15  4810.7  869.86
  4831.6  869.65  4888.6  866.57  4973.7  864.58  4998.6  862.61  5001.3  862.11
  5004.6  862.61  5037.1  864.66  5058.6  868.28  5079.5  873.61  5129.9  878.77
  5158.4  883.53  5179.2  889.08  5189.1  890.68  5285.6  896.33  5363.5  904.17
  5406.3  905.55  5427.1  908.65  5462.9  911.12  5533.5   920.7  5568.9  923.17
#Mann= 5 ,-1 , 0
  4544.1     .16       0  4998.6     .07       0  5004.6     .16       0
  5037.1      .1       0  5189.1     .16       0
Bank Sta=4998.6,5004.6
XS Rating Curve= 0 ,0
Exp/Cntr=0.3,0.1

Type RM Length L Ch R = 1 ,3720    ,438,438,438
BEGIN DESCRIPTION:
UNT 1054 IN LATR 8.0
END DESCRIPTION:
XS GIS Cut Line= 3
      3006748.79     10102714.76      3006738.37     10103469.97
      3007217.51     10103761.62
#Sta/Elev= 30
  4450.8  950.56  4479.8  949.55  4509.8   941.6  4549.8  934.35  4589.8   931.7
  4649.8  918.26  4689.8  912.46  4719.8  904.56  4749.8  900.22  4789.8  887.43
  4829.8  879.91  4835.7  877.37  4849.8   875.5  4889.8  865.94  4959.8  858.53
  4989.8  851.78  5026.8  849.63  5029.6  849.13  5032.8  849.63  5145.1  866.63
  5413.2   874.8  5463.7  882.42  5482.3   883.5  5513.9  884.63  5544.9   887.8
  5639.3  890.89  5645.6  892.73  5688.3  895.93  5703.7  899.05    5767  903.46
#Mann= 5 ,-1 , 0
  4450.8     .16       0  5026.8     .07       0  5032.8     .16       0
  5145.1     .05       0  5482.3     .16       0
Bank Sta=5026.8,5032.8
XS Rating Curve= 0 ,0
Exp/Cntr=0.3,0.1

Type RM Length L Ch R = 1 ,3282    ,404,404,404
BEGIN DESCRIPTION:
UNT 1054 IN LATR 7.0
END DESCRIPTION:
XS GIS Cut Line= 4
      3006483.15     10102808.54       3006259.2     10103287.68
       3006634.2     10103798.09      3007044.55     10104037.03
#Sta/Elev= 30
  4293.2  913.05  4315.8  911.22    4367  901.91  4458.4   897.6  4509.6  891.85
  4549.8  881.89  4669.5  866.36  4760.9  858.59  4822.1  856.17    4912  848.28
  4918.2  849.65  4932.9  848.81  4947.5  845.07  4994.7   839.2  4997.4   838.7
  5000.7   839.2  5018.5  840.78    5027  846.38  5033.2  852.75  5040.6  856.62
  5118.8  863.97  5292.7  870.08  5363.2  874.06  5440.6  880.92  5594.6  886.53
  5659.2   894.6  5719.3   896.6  5774.7  899.35  5856.9   909.2  5930.3  912.34
#Mann= 6 ,-1 , 0
  4293.2     .16       0  4994.7    .035       0  5000.7     .16       0
  5292.7      .1       0  5719.3     .16       0  5774.7      .1       0
Bank Sta=4994.7,5000.7
XS Rating Curve= 0 ,0
Exp/Cntr=0.3,0.1

Type RM Length L Ch R = 1 ,2878    ,578,578,578
BEGIN DESCRIPTION:
UNT 1054 IN LATR 6.0
END DESCRIPTION:
XS GIS Cut Line= 3
      3005670.69     10103204.38       3006191.5     10103855.39
      3006694.02     10103948.64
#Sta/Elev= 30
  4428.2  894.99  4439.6  893.23  4511.6  879.68  4668.5  870.17  4753.4  860.69
    4811  856.14  4831.8  852.49  4852.6  844.22    4875  838.78  4881.4   835.3
  4895.8  834.71  4902.2  837.24  4916.6   839.3  5000.1  833.56  5002.8  833.06
  5006.1  833.56  5023.9  842.65  5059.1  846.98  5087.9  845.77  5116.7  846.58
  5166.4  848.75  5201.6  852.35  5260.9  853.43  5335.1  857.29  5401.2  862.86
  5523.3  868.62  5574.1  873.62  5614.8  880.18    5686  881.81    5773  886.79
#Mann= 5 ,-1 , 0
  4428.2      .1       0  4439.6     .16       0  5000.1     .07       0
  5006.1     .16       0  5260.9      .1       0
Bank Sta=5000.1,5006.1
XS Rating Curve= 0 ,0
Exp/Cntr=0.3,0.1

Type RM Length L Ch R = 1 ,2300    ,469,469,469
BEGIN DESCRIPTION:
UNT 1054 IN LATR 5.0
END DESCRIPTION:
XS GIS Cut Line= 4
      3005488.35     10103381.38      3005722.75     10103943.93
      3005905.04     10104204.34      3006243.56     10104334.54
#Sta/Elev= 30
  4202.2  878.88  4265.9  872.25  4295.2  871.06    4319  867.21  4366.7  864.09
  4425.2  862.16  4496.7  855.07  4562.2  850.54  4602.8  845.72  4638.1  845.67
  4655.9  843.01  4691.4  841.81  4836.1  838.64    4947  833.81  4999.6  828.01
  5002.4  827.51  5005.6  828.01  5017.5  830.27  5031.1  836.85  5044.5  848.43
  5053.2  853.86  5095.1  861.05  5200.1  872.12  5217.4  876.23  5224.8  879.66
  5240.3  881.41  5309.4  882.97  5347.5  886.54    5385  887.56  5492.2  888.94
#Mann= 7 ,-1 , 0
  4202.2     .16       0  4691.4     .05       0    4947     .16       0
  4999.6     .07       0  5005.6     .16       0  5217.4     .05       0
    5385      .1       0
Bank Sta=4999.6,5005.6
XS Rating Curve= 0 ,0
Exp/Cntr=0.3,0.1

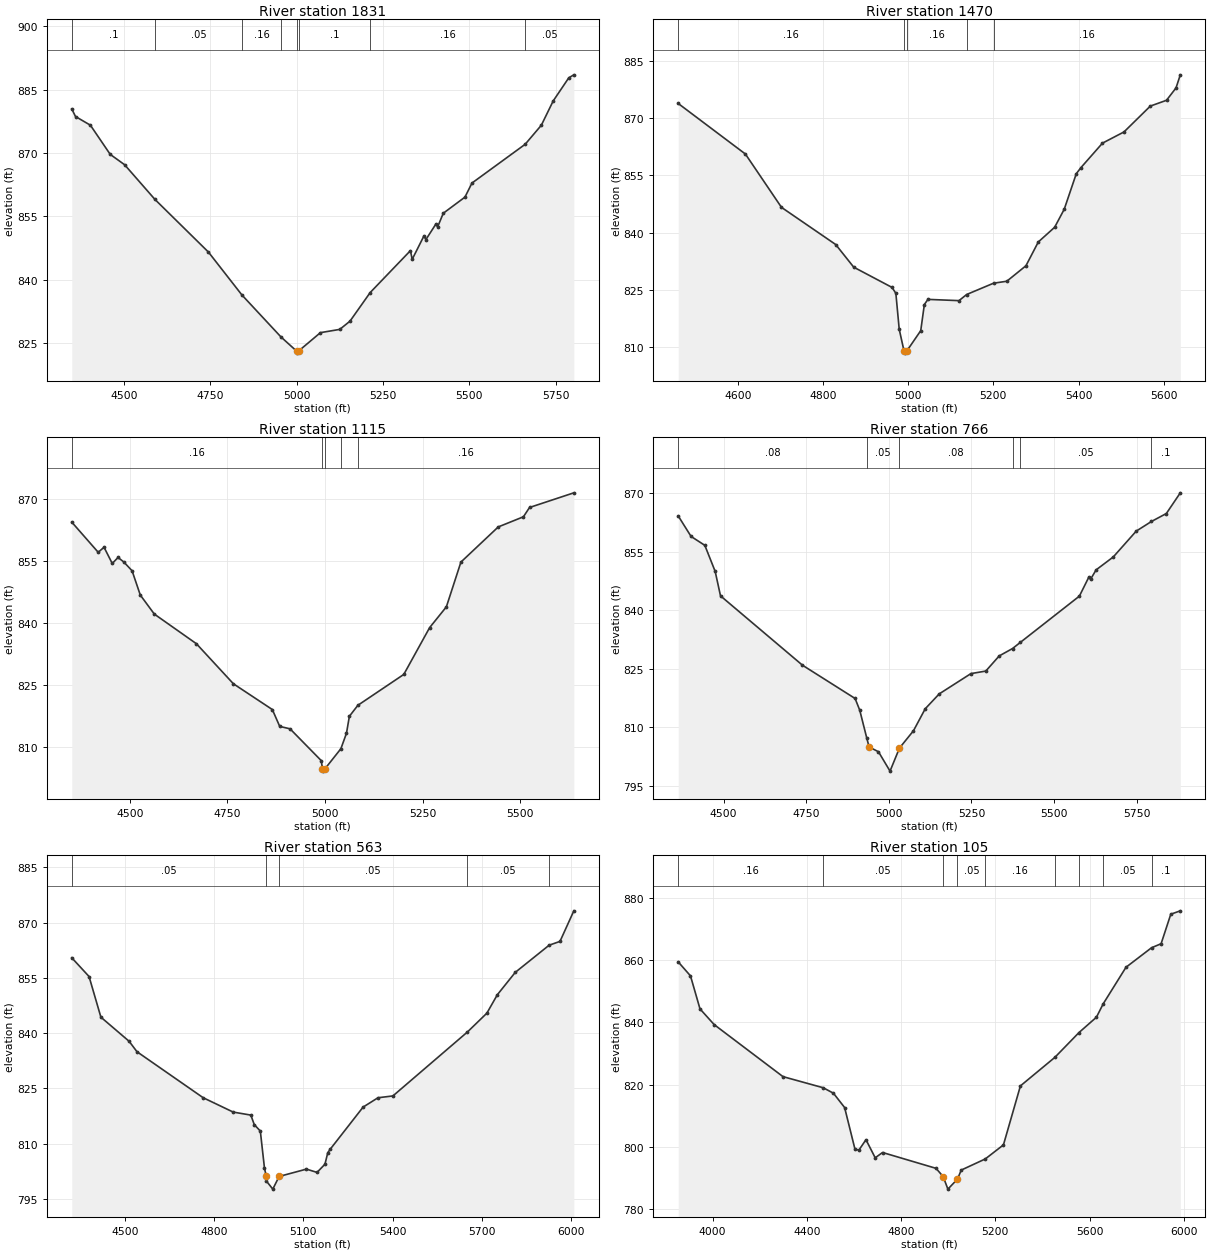
Type RM Length L Ch R = 1 ,1831    ,361,361,361
BEGIN DESCRIPTION:
UNT 1054 IN LATR 4.0
END DESCRIPTION:
XS GIS Cut Line= 4
      3005030.01     10103626.19       3005316.5     10103975.18
      3005436.29     10104272.05       3006092.5     10104454.33
#Sta/Elev= 30
  4349.5  880.41  4360.3  878.61  4403.4  876.55  4460.8  869.64  4502.4  867.19
  4590.1  858.98  4744.9  846.51  4841.8  836.35  4954.7  826.42  4999.8  823.08
  5002.6  822.58  5005.8  823.08    5069  827.43  5124.9   828.2  5154.5  830.15
    5213  836.93  5329.4  846.85  5334.5  844.79  5368.8  850.39    5374  849.45
    5403  853.14  5408.2  852.48  5424.4   855.7  5487.1  859.52  5507.4  862.85
  5661.3  872.03  5708.2  876.55  5742.4  882.29  5787.6  887.78  5802.2  888.48
#Mann= 8 ,-1 , 0
  4349.5      .1       0  4590.1     .05       0  4841.8     .16       0
  4954.7      .1       0  4999.8     .07       0  5005.8      .1       0
    5213     .16       0  5661.3     .05       0
Bank Sta=4999.8,5005.8
XS Rating Curve= 0 ,0
Exp/Cntr=0.3,0.1

Type RM Length L Ch R = 1 ,1470    ,355,355,355
BEGIN DESCRIPTION:
UNT 1054 IN LATR 3.0
END DESCRIPTION:
XS GIS Cut Line= 3
      3004769.61     10104089.75      3005040.45     10104371.01
      3005747.53     10104719.35
#Sta/Elev= 30
  4460.2  873.88  4617.9  860.62  4702.6  846.63  4829.9  836.88  4872.2  830.94
  4962.1  825.63  4971.1  824.08    4979  814.64  4990.4  808.89  4993.1  808.39
  4996.4  808.89  5029.5  814.28    5038  821.14  5046.4  822.49  5119.3  822.16
  5137.3  823.77  5200.4  826.73  5231.6  827.25  5276.5  831.31  5305.5  837.55
  5343.9  841.41  5366.4  846.14  5394.7  855.47  5405.7  857.07  5456.2  863.48
  5506.7  866.42  5568.5   873.2  5606.5  874.72  5628.8  877.96  5638.9   881.4
#Mann= 5 ,-1 , 0
  4460.2     .16       0  4990.4     .07       0  4996.4     .16       0
  5137.3      .1       0  5200.4     .16       0
Bank Sta=4990.4,4996.4
XS Rating Curve= 0 ,0
Exp/Cntr=0.3,0.1

Type RM Length L Ch R = 1 ,1115    ,349,349,349
BEGIN DESCRIPTION:
UNT 1054 IN LATR 2.0
END DESCRIPTION:
XS GIS Cut Line= 3
      3004675.85     10104272.03      3004977.95     10104714.76
       3005623.6     10105094.86
#Sta/Elev= 30
  4351.6  864.36  4419.3  857.07  4434.2  858.29  4455.2  854.37  4470.1  855.82
    4485  854.71    4506   852.6    4527  846.74  4562.9  842.14  4670.6  834.98
  4765.3   825.3    4865  819.07  4883.9     815  4910.4  814.41  4990.4  806.71
  4993.2  804.69  4995.9  804.19  4999.2  804.69  5040.5  809.61  5054.8  813.35
  5062.2  817.44    5084   820.1  5201.5  827.56  5267.6  838.86  5310.5  843.89
  5347.7   854.7  5443.3   863.2  5507.7  865.65  5523.4   867.9  5636.8  871.44
#Mann= 5 ,-1 , 0
  4351.6     .16       0  4993.2     .07       0  4999.2     .16       0
  5040.5     .05       0    5084     .16       0
Bank Sta=4993.2,4999.2
XS Rating Curve= 0 ,0
Exp/Cntr=0.3,0.1

Type RM Length L Ch R = 1 ,766     ,203,203,203
BEGIN DESCRIPTION:
Mapping XS 815b6bfa
END DESCRIPTION:
XS GIS Cut Line= 4
      3004546.92     10104416.56      3004677.13     10104854.93
      3004985.29     10105154.41      3005610.32      10105249.9
#Sta/Elev= 30
  4362.7  864.23  4401.5  858.98  4443.2  856.69  4474.5     850  4490.6  843.74
  4738.7  825.95  4897.9  817.42    4912   814.4  4933.3  807.24  4940.3  804.98
  4968.6  803.76  5003.6  798.79  5032.2  804.71  5074.6  809.15  5110.1  814.78
  5152.5   818.6  5248.4   823.8  5293.4  824.45  5333.9  828.33  5374.3  830.23
    5398  831.81  5576.6  843.67  5605.7  848.63  5610.7  848.03  5627.2   850.4
  5679.2  853.72  5748.6  860.34  5794.8  862.82  5839.7  864.85    5882  870.16
#Mann= 6 ,-1 , 0
  4362.7     .08       0  4933.3     .05       0  5032.2     .08       0
  5374.3      .1       0    5398     .05       0  5794.8      .1       0
Bank Sta=4940.3,5032.2
XS Rating Curve= 0 ,0
Exp/Cntr=0.3,0.1

Type RM Length L Ch R = 1 ,563     ,458,458,458
BEGIN DESCRIPTION:
Mapping XS 56e663fa
END DESCRIPTION:
XS GIS Cut Line= 4
      3004525.71     10104446.83      3004616.85     10105069.22
      3004767.89     10105228.07      3005604.94     10105290.46
#Sta/Elev= 30
  4321.4  860.46  4379.5  855.37  4419.3  844.34  4514.2  837.79  4540.6  834.96
    4763  822.48    4864  818.58  4923.3  817.76  4934.8  815.18  4955.2  813.43
    4969  803.47 4974.71  801.27  4975.9  799.83  4997.1  797.67  5018.4  801.11
  5110.2   803.1  5145.8  802.21  5172.4  804.43  5181.9  807.55  5190.3  808.52
  5300.6  819.93  5350.7  822.47  5400.8  822.96  5651.5  840.33  5716.7  845.43
  5751.8  850.42    5812  856.49  5925.9  863.87  5962.4   864.9    6009   873.2
#Mann= 5 ,-1 , 0
  4321.4     .05       0 4974.71    .035       0  5018.4     .05       0
  5651.5     .05       0  5925.9      .1       0
Bank Sta=4974.71,5018.4
XS Rating Curve= 0 ,0
Exp/Cntr=0.3,0.1

Type RM Length L Ch R = 1 ,105     ,0,0,0
BEGIN DESCRIPTION:
UNT 1054 IN LATR 1.0
END DESCRIPTION:
XS GIS Cut Line= 4
      3004491.85     10104452.03      3004609.04     10105519.74
      3004747.06     10105540.57      3005637.71     10105324.42
#Sta/Elev= 30
  3854.5   859.4  3906.5   854.9  3946.8   844.3  4007.1  839.24  4298.9  822.53
  4469.9  818.95    4513   817.2  4560.4   812.6  4604.1  799.29  4620.8   798.9
    4651  802.26  4690.2  796.45  4721.4  798.15  4948.3  793.06  4978.6   790.4
  4998.6  786.38  5039.3   789.6  5055.2   792.5  5157.3  796.08  5234.3   800.6
  5306.3  819.55  5452.3  828.71  5554.9   836.7  5628.8  841.62  5657.5  845.92
  5754.2  857.67  5862.7  863.95  5903.2  865.24  5944.3  874.72  5984.7  875.81
#Mann= 9 ,-1 , 0
  3854.5     .16       0  4469.9     .05       0  4978.6    .035       0
  5039.3     .05       0  5157.3     .16       0  5452.3     .05       0
  5554.9      .1       0  5657.5     .05       0  5862.7      .1       0
Bank Sta=4978.6,5039.3
XS Rating Curve= 0 ,0
Exp/Cntr=0.3,0.1

Chan Stop Cuts=-1
Use User Specified Reach Order=0
Composite Channel Slope=5