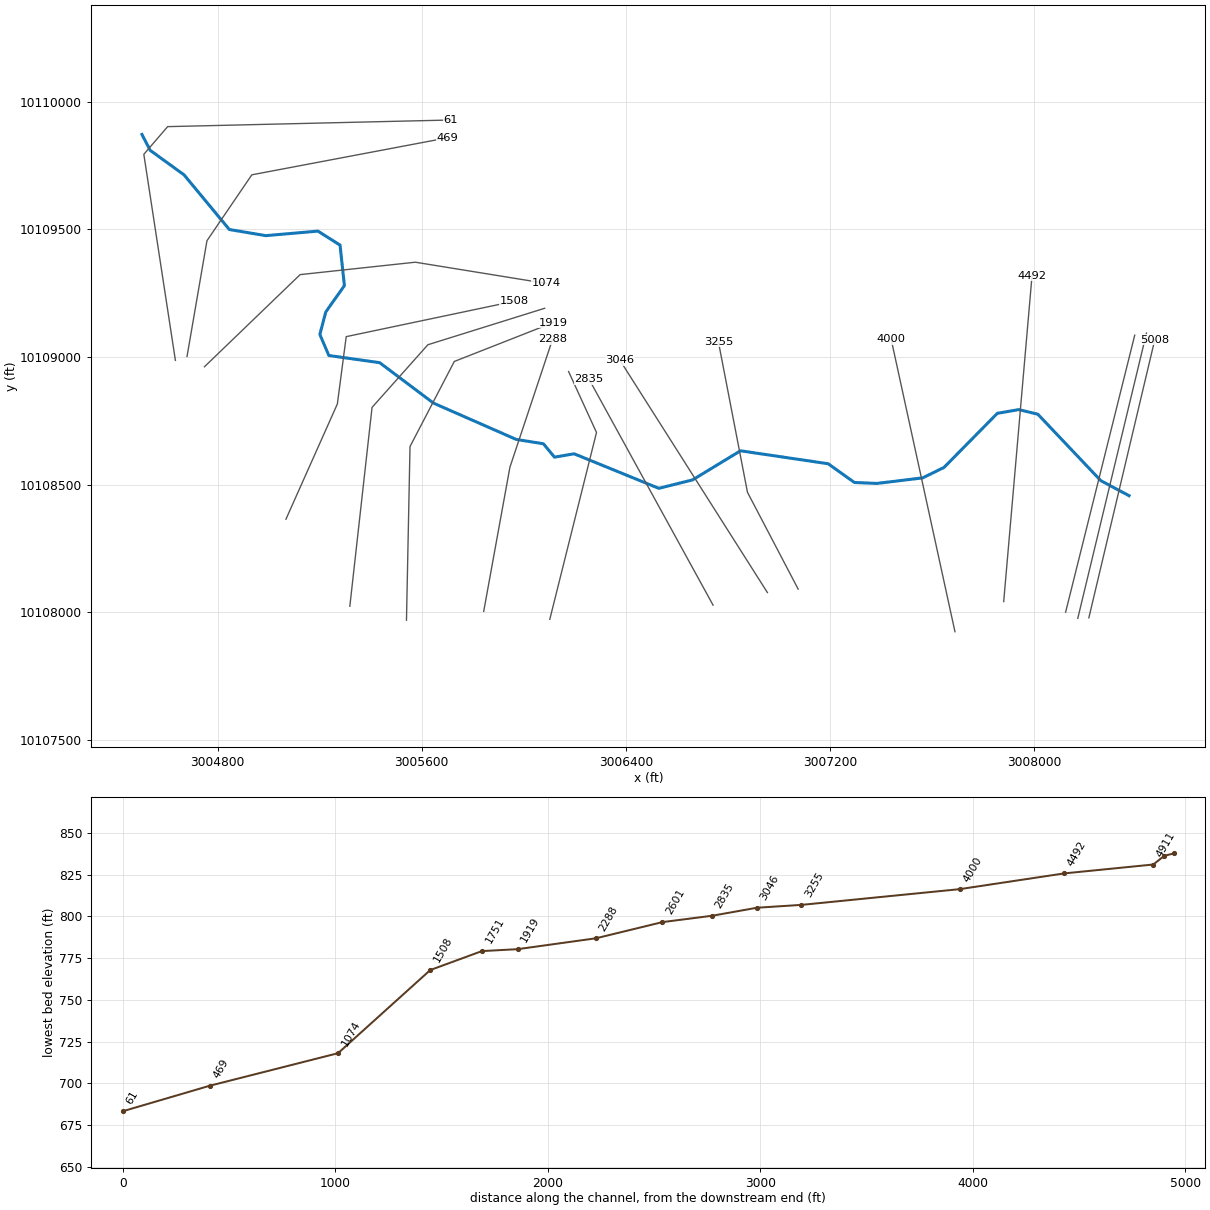
--- UNT 1055 IN LATR.prj (project) ---

Proj Title=UNT 1055 IN LATR Base Level Engineering
Current Plan=p01
Default Exp/Contr=0.3,0.1
English Units
Geom File=g01
Flow File=f01
Plan File=p01
Y Axis Title=Elevation
X Axis Title(PF)=Main Channel Distance
X Axis Title(XS)=Station
BEGIN DESCRIPTION:
UNT 1055 IN LATR
END DESCRIPTION:
DSS Export Rating Curves= 0
DSS Export Rating Curve Sorted= 0
DSS Export Volume Flow Curves= 0
DXF OffsetX= 0
DXF OffsetY= 0
DXF ScaleX= 1
DXF ScaleY= 10

--- UNT 1055 IN LATR.p01 (plan) ---

Plan Title=Multiple Run
Short Identifier=Multiple
Geom File=g01
Flow File=f01
Subcritical Flow
K Sum by GR= 0
Std Step Tol= 0.01
Critical Tol= 0.01
Num of Std Step Trials= 20
Max Error Tol= 0.3
Flow Tol Ratio= 0.001
Split Flow NTrial= 30
Split Flow Tol= 0.02
Split Flow Ratio= 0.02
Log Output Level= 0
Friction Slope Method= 1
Unsteady Friction Slope Method= 2
Unsteady Bridges Friction Slope Method= 1
Parabolic Critical Depth
Global Vel Dist=  1 , 1 , 1
Global Log Level= 0
CheckData=True
Encroach Param= -1, 0, 0, 0
BEGIN DESCRIPTION:
Multiple Run
END DESCRIPTION:

--- UNT 1055 IN LATR.f01 (steady flow) ---

Flow Title=Multiple
Number of Profiles=7
Profile Names=10-year,25-year,50-year,1pct_min,100-year,1pct_plu,500-year
River Rch & RM= UNT 1055 IN LATR,Reach-1,5008
     921    1340    1705    1590    2150    2907    3428
River Rch & RM= UNT 1055 IN LATR,Reach-1,2835
    1224    1816    2343    2213    2993    4047    4899
Boundary for River Rch & Prof#=UNT 1055 IN LATR,Reach-1,1
Up Type=0
Dn Type=3
Dn Slope=0.005
Boundary for River Rch & Prof#=UNT 1055 IN LATR,Reach-1,2
Up Type=0
Dn Type=3
Dn Slope=0.005
Boundary for River Rch & Prof#=UNT 1055 IN LATR,Reach-1,3
Up Type=0
Dn Type=3
Dn Slope=0.005
Boundary for River Rch & Prof#=UNT 1055 IN LATR,Reach-1,4
Up Type=0
Dn Type=3
Dn Slope=0.005
Boundary for River Rch & Prof#=UNT 1055 IN LATR,Reach-1,5
Up Type=0
Dn Type=3
Dn Slope=0.005
Boundary for River Rch & Prof#=UNT 1055 IN LATR,Reach-1,6
Up Type=0
Dn Type=3
Dn Slope=0.005
Boundary for River Rch & Prof#=UNT 1055 IN LATR,Reach-1,7
Up Type=0
Dn Type=3
Dn Slope=0.005

--- UNT 1055 IN LATR.g01 (geometry) ---

Geom Title=Existing Conditions
Program Version=4.10

River Reach=UNT 1055 IN LATR,Reach-1
Reach XY= 30
      3008371.71     10108456.31      3008260.84     10108515.32
      3008014.27     10108775.58      3007939.44     10108793.72
      3007855.49     10108779.15      3007646.56     10108567.07
      3007562.81     10108526.14      3007383.79     10108504.46
       3007295.6     10108508.13      3007192.73     10108581.53
      3006848.95      10108632.3      3006661.13     10108518.17
      3006529.03     10108485.22      3006197.02     10108620.59
      3006120.23     10108607.32      3006076.83     10108659.81
      3005969.82     10108676.99      3005646.01     10108819.19
      3005435.26     10108977.51      3005236.01     10109005.71
      3005200.71     10109088.11      3005223.82     10109176.21
      3005296.92     10109279.51      3005279.87     10109438.31
      3005193.21     10109493.14      3004988.83     10109475.38
      3004845.98     10109499.47      3004668.45     10109713.72
      3004535.98     10109809.62      3004503.52     10109871.94

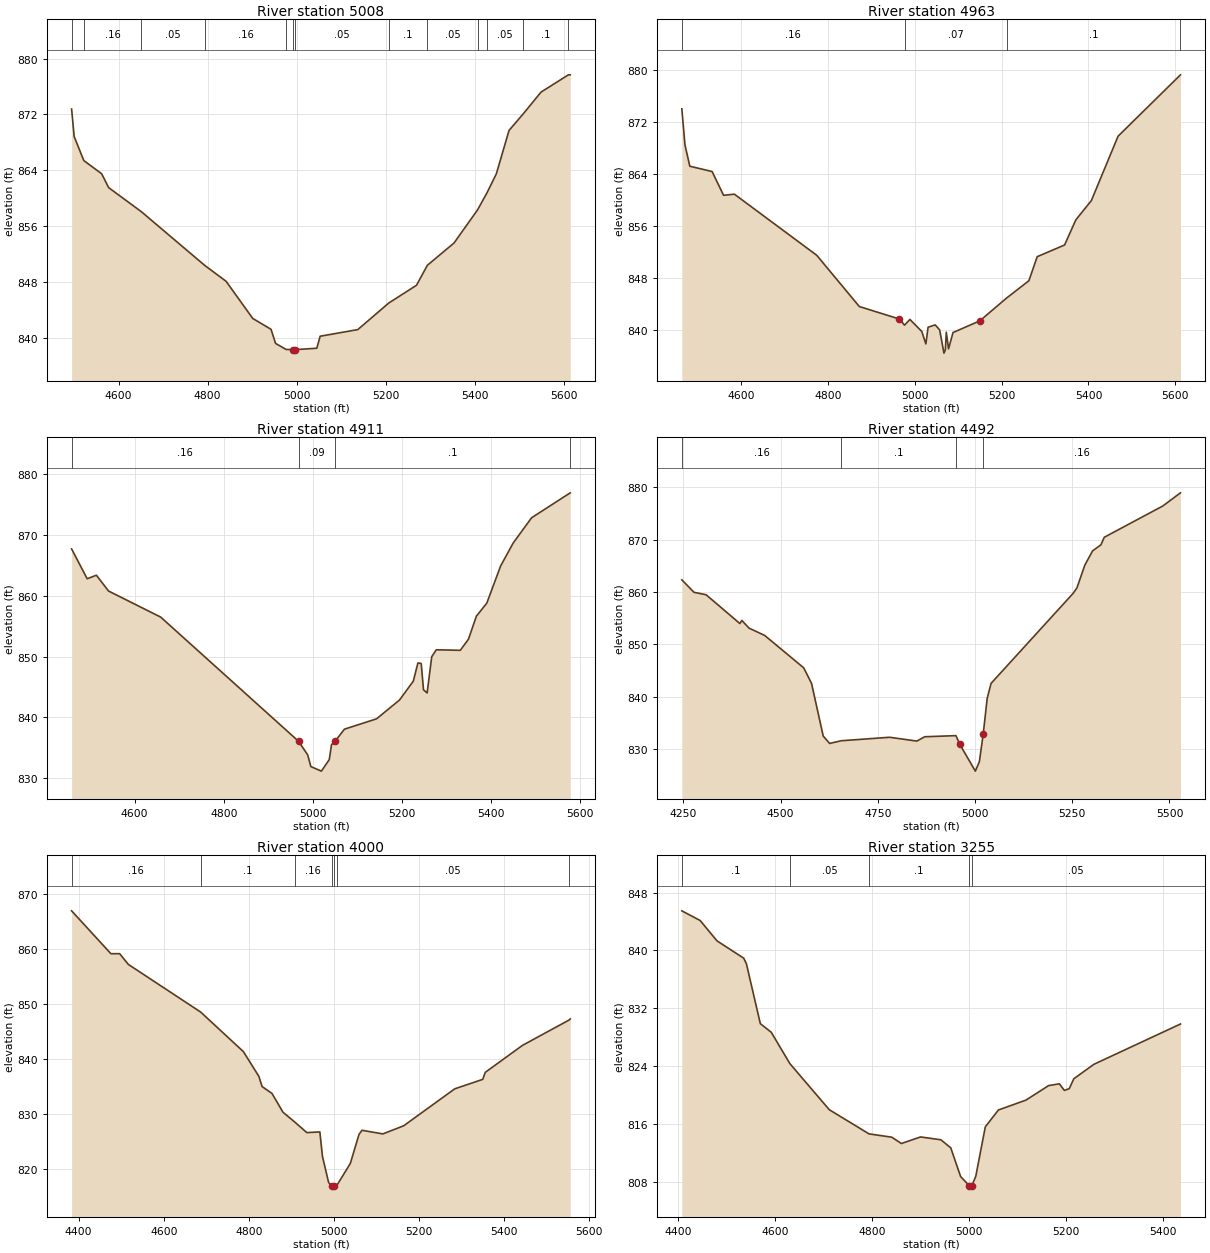
Type RM Length L Ch R = 1 ,5008    ,45,45,45
BEGIN DESCRIPTION:
UNT 1055 IN LATR 11.0
END DESCRIPTION:
XS GIS Cut Line= 2
      3008214.17     10107978.05      3008472.42     10109067.46
#Sta/Elev= 30
  4494.5  872.77  4500.3  868.83  4521.9  865.39    4562   863.5  4577.8  861.51
  4651.1  858.07  4793.5  850.37  4841.4   848.1  4901.2  842.78  4942.3  841.22
  4952.5   839.2    4976  838.34  4990.6  838.31  4993.4  837.81  4996.6  838.31
    5045  838.51  5052.6  840.23  5137.1  841.18  5206.5  844.98  5268.9  847.53
  5293.3  850.39  5353.3  853.59  5405.9  858.32    5427  860.75  5448.1  863.48
  5476.7  869.71    5508  872.04  5548.6   875.2    5610  877.67  5614.1  877.67
#Mann= 13 ,-1 , 0
  4494.5     .05       0  4521.9     .16       0  4651.1     .05       0
  4793.5     .16       0    4976     .05       0  4990.6    .035       0
  4996.6     .05       0  5206.5      .1       0  5293.3     .05       0
  5405.9      .1       0    5427     .05       0    5508      .1       0
    5610     .05       0
Bank Sta=4990.6,4996.6
XS Rating Curve= 0 ,0
Exp/Cntr=0.3,0.1

Type RM Length L Ch R = 1 ,4963    ,52,52,52
BEGIN DESCRIPTION:
Mapping XS cd087fcd
END DESCRIPTION:
XS GIS Cut Line= 2
      3008170.77     10107975.89      3008439.88     10109093.55
#Sta/Elev= 30
  4462.6  874.01  4469.8  868.46    4481  865.17  4532.4  864.35  4558.8  860.69
  4583.8  860.86  4773.6  851.45  4871.8  843.55  4964.4  841.62    4976  840.68
  4988.4  841.56  5015.8  839.71  5025.2  837.79  5030.3  840.36  5046.7  840.72
    5057  839.95  5066.9  836.37  5070.1  836.87  5072.3   839.6  5077.5  837.03
  5087.8  839.54  5149.5  841.34  5211.2  844.85  5262.7  847.52  5281.9  851.23
    5345  853.03  5370.9   856.9  5406.7  859.87  5468.4   869.8  5612.2  879.25
#Mann= 4 ,-1 , 0
  4462.6     .16       0    4976     .07       0  5211.2      .1       0
  5612.2     .05       0
Bank Sta=4964.4,5149.5
XS Rating Curve= 0 ,0
Exp/Cntr=0.3,0.1

Type RM Length L Ch R = 1 ,4911    ,419,419,419
BEGIN DESCRIPTION:
Mapping XS d28eb86f
END DESCRIPTION:
XS GIS Cut Line= 2
      3008123.04      10107999.8      3008393.88     10109085.32
#Sta/Elev= 30
  4458.6  867.73  4493.6  862.82  4514.2   863.4  4541.5   860.8  4658.5  856.51
  4967.7  836.08  4988.3  833.84  4995.4  831.91    5019  831.16  5036.7  833.05
  5041.8  835.52  5050.1   836.1  5070.7  838.06  5142.9  839.77  5194.4  842.87
  5225.3  845.97  5235.6  848.96    5243  848.88  5248.2  844.54  5256.3  844.03
  5266.6  849.98  5276.9  851.13  5330.7  851.04    5349  852.87  5366.8  856.66
  5390.2  858.81  5421.2  864.92  5449.4   868.7  5490.6  872.85  5577.4  876.96
#Mann= 4 ,-1 , 0
  4458.6     .16       0  4967.7     .09       0  5050.1      .1       0
  5577.4      .1       0
Bank Sta=4967.7,5050.1
XS Rating Curve= 0 ,0
Exp/Cntr=0.3,0.1

Type RM Length L Ch R = 1 ,4492    ,492,492,492
BEGIN DESCRIPTION:
UNT 1055 IN LATR 10.0
END DESCRIPTION:
XS GIS Cut Line= 2
      3007880.41     10108041.47       3007991.5     10109318.95
#Sta/Elev= 30
  4246.1  862.33  4277.4  859.95  4308.6  859.48  4395.3  853.99  4400.4  854.58
    4419  853.11  4459.2  851.72  4559.5  845.54  4579.6  842.58  4609.7  832.52
  4626.2  831.11  4656.3  831.63  4780.4  832.29  4850.6  831.56  4870.7  832.39
    4951   832.6    4961  830.93  5000.9  825.83  5011.2  827.63  5021.3     833
  5031.3  839.68  5041.3  842.57  5252.1  859.73  5262.2   860.8  5282.3  865.11
  5302.3  867.85  5323.8  869.01  5332.4  870.45    5483  876.42  5528.4  878.93
#Mann= 4 ,-1 , 0
  4246.1     .16       0  4656.3      .1       0    4951     .09       0
  5021.3     .16       0
Bank Sta=4961,5021.3
XS Rating Curve= 0 ,0
Exp/Cntr=0.3,0.1

Type RM Length L Ch R = 1 ,4000    ,745,745,745
BEGIN DESCRIPTION:
UNT 1055 IN LATR 9.0
END DESCRIPTION:
XS GIS Cut Line= 2
      3007689.44     10107923.36      3007439.48     10109069.01
#Sta/Elev= 30
  4383.4  866.99  4475.9  859.19  4496.4   859.2  4516.8  857.25    4687  848.58
  4787.4  841.39  4823.9  836.88  4831.3  835.04  4854.6  833.79  4880.4  830.38
    4908   828.6  4936.5  826.67  4967.2  826.79  4973.3  822.35  4987.7  817.63
  4994.9  816.89  4997.6  816.39  5000.9  816.89  5007.8  817.15  5038.8  821.05
  5059.3  826.35  5066.3  827.09  5115.4  826.43  5164.4  827.91  5284.5  834.63
  5350.3  836.35  5356.1  837.62  5443.3  842.51  5553.6  847.15    5556  847.34
#Mann= 7 ,-1 , 0
  4383.4     .16       0    4687      .1       0    4908     .16       0
  4994.9     .07       0  5000.9     .16       0  5007.8     .05       0
  5553.6     .16       0
Bank Sta=4994.9,5000.9
XS Rating Curve= 0 ,0
Exp/Cntr=0.3,0.1

Type RM Length L Ch R = 1 ,3255    ,209,209,209
BEGIN DESCRIPTION:
UNT 1055 IN LATR 8.0
END DESCRIPTION:
XS GIS Cut Line= 3
      3007075.01     10108090.27      3006876.36     10108469.72
      3006762.53     10109058.92
#Sta/Elev= 30
    4407  845.47  4444.8  844.13  4479.6  841.31  4534.6  838.92  4540.2  838.14
  4568.9  829.86  4591.5  828.66  4629.8  824.33  4711.1  817.95  4793.2   814.6
  4839.9  814.15  4859.8  813.27  4899.3  814.18  4941.2  813.79  4961.6  812.68
    4982   808.7  4999.3  807.46  5002.1  806.96  5005.3  807.46  5013.2  808.73
  5032.9  815.58  5059.9  817.91  5116.8  819.28  5163.5  821.29  5185.7  821.53
  5195.9  820.62    5206  820.86  5215.4  822.23    5257  824.24  5435.4  829.81
#Mann= 5 ,-1 , 0
    4407      .1       0  4629.8     .05       0  4793.2      .1       0
  4999.3     .07       0  5005.3     .05       0
Bank Sta=4999.3,5005.3
XS Rating Curve= 0 ,0
Exp/Cntr=0.3,0.1

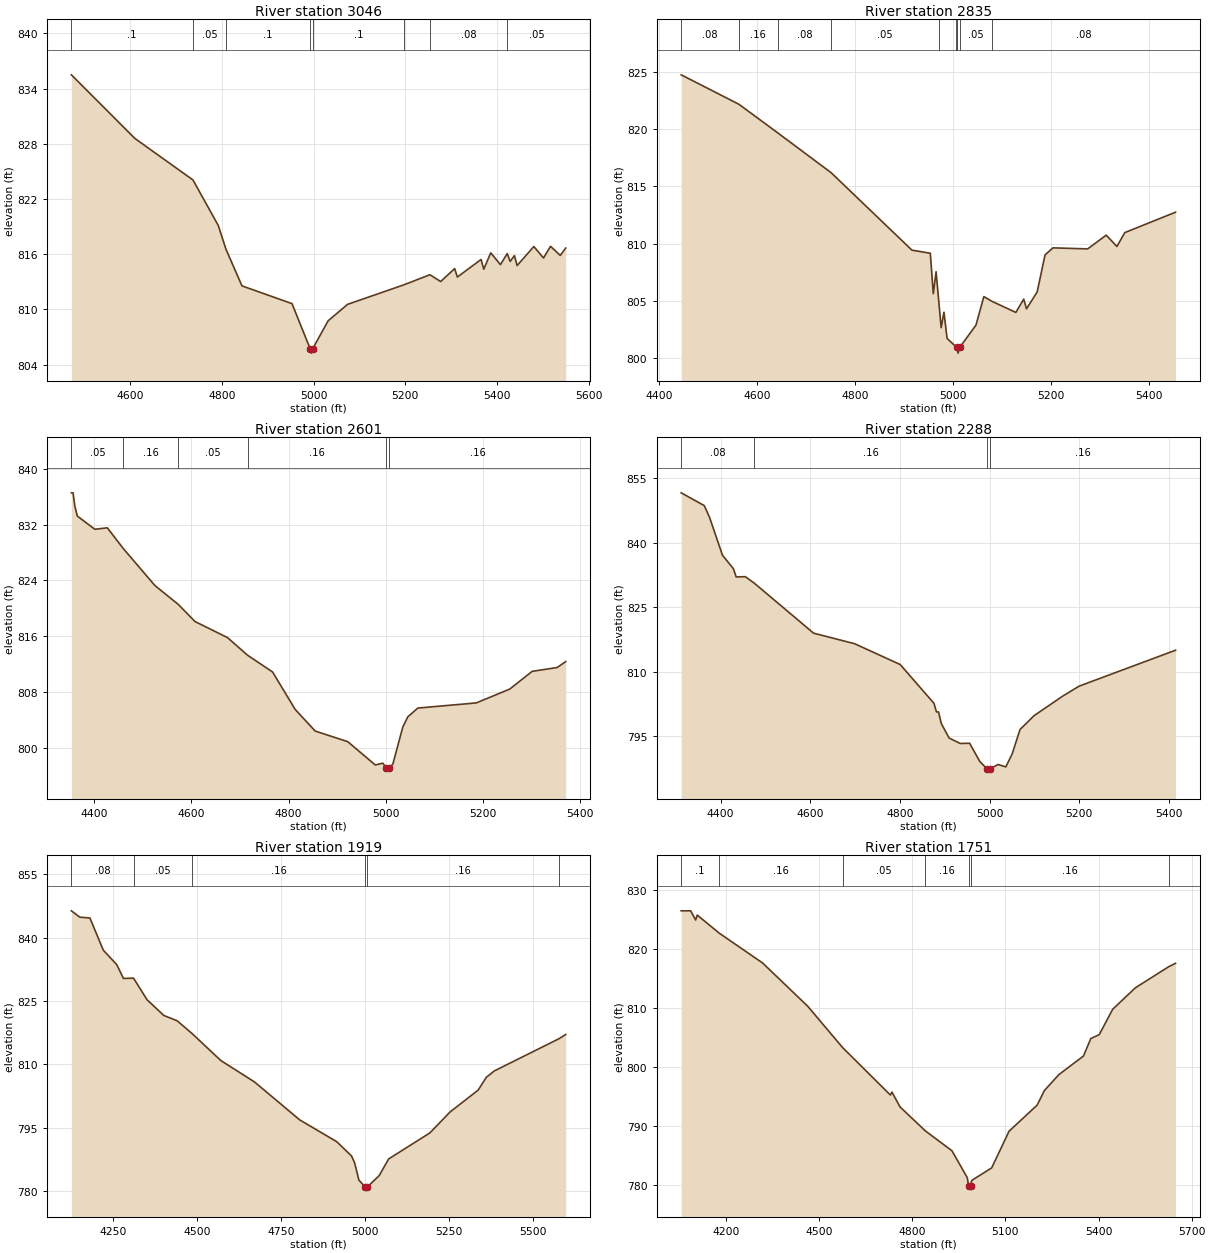
Type RM Length L Ch R = 1 ,3046    ,211,211,211
BEGIN DESCRIPTION:
UNT 1055 IN LATR 7.0
END DESCRIPTION:
XS GIS Cut Line= 2
      3006954.49     10108076.83      3006376.32     10108987.62
#Sta/Elev= 30
  4471.3   835.5  4609.8  828.59  4736.7  824.07  4791.9  819.12  4808.7  816.54
  4843.6  812.56  4952.8  810.63  4992.2  805.75  4994.9  805.25  4998.2  805.75
  5031.6  808.76    5074  810.55  5197.3  812.68  5253.7  813.77  5277.3  813.03
  5307.8  814.44  5313.7  813.52  5365.4  815.43  5371.3  814.37  5386.5  816.15
  5407.7  814.87  5422.5  816.07  5428.9  815.22  5438.2  815.85  5444.1  814.77
  5480.6  816.84  5501.7  815.59    5517  816.86  5538.2  815.87  5550.1  816.67
#Mann= 8 ,-1 , 0
  4471.3      .1       0  4736.7     .05       0  4808.7      .1       0
  4992.2     .07       0  4998.2      .1       0  5197.3     .16       0
  5253.7     .08       0  5422.5     .05       0
Bank Sta=4992.2,4998.2
XS Rating Curve= 0 ,0
Exp/Cntr=0.3,0.1

Type RM Length L Ch R = 1 ,2835    ,234,234,234
BEGIN DESCRIPTION:
UNT 1055 IN LATR 6.0
END DESCRIPTION:
XS GIS Cut Line= 2
      3006741.53     10108027.53      3006255.42     10108912.96
#Sta/Elev= 30
  4444.6  824.72  4562.6  822.15  4641.5  819.67  4751.1  816.18  4916.1  809.43
  4953.6  809.16  4959.7  805.63  4965.4  807.55  4970.4   805.2  4975.8  802.67
  4981.5  804.02  4987.9  801.73  5006.9  800.98  5007.7  800.95  5010.4  800.45
  5013.7  800.95  5046.9  802.89    5063  805.38    5080  804.96  5128.4     804
  5144.5  805.16  5150.2  804.31    5172  805.79  5188.1  809.02  5204.2  809.63
  5275.2  809.54  5313.1  810.74  5334.9  809.75    5351  810.96  5454.7  812.74
#Mann= 9 ,-1 , 0
  4444.6     .08       0  4562.6     .16       0  4641.5     .08       0
  4751.1     .05       0  4970.4      .1       0  5006.9     .05       0
  5007.7     .07       0  5013.7     .05       0    5080     .08       0
Bank Sta=5007.7,5013.7
XS Rating Curve= 0 ,0
Exp/Cntr=0.3,0.1

Type RM Length L Ch R = 1 ,2601    ,313,313,313
BEGIN DESCRIPTION:
UNT 1055 IN LATR 5.0
END DESCRIPTION:
XS GIS Cut Line= 3
      3006101.75     10107971.95      3006284.79     10108704.11
      3006175.41     10108942.96
#Sta/Elev= 30
  4352.8  836.58  4356.3  836.58  4359.8  834.71    4365  833.25  4401.1  831.35
  4426.8  831.56  4459.9  828.56  4524.8  823.27  4572.8  820.57  4607.2  818.11
  4674.2   815.8  4715.3  813.28  4766.9  810.87  4813.4   805.5  4854.6  802.39
  4921.6  800.87  4978.3  797.52  4993.7  797.78    5001  797.14  5003.8  796.64
    5007  797.14  5014.3  797.62    5035  802.98  5045.3  804.44  5065.9  805.69
  5186.2  806.43  5255.2  808.42  5301.2  810.96  5352.7  811.51  5370.2  812.36
#Mann= 6 ,-1 , 0
  4352.8     .05       0  4459.9     .16       0  4572.8     .05       0
  4715.3     .16       0    5001     .07       0    5007     .16       0
Bank Sta=5001,5007
XS Rating Curve= 0 ,0
Exp/Cntr=0.3,0.1

Type RM Length L Ch R = 1 ,2288    ,369,369,369
BEGIN DESCRIPTION:
Mapping XS 4847953c
END DESCRIPTION:
XS GIS Cut Line= 3
      3005842.79     10108003.14      3005945.48     10108567.94
      3006112.65     10109069.45
#Sta/Elev= 30
  4312.2  851.64  4363.6  848.67  4375.4  845.94  4404.3  837.12  4428.7     834
  4434.8  832.09  4455.1  832.15  4475.2  830.64  4607.6  819.01    4699  816.56
  4800.7  811.72    4876  802.71  4881.6   800.7  4886.3   800.7  4892.4  798.01
  4909.8  794.64  4934.5  793.37  4955.6  793.42  4978.4  789.16  4994.8  787.44
  4997.5  786.94  5000.8  787.44  5018.9  788.48  5036.3  787.93  5050.5  790.94
    5068  796.62  5099.6  799.85  5162.8  804.35  5199.7  806.69  5414.9  815.05
#Mann= 4 ,-1 , 0
  4312.2     .08       0  4475.2     .16       0  4994.8     .07       0
  5000.8     .16       0
Bank Sta=4994.8,5000.8
XS Rating Curve= 0 ,0
Exp/Cntr=0.3,0.1

Type RM Length L Ch R = 1 ,1919    ,168,168,168
BEGIN DESCRIPTION:
UNT 1055 IN LATR 4.0
END DESCRIPTION:
XS GIS Cut Line= 4
      3005540.13     10107968.55      3005554.02     10108649.08
      3005727.63     10108982.41      3006115.01      10109134.6
#Sta/Elev= 30
  4125.7  846.34  4150.9  844.84  4180.9  844.64  4220.9  837.01  4260.9  833.59
  4280.9  830.32  4310.9  830.39  4350.9   825.3  4400.9  821.56  4440.9  820.29
  4484.7  817.31    4571  810.87    4671  805.82  4806.2   796.8  4916.1  791.66
  4960.3  788.27  4969.5  786.66  4982.4  782.53  5001.5  780.91  5004.2  780.41
  5007.5  780.91    5043  783.64  5070.9  787.56  5193.8  793.73  5253.6  798.67
  5337.6  803.87    5362  806.91  5386.4  808.44  5578.4  816.04  5598.4  817.04
#Mann= 6 ,-1 , 0
  4125.7     .08       0  4310.9     .05       0  4484.7     .16       0
  5001.5     .07       0  5007.5     .16       0  5578.4     .08       0
Bank Sta=5001.5,5007.5
XS Rating Curve= 0 ,0
Exp/Cntr=0.3,0.1

Type RM Length L Ch R = 1 ,1751    ,243,243,243
BEGIN DESCRIPTION:
Mapping XS 674e0396
END DESCRIPTION:
XS GIS Cut Line= 4
      3005318.21     10108023.31      3005405.26     10108802.34
      3005624.03     10109047.89      3006081.69     10109190.77
#Sta/Elev= 30
  4055.9  826.51  4086.5  826.51  4102.4  824.95  4107.5  825.79  4178.1  822.73
  4317.9  817.66  4463.6   810.3  4575.7   803.3  4729.5  795.24  4734.6  795.74
  4760.7  793.22    4842  789.16    4928  785.77  4977.3  781.21  4981.8  779.76
  4984.6  779.26  4987.8  779.76  4991.5  780.73  5055.9  782.87  5111.9  789.09
  5202.3  793.52  5225.7     796  5272.5  798.71  5351.4  801.85  5375.2  804.82
  5402.4  805.49  5445.7   809.8    5519  813.45    5626  817.02  5648.1   817.6
#Mann= 7 ,-1 , 0
  4055.9      .1       0  4178.1     .16       0  4575.7     .05       0
    4842     .16       0  4981.8     .07       0  4987.8     .16       0
    5626     .08       0
Bank Sta=4981.8,4987.8
XS Rating Curve= 0 ,0
Exp/Cntr=0.3,0.1

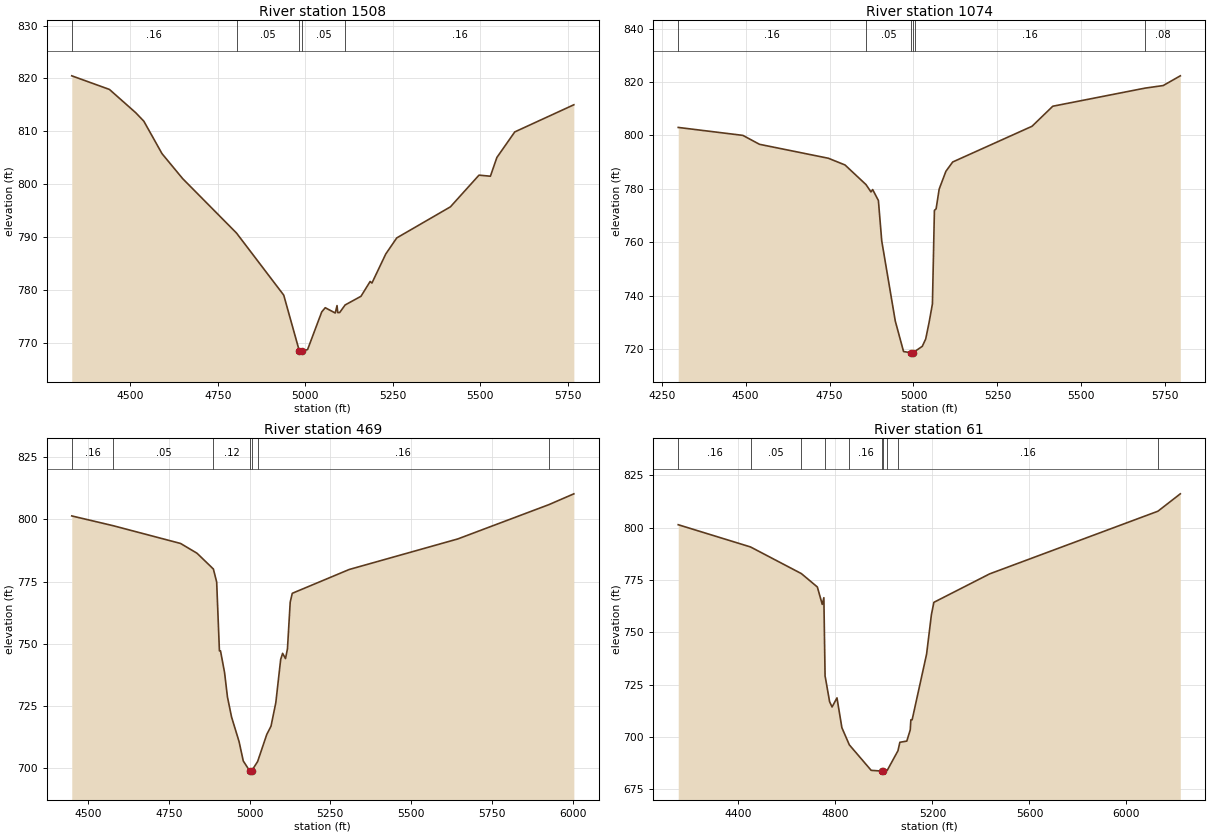
Type RM Length L Ch R = 1 ,1508    ,434,434,434
BEGIN DESCRIPTION:
UNT 1055 IN LATR 3.0
END DESCRIPTION:
XS GIS Cut Line= 4
      3005067.91     10108364.35       3005269.3     10108815.75
      3005304.02     10109079.63      3005963.61      10109218.5
#Sta/Elev= 30
  4332.7  820.49  4440.3  817.92  4515.4  813.52  4538.6  811.92  4590.6  805.78
  4649.6  801.06  4803.4  790.78  4938.3  779.05  4983.3   768.4  4986.1   767.9
  4989.3   768.4  5006.5  768.77  5046.9  775.88  5056.9  776.67  5085.5  775.67
  5090.6  777.07  5092.7  775.75    5098  775.75  5113.7  777.19    5159  778.83
  5185.2  781.63  5190.3  781.33  5229.9  786.83  5261.2  789.86  5414.5  795.73
  5496.2  801.72  5528.8  801.52  5547.3  805.06  5598.4  809.89  5767.2  815.02
#Mann= 5 ,-1 , 0
  4332.7     .16       0  4803.4     .05       0  4983.3     .04       0
  4989.3     .05       0  5113.7     .16       0
Bank Sta=4983.3,4989.3
XS Rating Curve= 0 ,0
Exp/Cntr=0.3,0.1

Type RM Length L Ch R = 1 ,1074    ,605,605,605
BEGIN DESCRIPTION:
UNT 1055 IN LATR 2.0
END DESCRIPTION:
XS GIS Cut Line= 4
      3004748.44     10108961.55      3005123.47     10109322.69
      3005574.85      10109371.3       3006088.7     10109287.98
#Sta/Elev= 30
  4299.4  802.98    4492     800  4541.4  796.66  4746.4  791.44  4796.1  788.92
  4858.6  781.57  4873.4  778.82  4878.4  779.72  4895.5  775.61  4905.5  760.43
  4945.8  730.45  4970.4  719.04  4993.1  718.57  4995.8  718.07  4999.1  718.57
  5003.1     719  5026.2     721  5036.3   723.7  5046.3  729.83  5056.4  736.89
  5062.3  771.91  5067.4   772.5  5076.5   779.9  5096.6  786.57  5116.8  790.04
  5353.1  803.42  5414.8  810.92  5689.4   817.7  5743.7  818.67  5794.6  822.31
#Mann= 6 ,-1 , 0
  4299.4     .16       0  4858.6     .05       0  4993.1     .04       0
  4999.1     .05       0  5003.1     .16       0  5689.4     .08       0
Bank Sta=4993.1,4999.1
XS Rating Curve= 0 ,0
Exp/Cntr=0.3,0.1

Type RM Length L Ch R = 1 ,469     ,408,408,408
BEGIN DESCRIPTION:
Mapping XS 85ee75a7
END DESCRIPTION:
XS GIS Cut Line= 4
      3004680.23     10109001.99      3004758.35      10109455.5
      3004934.13     10109713.75      3005701.22     10109858.93
#Sta/Elev= 30
  4450.1  801.43  4578.7  797.49  4786.7  790.37  4837.5  786.46  4888.2  780.11
  4898.4  774.88  4906.9  747.22  4910.3  747.22  4922.8  738.55  4931.7  728.75
  4944.4  720.68  4967.7  710.78  4980.7     703  5000.6  699.02  5003.3  698.52
  5006.6  699.02  5025.1  702.78  5053.3  713.63  5066.5  716.97  5081.4  726.44
  5096.4  743.78  5102.4  746.23  5111.3  744.13  5117.4  748.02  5125.9  766.81
  5132.3  770.35  5308.5  779.92  5644.4  792.19  5926.3  805.97  6003.4  810.31
#Mann= 7 ,-1 , 0
  4450.1     .16       0  4578.7     .05       0  4888.2     .12       0
  5000.6     .07       0  5006.6     .12       0  5025.1     .16       0
  5926.3     .05       0
Bank Sta=5000.6,5006.6
XS Rating Curve= 0 ,0
Exp/Cntr=0.3,0.1

Type RM Length L Ch R = 1 ,61      ,0,0,0
BEGIN DESCRIPTION:
UNT 1055 IN LATR 1.0
END DESCRIPTION:
XS GIS Cut Line= 4
      3004634.65     10108986.72      3004510.95     10109794.04
      3004604.27     10109902.55       3005714.4     10109928.57
#Sta/Elev= 30
  4151.6  801.47  4449.7  790.85  4659.5  778.11  4725.2  771.73  4745.5  763.42
  4752.1  766.61  4757.1  729.13  4758.3  728.48  4775.8  716.91  4785.9   714.4
  4806.2  718.75  4826.4  704.51  4857.1  696.31  4947.2  684.13  4991.3  683.78
  4994.1  683.28  4997.3  683.78  5013.7  684.19  5057.7  693.51  5065.5  697.53
  5094.1  698.11  5108.3  703.45  5110.8  708.27  5116.1  708.27  5175.7  739.67
  5195.7  758.64  5205.7  764.39  5435.7  777.99  6129.5  807.92  6221.9  816.23
#Mann= 10 ,-1 , 0
  4151.6     .16       0  4449.7     .05       0  4659.5     .16       0
  4758.3     .12       0  4857.1     .16       0  4991.3     .07       0
  4997.3     .16       0  5013.7     .12       0  5057.7     .16       0
  6129.5     .05       0
Bank Sta=4991.3,4997.3
XS Rating Curve= 0 ,0
Exp/Cntr=0.3,0.1

Chan Stop Cuts=-1
Use User Specified Reach Order=0
Composite Channel Slope=5