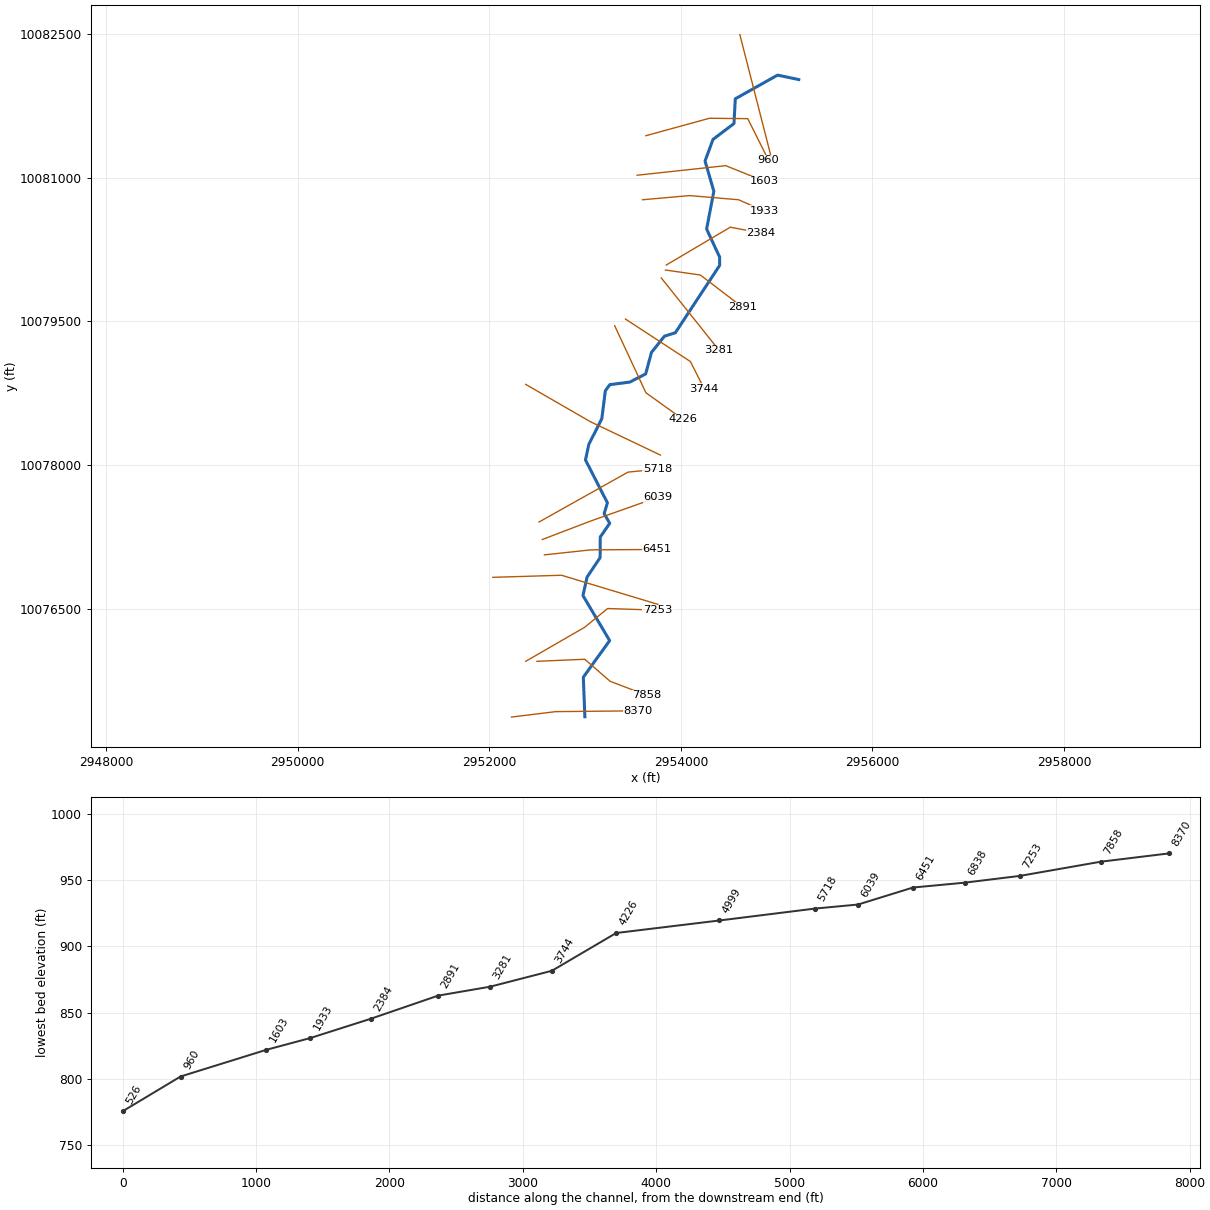
--- UNT 1056 IN LATR.prj (project) ---

Proj Title=UNT 1056 IN LATR Base Level Engineering
Current Plan=p01
Default Exp/Contr=0.3,0.1
English Units
Geom File=g01
Flow File=f01
Plan File=p01
BEGIN DESCRIPTION:
UNT 1056 IN LATR
END DESCRIPTION:

--- UNT 1056 IN LATR.p01 (plan) ---

Plan Title=Multiple Run
Short Identifier=Multiple
Geom File=g01
Flow File=f01
Subcritical Flow
K Sum by GR= 0
Std Step Tol= 0.01
Critical Tol= 0.01
Num of Std Step Trials= 20
Max Error Tol= 0.3
Flow Tol Ratio= 0.001
Split Flow NTrial= 30
Split Flow Tol= 0.02
Split Flow Ratio= 0.02
Log Output Level= 0
Friction Slope Method= 1
Unsteady Friction Slope Method= 2
Unsteady Bridges Friction Slope Method= 1
Parabolic Critical Depth
Global Vel Dist=  1 , 1 , 1
Global Log Level= 0
CheckData=True
Encroach Param= -1, 0, 0, 0
BEGIN DESCRIPTION:
Multiple Run
END DESCRIPTION:

--- UNT 1056 IN LATR.f01 (steady flow) ---

Flow Title=Multiple
Number of Profiles=7
Profile Names=10-year,25-year,50-year,1pct_min,100-year,1pct_plu,500-year
River Rch & RM= UNT 1056 IN LATR,Reach-1,8370
     953    1395    1784    1671    2260    3056    3639
River Rch & RM= UNT 1056 IN LATR,Reach-1,6451
    1643    2479    3234    3084    4171    5641    6969
Boundary for River Rch & Prof#=UNT 1056 IN LATR,Reach-1,1
Up Type=0
Dn Type=3
Dn Slope=0.005
Boundary for River Rch & Prof#=UNT 1056 IN LATR,Reach-1,2
Up Type=0
Dn Type=3
Dn Slope=0.005
Boundary for River Rch & Prof#=UNT 1056 IN LATR,Reach-1,3
Up Type=0
Dn Type=3
Dn Slope=0.005
Boundary for River Rch & Prof#=UNT 1056 IN LATR,Reach-1,4
Up Type=0
Dn Type=3
Dn Slope=0.005
Boundary for River Rch & Prof#=UNT 1056 IN LATR,Reach-1,5
Up Type=0
Dn Type=3
Dn Slope=0.005
Boundary for River Rch & Prof#=UNT 1056 IN LATR,Reach-1,6
Up Type=0
Dn Type=3
Dn Slope=0.005
Boundary for River Rch & Prof#=UNT 1056 IN LATR,Reach-1,7
Up Type=0
Dn Type=3
Dn Slope=0.005

--- UNT 1056 IN LATR.g01 (geometry) ---

Geom Title=Existing Conditions

River Reach=UNT 1056 IN LATR,Reach-1
Reach XY= 30
      2952998.47     10075373.73      2952982.38     10075786.83
      2953257.26     10076168.70      2952978.47     10076638.65
      2953021.80     10076832.35      2953157.66     10077034.26
      2953159.31     10077249.69      2953257.87     10077393.13
      2953199.57     10077493.98      2953233.92     10077606.52
      2953004.97     10078053.95      2953040.20     10078217.65
      2953175.70     10078484.87      2953212.33     10078776.95
      2953259.62     10078840.37      2953467.14     10078866.93
      2953633.34     10078951.97      2953693.43     10079176.39
      2953829.68     10079346.25      2953943.02     10079382.01
      2954405.53     10080085.16      2954404.81     10080172.00
      2954269.36     10080464.23      2954344.72     10080858.76
      2954252.82     10081174.07      2954336.03     10081399.97
      2954554.85     10081565.16      2954568.47     10081823.73
      2955009.70     10082070.85      2955231.00     10082024.63

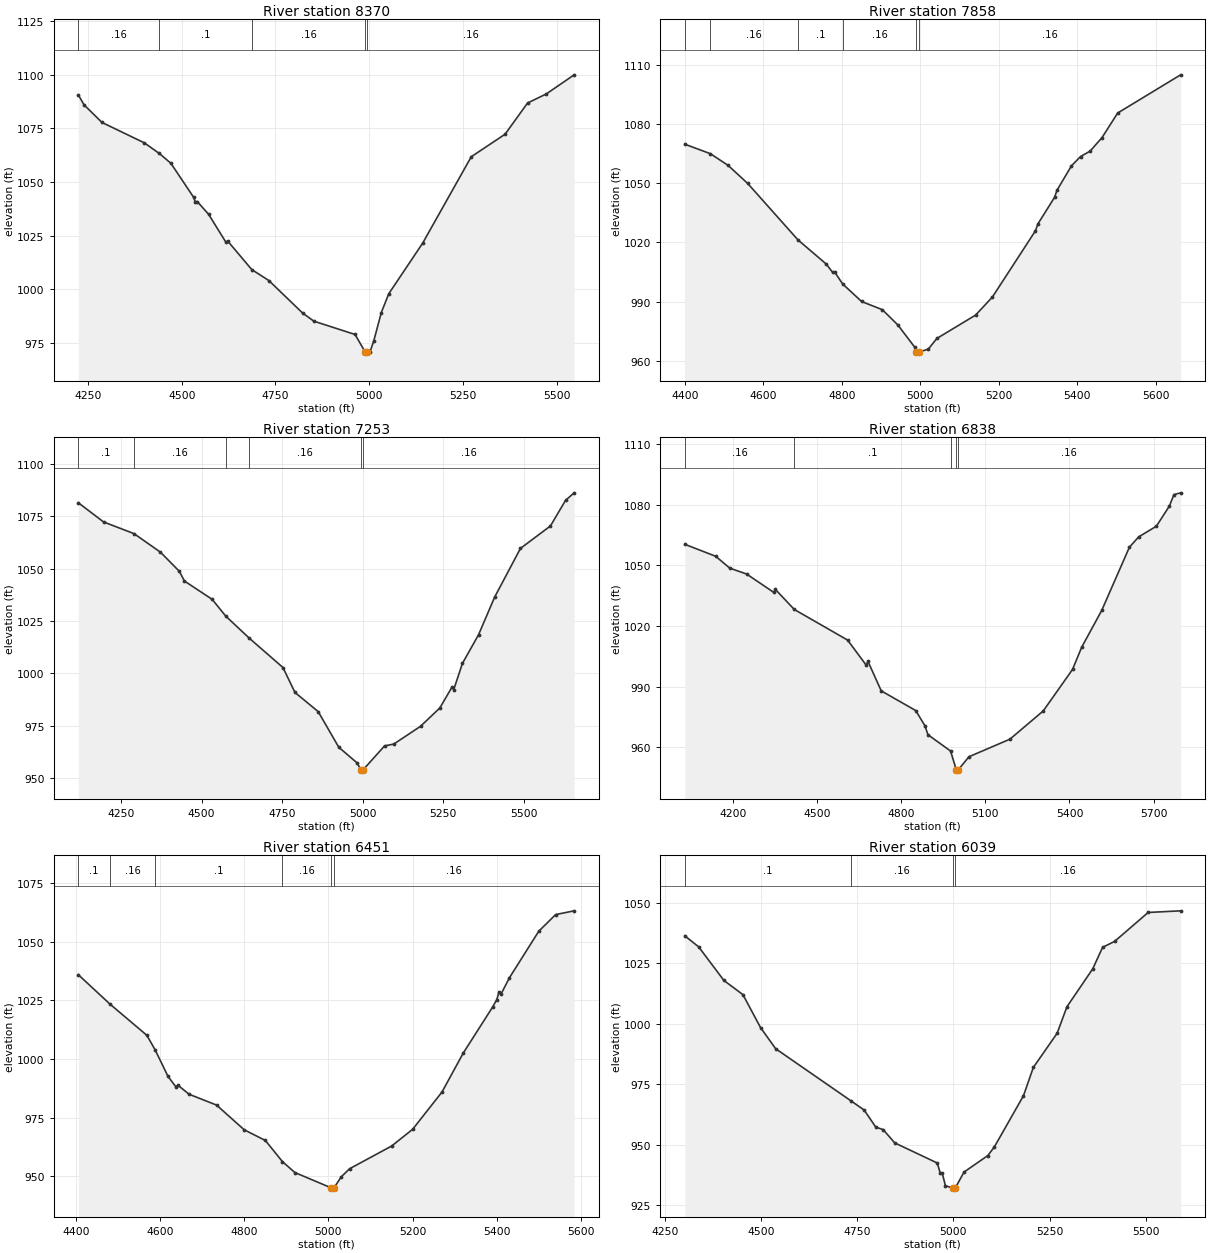
Type RM Length L Ch R = 1,8370,512,512,512
BEGIN DESCRIPTION:
UNT 1056 IN LATR 18.0
END DESCRIPTION:
XS GIS Cut Line= 3
      2952233.50     10075370.72      2952693.53     10075427.13
      2953552.91     10075435.82
#Sta/Elev= 30
  4224.0 1090.60  4239.1 1085.97  4287.1 1077.73  4400.3 1068.20  4439.9 1063.29
  4470.8 1058.72  4531.3 1042.92  4536.3 1040.55  4541.3 1040.86  4571.6 1034.91
  4617.7 1021.90  4622.7 1022.40  4686.8 1009.12  4732.4 1004.01  4822.4  988.86
  4852.4  985.07  4962.4  978.86  4989.4  970.67  4992.2  970.17  4995.4  970.67
  5002.4  970.83  5012.4  975.97  5032.4  989.11  5052.4  997.90  5142.4 1021.36
  5272.4 1061.75  5362.5 1072.23  5422.5 1086.78  5472.5 1091.02  5546.9 1099.94
#Mann=5,-1,0
  4224.0    0.16       0  4439.9     0.1       0  4686.8    0.16       0
  4989.4    0.07       0  4995.4    0.16       0
Bank Sta=4989.4,4995.4
Exp/Cntr=0.3,0.1

Type RM Length L Ch R = 1,7858,605,605,605
BEGIN DESCRIPTION:
UNT 1056 IN LATR 17.0
END DESCRIPTION:
XS GIS Cut Line= 4
      2952498.25     10075952.31      2952997.35     10075974.01
      2953262.11     10075743.97      2953648.38     10075596.41
#Sta/Elev= 30
  4400.1 1069.75  4465.3 1064.94  4510.4 1059.03  4560.5 1049.86  4688.5 1021.28
  4760.7 1009.01  4776.9 1004.82  4781.9 1005.05  4802.5  998.93  4850.7  990.05
  4903.7  985.89  4942.9  978.22  4985.6  967.05  4990.2  964.39  4993.0  963.89
  4996.2  964.39  5020.7  965.90  5042.6  971.33  5141.3  983.16  5184.1  992.30
  5293.9 1025.88  5300.0 1029.33  5342.8 1042.89  5348.7 1046.40  5385.7 1058.80
  5408.8 1063.50  5433.2 1066.24  5463.6 1073.12  5503.4 1085.54  5663.9 1104.90
#Mann=6,-1,0
  4400.1     0.1       0  4465.3    0.16       0  4688.5     0.1       0
  4802.5    0.16       0  4990.2    0.07       0  4996.2    0.16       0
Bank Sta=4990.2,4996.2
Exp/Cntr=0.3,0.1

Type RM Length L Ch R = 1,7253,415,415,415
BEGIN DESCRIPTION:
UNT 1056 IN LATR 16.0
END DESCRIPTION:
XS GIS Cut Line= 4
      2952381.00     10075952.29      2952997.35     10076308.21
      2953236.06     10076503.52      2953755.21     10076486.22
#Sta/Elev= 30
  4117.5 1081.53  4195.8 1072.36  4290.2 1066.78  4372.4 1057.92  4431.2 1048.73
  4447.0 1044.10  4533.2 1035.33  4575.0 1027.36  4648.9 1016.69  4752.9 1002.74
  4790.2  990.82  4862.3  981.66  4926.2  964.62  4983.6  957.07  4995.0  953.70
  4997.7  953.20  5001.0  953.70  5068.3  965.26  5097.0  966.14  5180.1  974.64
  5240.1  983.42  5278.3  993.52  5283.3  992.23  5310.2 1004.73  5360.2 1018.41
  5410.2 1036.41  5490.3 1059.69  5583.5 1070.44  5630.3 1082.67  5657.1 1086.28
#Mann=6,-1,0
  4117.5     0.1       0  4290.2    0.16       0  4575.0     0.1       0
  4648.9    0.16       0  4995.0    0.07       0  5001.0    0.16       0
Bank Sta=4995,5001
Exp/Cntr=0.3,0.1

Type RM Length L Ch R = 1,6838,387,387,387
BEGIN DESCRIPTION:
UNT 1056 IN LATR 15.0
END DESCRIPTION:
XS GIS Cut Line= 3
      2952038.14     10076829.04      2952754.29     10076850.75
      2953761.28     10076546.92
#Sta/Elev= 30
  4028.1 1060.48  4138.5 1054.52  4188.5 1048.65  4248.5 1045.75  4345.8 1036.61
  4350.8 1038.18  4418.6 1028.18  4608.7 1013.01  4675.9 1000.43  4680.9 1002.60
  4728.7  987.84  4851.8  978.08  4884.7  970.49  4895.2  966.12  4976.0  958.03
  4996.6  948.57  4999.4  948.07  5002.6  948.57  5041.4  955.19  5187.6  963.90
  5306.6  977.92  5410.8  998.44  5443.7 1009.52  5514.9 1027.68  5613.8 1059.05
  5646.8 1064.15  5709.9 1069.43  5756.2 1079.40  5772.6 1085.10  5796.4 1085.98
#Mann=5,-1,0
  4028.1    0.16       0  4418.6     0.1       0  4976.0    0.16       0
  4996.6    0.07       0  5002.6    0.16       0
Bank Sta=4996.6,5002.6
Exp/Cntr=0.3,0.1

Type RM Length L Ch R = 1,6451,412,412,412
BEGIN DESCRIPTION:
UNT 1056 IN LATR 14.0
END DESCRIPTION:
XS GIS Cut Line= 3
      2952576.39     10077063.42      2953058.11     10077115.50
      2953752.56     10077119.84
#Sta/Elev= 30
  4405.3 1036.00  4480.9 1023.39  4568.3 1010.11  4587.9 1003.90  4618.6  992.55
  4637.2  988.13  4642.3  988.77  4668.9  984.92  4734.0  980.31  4799.7  969.76
  4850.0  965.20  4890.7  956.15  4920.2  951.50  5007.2  944.91  5009.9  944.41
  5013.2  944.91  5030.2  949.61  5050.2  953.11  5150.2  962.81  5200.2  969.96
  5270.2  985.93  5320.2 1002.42  5390.2 1022.13  5400.2 1025.34  5405.9 1028.70
  5410.9 1027.90  5430.2 1034.65  5500.2 1054.58  5540.2 1061.68  5584.3 1063.29
#Mann=6,-1,0
  4405.3     0.1       0  4480.9    0.16       0  4587.9     0.1       0
  4890.7    0.16       0  5007.2    0.07       0  5013.2    0.16       0
Bank Sta=5007.2,5013.2
Exp/Cntr=0.3,0.1

Type RM Length L Ch R = 1,6039,321,321,321
BEGIN DESCRIPTION:
UNT 1056 IN LATR 13.0
END DESCRIPTION:
XS GIS Cut Line= 3
      2952554.66     10077224.02      2953066.79     10077419.32
      2953764.54     10077666.35
#Sta/Elev= 30
  4302.4 1036.44  4338.5 1031.85  4404.0 1017.96  4453.5 1012.07  4499.1  998.48
  4538.4  989.71  4734.9  968.04  4768.4  964.31  4798.8  957.21  4817.8  956.22
  4847.9  950.71  4958.4  942.38  4966.1  938.21  4971.4  938.15  4979.6  932.94
  4999.3  932.07  5002.1  931.57  5005.3  932.07  5027.9  938.64  5089.7  945.45
  5106.9  949.09  5182.4  970.24  5208.0  981.95  5269.8  996.09  5295.4 1007.09
  5362.5 1022.80  5388.0 1031.69  5418.9 1034.09  5506.3 1046.10  5590.7 1046.78
#Mann=4,-1,0
  4302.4     0.1       0  4734.9    0.16       0  4999.3    0.07       0
  5005.3    0.16       0
Bank Sta=4999.3,5005.3
Exp/Cntr=0.3,0.1

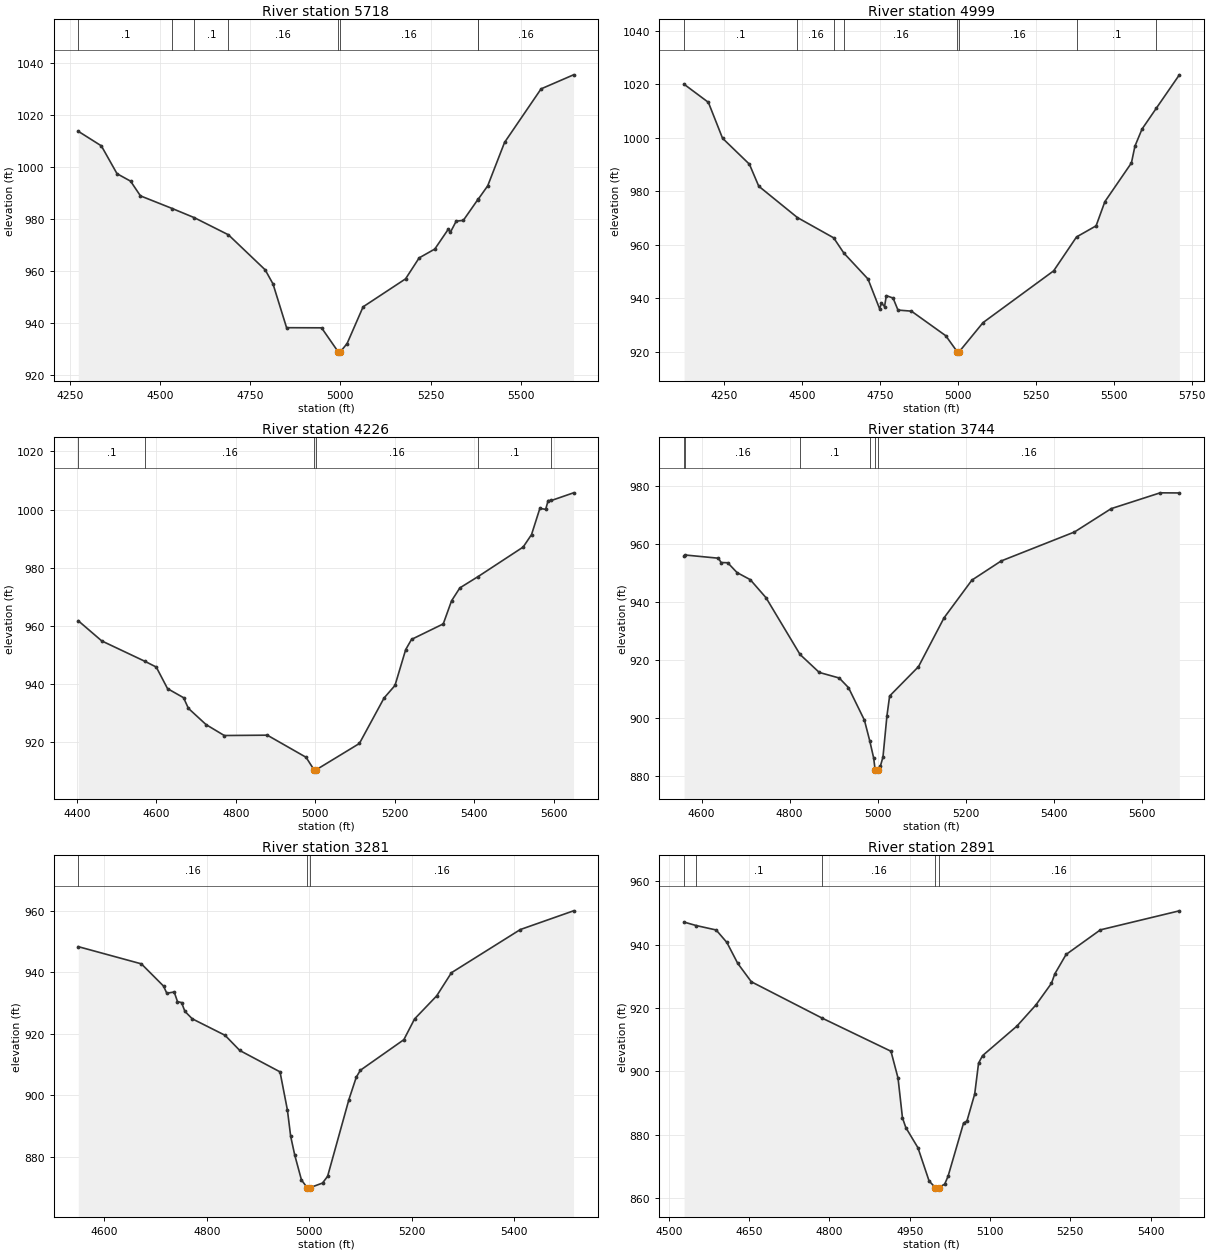
Type RM Length L Ch R = 1,5718,719,719,719
BEGIN DESCRIPTION:
UNT 1056 IN LATR 12.0
END DESCRIPTION:
XS GIS Cut Line= 3
      2952519.88     10077406.28      2953448.74     10077927.13
      2953755.23     10077957.35
#Sta/Elev= 30
  4273.4 1013.82  4337.3 1008.23  4380.7  997.53  4418.3  994.66  4445.7  989.00
  4534.0  984.13  4594.9  980.63  4689.6  974.03  4791.5  960.56  4813.2  955.13
  4850.8  938.32  4947.8  938.27  4993.9  929.04  4996.7  928.54  4999.9  929.04
  5018.6  932.24  5062.9  946.34  5180.6  957.09  5218.3  965.16  5261.7  968.56
  5299.3  976.23  5305.0  975.03  5321.0  979.28  5340.7  979.57  5380.6  987.50
  5381.9  987.69  5408.4  992.87  5455.1 1009.56  5556.3 1030.14  5646.3 1035.54
#Mann=8,-1,0
  4273.4     0.1       0  4534.0    0.16       0  4594.9     0.1       0
  4689.6    0.16       0  4993.9    0.07       0  4999.9    0.16       0
  5380.6     0.1       0  5381.9    0.16       0
Bank Sta=4993.9,4999.9
Exp/Cntr=0.3,0.1

Type RM Length L Ch R = 1,4999,773,773,773
BEGIN DESCRIPTION:
UNT 1056 IN LATR 10.0
END DESCRIPTION:
XS GIS Cut Line= 3
      2952381.05     10078842.92      2953058.11     10078452.31
      2953787.30     10078105.08
#Sta/Elev= 30
  4121.3 1020.00  4199.1 1013.25  4244.6  999.83  4330.8  990.13  4360.8  981.91
  4484.7  970.20  4601.2  962.61  4633.8  956.93  4711.4  947.22  4748.8  936.06
  4754.5  938.25  4764.5  936.94  4770.3  941.01  4791.9  940.09  4807.6  935.61
  4850.7  935.21  4961.0  926.02  4997.9  920.02  5000.7  919.52  5003.9  920.02
  5080.6  930.93  5307.2  950.27  5380.6  962.94  5443.4  967.09  5471.6  976.14
  5556.8  990.60  5568.0  996.86  5590.7 1003.24  5636.3 1010.99  5710.6 1023.53
#Mann=8,-1,0
  4121.3     0.1       0  4484.7    0.16       0  4601.2     0.1       0
  4633.8    0.16       0  4997.9    0.07       0  5003.9    0.16       0
  5380.6     0.1       0  5636.3    0.16       0
Bank Sta=4997.9,5003.9
Exp/Cntr=0.3,0.1

Type RM Length L Ch R = 1,4226,482,482,482
BEGIN DESCRIPTION:
UNT 1056 IN LATR 9.0
END DESCRIPTION:
XS GIS Cut Line= 3
      2953309.83     10079454.95      2953635.37     10078756.13
      2954021.39     10078478.54
#Sta/Elev= 30
  4403.3  961.76  4462.3  954.84  4571.2  947.81  4599.5  945.86  4627.9  938.44
  4668.2  935.32  4680.4  931.66  4724.9  926.07  4770.7  922.32  4879.0  922.44
  4976.5  914.84  4996.4  910.58  4999.2  910.08  5002.4  910.58  5110.7  919.58
  5172.8  935.21  5200.3  939.53  5227.3  951.87  5242.0  955.37  5321.8  960.69
  5342.7  968.63  5363.6  973.07  5409.6  976.97  5522.9  987.11  5544.0  991.40
  5564.9 1000.38  5579.6 1000.08  5585.8 1003.11  5594.0 1003.12  5649.7 1005.75
#Mann=6,-1,0
  4403.3     0.1       0  4571.2    0.16       0  4996.4    0.07       0
  5002.4    0.16       0  5409.6     0.1       0  5594.0    0.16       0
Bank Sta=4996.4,5002.4
Exp/Cntr=0.3,0.1

Type RM Length L Ch R = 1,3744,463,463,463
BEGIN DESCRIPTION:
UNT 1056 IN LATR 8.0
END DESCRIPTION:
XS GIS Cut Line= 3
      2953422.69     10079524.36      2954099.78     10079081.65
      2954243.02     10078799.51
#Sta/Elev= 30
  4560.2  956.01  4562.3  956.30  4638.2  955.19  4644.2  953.70  4659.3  953.62
  4680.4  950.23  4710.5  947.77  4746.3  941.53  4823.6  921.91  4867.3  915.69
  4912.7  913.76  4933.7  910.44  4969.9  899.19  4981.9  892.12  4991.0  886.05
  4994.2  882.06  4997.0  881.56  5000.2  882.06  5006.1  883.23  5012.1  886.45
  5021.1  900.68  5027.2  907.54  5092.8  917.69  5150.9  934.58  5214.2  947.62
  5280.6  954.23  5447.3  964.26  5530.7  972.33  5642.0  977.80  5685.6  977.76
#Mann=6,-1,0
  4560.2     0.1       0  4562.3    0.16       0  4823.6     0.1       0
  4981.9    0.16       0  4994.2    0.07       0  5000.2    0.16       0
Bank Sta=4994.2,5000.2
Exp/Cntr=0.3,0.1

Type RM Length L Ch R = 1,3281,390,390,390
BEGIN DESCRIPTION:
UNT 1056 IN LATR 7.0
END DESCRIPTION:
XS GIS Cut Line= 2
      2953795.94     10079954.07      2954399.24     10079198.86
#Sta/Elev= 30
  4549.1  948.37  4672.2  942.78  4715.4  935.57  4721.8  933.24  4736.3  933.63
  4742.7  930.51  4750.7  930.19  4757.1  927.35  4771.5  924.92  4835.5  919.56
  4864.3  914.62  4942.8  907.67  4957.2  895.30  4963.6  886.73  4971.6  880.58
  4984.7  872.51  4995.8  870.05  4998.6  869.55  5001.8  870.05  5025.8  871.53
  5035.7  873.73  5077.3  898.68  5091.7  905.97  5099.7  908.20  5184.5  918.13
  5205.4  924.87  5248.6  932.38  5277.4  939.90  5411.9  953.94  5515.7  960.02
#Mann=3,-1,0
  4549.1    0.16       0  4995.8    0.07       0  5001.8    0.16       0
Bank Sta=4995.8,5001.8
Exp/Cntr=0.3,0.1

Type RM Length L Ch R = 1,2891,507,507,507
BEGIN DESCRIPTION:
UNT 1056 IN LATR 6.0
END DESCRIPTION:
XS GIS Cut Line= 3
      2953839.32     10080036.52      2954203.95     10079984.43
      2954646.62     10079645.91
#Sta/Elev= 30
  4528.3  947.12  4550.7  946.04  4588.2  944.63  4608.2  940.69  4628.5  934.09
  4653.9  928.28  4786.5  916.78  4914.9  906.34  4928.1  897.86  4936.4  885.30
  4942.7  882.22  4965.3  875.87  4986.2  865.35  4997.8  863.30  5000.5  862.80
  5003.8  863.30  5015.3  864.37  5021.6  866.86  5050.6  883.68  5056.9  884.31
  5071.4  892.83  5078.6  902.56  5086.0  904.94  5150.4  914.30  5185.7  920.94
  5214.8  927.78  5221.1  930.76  5242.2  936.90  5306.3  944.67  5453.9  950.68
#Mann=5,-1,0
  4528.3    0.16       0  4550.7     0.1       0  4786.5    0.16       0
  4997.8    0.07       0  5003.8    0.16       0
Bank Sta=4997.8,5003.8
Exp/Cntr=0.3,0.1

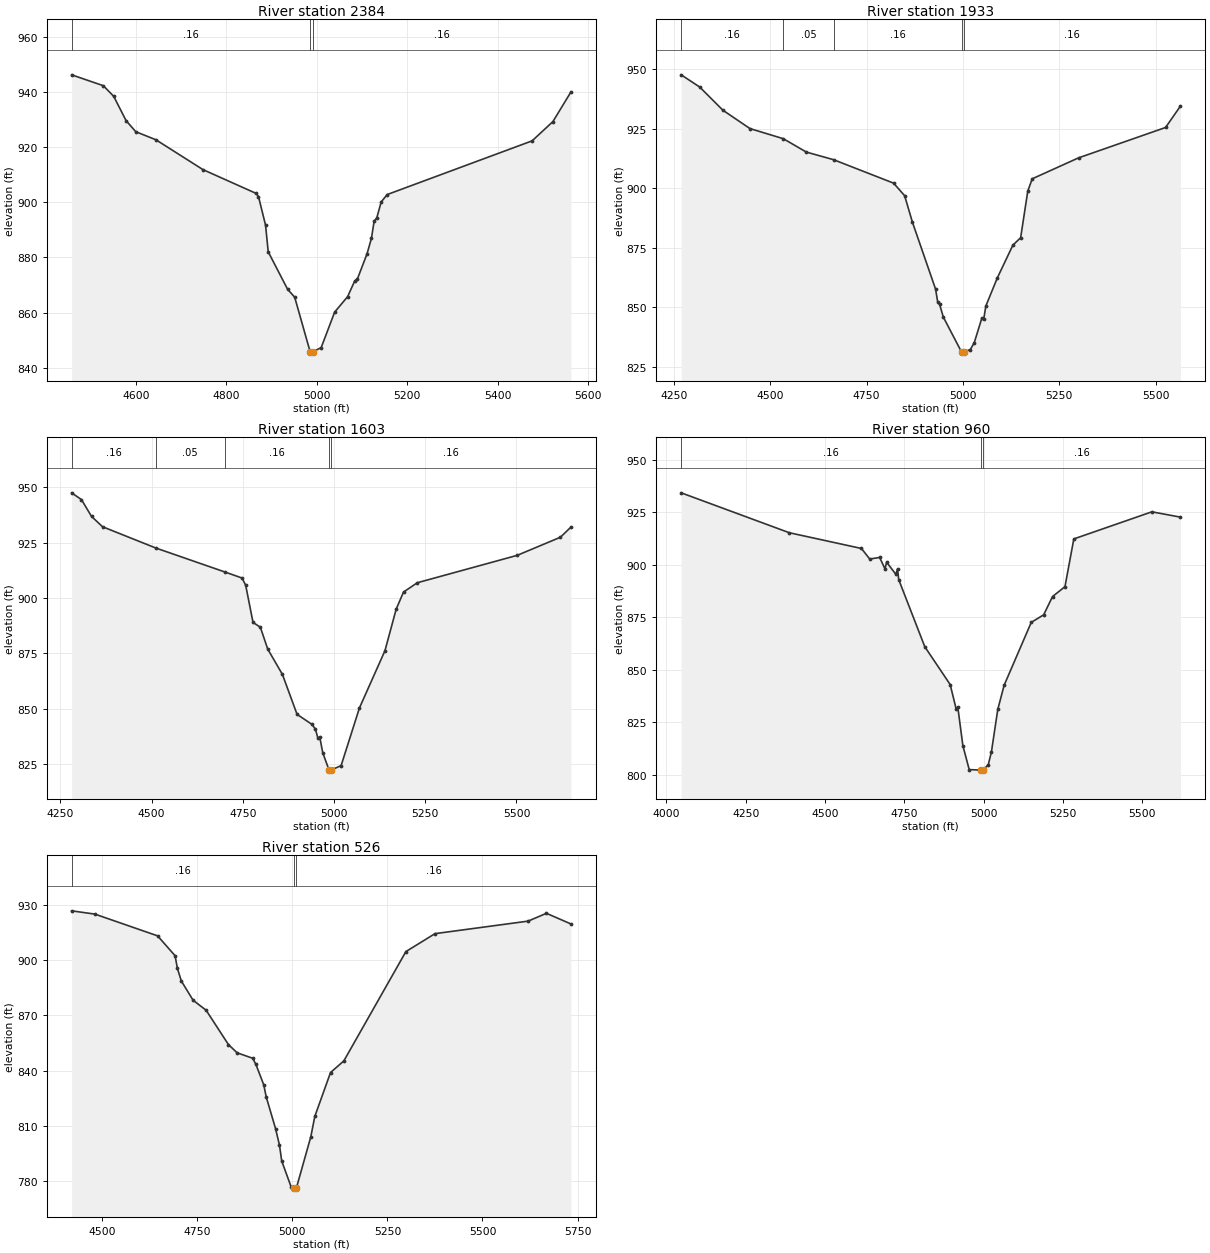
Type RM Length L Ch R = 1,2384,451,451,451
BEGIN DESCRIPTION:
UNT 1056 IN LATR 5.0
END DESCRIPTION:
XS GIS Cut Line= 3
      2953848.08     10080088.62      2954516.45     10080483.56
      2954837.62     10080422.80
#Sta/Elev= 30
  4458.4  946.26  4528.5  942.31  4551.4  938.45  4578.7  929.65  4600.1  925.62
  4644.7  922.69  4748.5  911.87  4865.4  903.28  4871.3  902.09  4886.9  891.70
  4892.8  882.03  4935.6  868.45  4951.3  865.56  4985.4  845.77  4988.1  845.27
  4991.4  845.77  5009.8  847.28  5039.6  860.16  5068.3  865.78  5084.0  871.49
  5089.8  872.16  5111.2  881.34  5120.9  886.95  5126.8  893.11  5132.7  894.38
  5142.5  900.16  5155.8  902.82  5475.9  922.30  5521.8  929.28  5561.6  940.02
#Mann=3,-1,0
  4458.4    0.16       0  4985.4    0.07       0  4991.4    0.16       0
Bank Sta=4985.4,4991.4
Exp/Cntr=0.3,0.1

Type RM Length L Ch R = 1,1933,330,330,330
BEGIN DESCRIPTION:
UNT 1056 IN LATR 4.0
END DESCRIPTION:
XS GIS Cut Line= 4
      2953600.67     10080770.02      2954091.10     10080813.42
      2954603.25     10080770.02      2954868.04     10080652.82
#Sta/Elev= 30
  4268.7  947.71  4316.7  942.59  4376.9  932.85  4447.2  925.13  4533.9  920.87
  4593.6  915.25  4664.2  912.06  4820.1  902.20  4848.7  896.93  4868.8  885.85
  4929.0  857.68  4934.5  852.27  4939.5  851.25  4949.1  845.94  4996.3  831.29
  4999.0  830.79  5002.3  831.29  5019.3  832.31  5029.4  835.19  5048.9  845.39
  5053.9  844.99  5059.5  850.60  5089.6  862.51  5129.7  876.17  5149.8  879.28
  5168.3  898.85  5179.9  904.03  5300.0  912.82  5526.0  925.59  5564.6  934.58
#Mann=5,-1,0
  4268.7    0.16       0  4533.9    0.05       0  4664.2    0.16       0
  4996.3    0.07       0  5002.3    0.16       0
Bank Sta=4996.3,5002.3
Exp/Cntr=0.3,0.1

Type RM Length L Ch R = 1,1603,643,643,643
BEGIN DESCRIPTION:
UNT 1056 IN LATR 3.0
END DESCRIPTION:
XS GIS Cut Line= 3
      2953544.21     10081026.09      2954468.70     10081125.92
      2954875.09     10080961.64
#Sta/Elev= 30
  4280.9  947.54  4307.9  944.47  4335.5  936.87  4365.6  932.23  4511.5  922.63
  4700.2  911.84  4747.9  909.07  4757.9  905.81  4778.0  889.02  4798.1  886.86
  4818.3  876.99  4858.5  865.57  4898.7  847.52  4939.0  843.05  4949.0  840.86
  4955.8  836.75  4960.8  837.30  4969.1  830.18  4986.3  822.39  4989.0  821.89
  4992.3  822.39  5019.4  824.39  5069.7  850.45  5139.5  876.24  5170.3  895.01
  5190.4  902.74  5228.3  906.95  5501.9  919.31  5620.4  927.49  5649.1  932.05
#Mann=5,-1,0
  4280.9    0.16       0  4511.5    0.05       0  4700.2    0.16       0
  4986.3    0.07       0  4992.3    0.16       0
Bank Sta=4986.3,4992.3
Exp/Cntr=0.3,0.1

Type RM Length L Ch R = 1,960,434,434,434
BEGIN DESCRIPTION:
UNT 1056 IN LATR 2.0
END DESCRIPTION:
XS GIS Cut Line= 4
      2953635.42     10081438.43      2954299.43     10081620.71
      2954698.74     10081616.37      2954915.77     10081182.31
#Sta/Elev= 30
  4046.9  934.37  4387.6  915.35  4614.9  907.85  4641.1  902.81  4672.3  903.59
  4689.0  898.12  4694.2  901.30  4723.5  895.51  4728.6  898.16  4732.4  893.00
  4814.5  861.03  4894.5  843.00  4913.5  831.25  4918.5  832.26  4934.5  813.88
  4954.5  802.46  4991.5  802.24  4994.3  801.74  4997.5  802.24  5014.5  804.77
  5024.5  810.94  5044.5  831.14  5064.5  842.65  5150.0  872.64  5189.1  876.23
  5217.0  884.93  5256.2  889.65  5284.1  912.40  5530.1  925.32  5620.1  922.78
#Mann=3,-1,0
  4046.9    0.16       0  4991.5    0.07       0  4997.5    0.16       0
Bank Sta=4991.5,4997.5
Exp/Cntr=0.3,0.1

Type RM Length L Ch R = 1,526,0,0,0
BEGIN DESCRIPTION:
UNT 1056 IN LATR 1.0
END DESCRIPTION:
XS GIS Cut Line= 2
      2954616.27     10082493.13      2954941.79     10081221.43
#Sta/Elev= 30
  4419.8  926.85  4481.1  925.06  4645.8  913.24  4691.8  902.44  4697.9  895.57
  4708.2  888.70  4739.2  878.22  4773.4  872.80  4832.1  854.13  4855.0  849.64
  4895.8  846.69  4904.3  843.35  4925.0  832.19  4931.4  825.68  4955.9  808.46
  4966.3  799.40  4972.2  790.81  4997.2  776.58  5004.6  776.02  5007.3  775.52
  5010.6  776.02  5048.7  804.02  5059.2  815.06  5100.5  838.92  5135.5  845.24
  5298.7  904.69  5375.2  914.44  5620.0  921.25  5668.2  925.50  5732.5  919.72
#Mann=3,-1,0
  4419.8    0.16       0  5004.6    0.07       0  5010.6    0.16       0
Bank Sta=5004.6,5010.6
Exp/Cntr=0.3,0.1

Chan Stop Cuts=-1