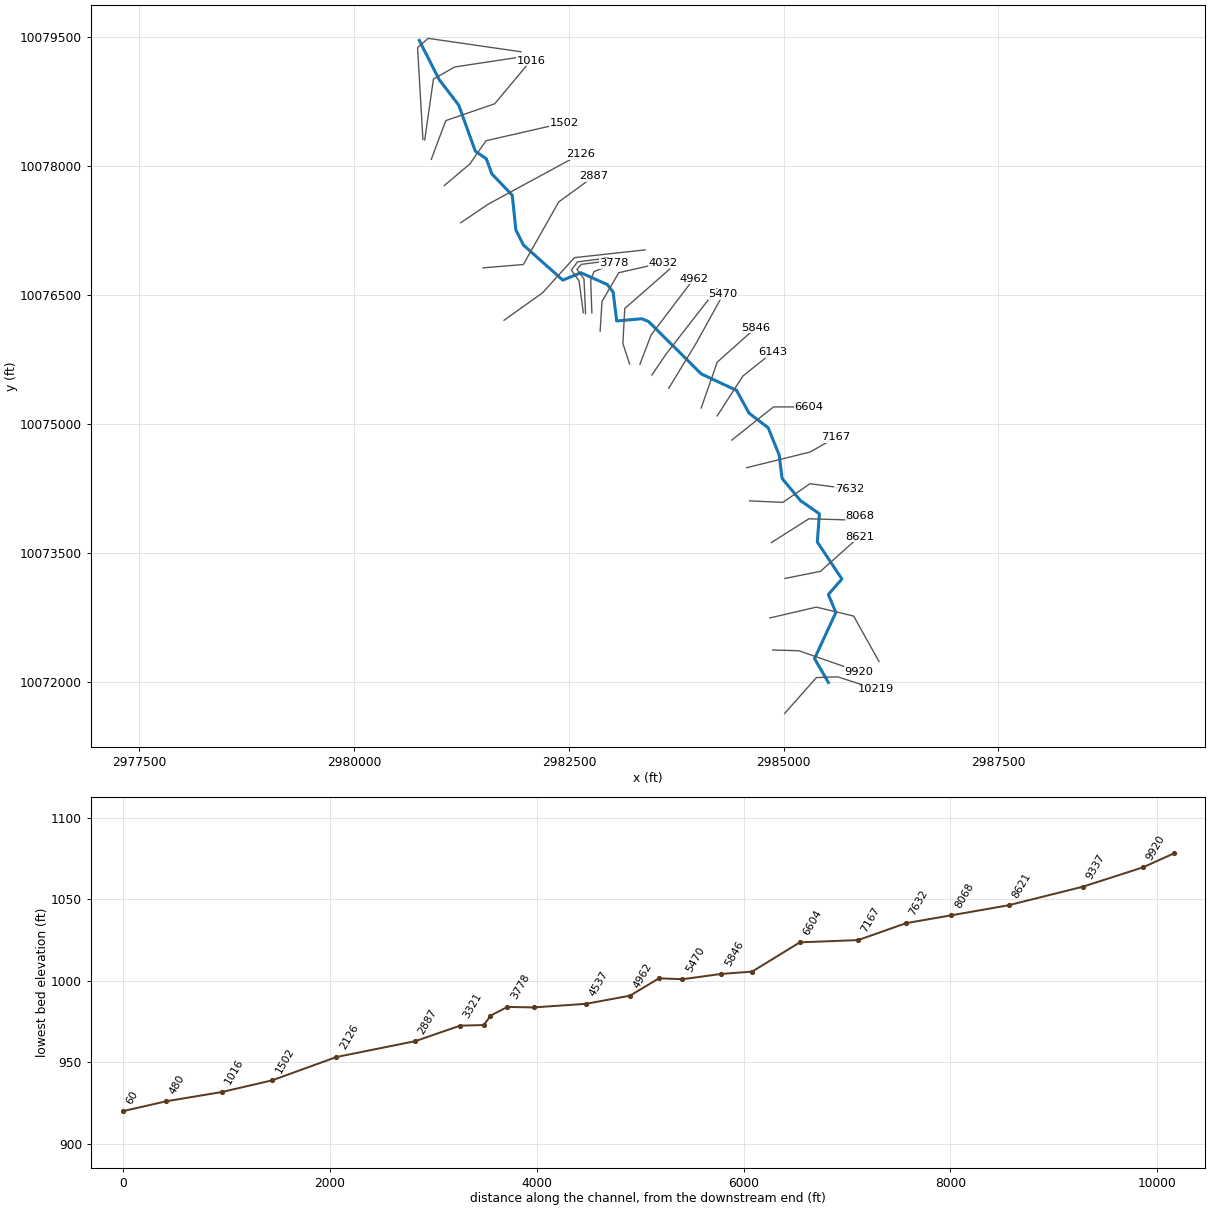
--- UNT 1061 IN LATR.prj (project) ---

Proj Title=UNT 1061 IN LATR Base Level Engineering
Current Plan=p01
Default Exp/Contr=0.3,0.1
English Units
Geom File=g01
Flow File=f01
Plan File=p01
Y Axis Title=Elevation
X Axis Title(PF)=Main Channel Distance
X Axis Title(XS)=Station
BEGIN DESCRIPTION:
UNT 1061 IN LATR
END DESCRIPTION:
DSS Export Rating Curves= 0
DSS Export Rating Curve Sorted= 0
DSS Export Volume Flow Curves= 0
DXF OffsetX= 0
DXF OffsetY= 0
DXF ScaleX= 1
DXF ScaleY= 10

--- UNT 1061 IN LATR.p01 (plan) ---

Plan Title=Multiple Run
Short Identifier=Multiple
Geom File=g01
Flow File=f01
Subcritical Flow
K Sum by GR= 0
Std Step Tol= 0.01
Critical Tol= 0.01
Num of Std Step Trials= 20
Max Error Tol= 0.3
Flow Tol Ratio= 0.001
Split Flow NTrial= 30
Split Flow Tol= 0.02
Split Flow Ratio= 0.02
Log Output Level= 0
Friction Slope Method= 1
Unsteady Friction Slope Method= 2
Unsteady Bridges Friction Slope Method= 1
Parabolic Critical Depth
Global Vel Dist=  1 , 1 , 1
Global Log Level= 0
CheckData=True
Encroach Param= -1, 0, 0, 0
BEGIN DESCRIPTION:
Multiple Run
END DESCRIPTION:

--- UNT 1061 IN LATR.f01 (steady flow) ---

Flow Title=Multiple
Program Version=4.10
Number of Profiles= 7
Profile Names=10-year,25-year,50-year,1pct_min,100-year,1pct_plu,500-year
River Rch & RM=UNT 1061 IN LATR,Reach-1         ,10219
    1037    1517    1938    1812    2451    3315    3935
River Rch & RM=UNT 1061 IN LATR,Reach-1         ,8621
    1179    1731    2216    2077    2808    3798    4524
River Rch & RM=UNT 1061 IN LATR,Reach-1         ,3321
    1460    2167    2795    2636    3565    4821    5821
Boundary for River Rch & Prof#=UNT 1061 IN LATR,Reach-1         , 1
Up Type= 0
Dn Type= 3
Dn Slope=0.014
Boundary for River Rch & Prof#=UNT 1061 IN LATR,Reach-1         , 2
Up Type= 0
Dn Type= 3
Dn Slope=0.014
Boundary for River Rch & Prof#=UNT 1061 IN LATR,Reach-1         , 3
Up Type= 0
Dn Type= 3
Dn Slope=0.014
Boundary for River Rch & Prof#=UNT 1061 IN LATR,Reach-1         , 4
Up Type= 0
Dn Type= 3
Dn Slope=0.014
Boundary for River Rch & Prof#=UNT 1061 IN LATR,Reach-1         , 5
Up Type= 0
Dn Type= 3
Dn Slope=0.014
Boundary for River Rch & Prof#=UNT 1061 IN LATR,Reach-1         , 6
Up Type= 0
Dn Type= 3
Dn Slope=0.014
Boundary for River Rch & Prof#=UNT 1061 IN LATR,Reach-1         , 7
Up Type= 0
Dn Type= 3
Dn Slope=0.014
DSS Import GetInterval= 0
DSS Import GetPeak= 0
DSS Import FillOption= 0

--- UNT 1061 IN LATR.g01 (geometry) ---

Geom Title=Existing Conditions
Program Version=4.10

River Reach=UNT 1061 IN LATR,Reach-1
Reach XY= 30
      2985521.15     10071989.98      2985359.96     10072267.69
      2985608.13     10072805.43       2985520.4     10073013.47
      2985678.42     10073194.66      2985392.05     10073625.23
      2985416.33       10073953.      2985195.53     10074107.64
      2984982.16     10074365.26      2984948.39     10074637.79
      2984819.68     10074955.66      2984598.39     10075123.77
      2984451.85     10075390.14      2984042.08     10075581.32
      2983427.59     10076191.61      2983348.44     10076224.38
      2983056.39      10076198.6      2983015.16     10076535.19
      2982947.02     10076622.46       2982640.2     10076759.51
      2982428.47     10076673.73      2981971.66     10077081.66
      2981882.71     10077258.42      2981840.65     10077662.21
      2981603.03     10077910.89      2981538.03      10078087.2
      2981410.85     10078174.59      2981216.78     10078713.03
      2980991.48     10079005.66      2980758.47     10079463.73

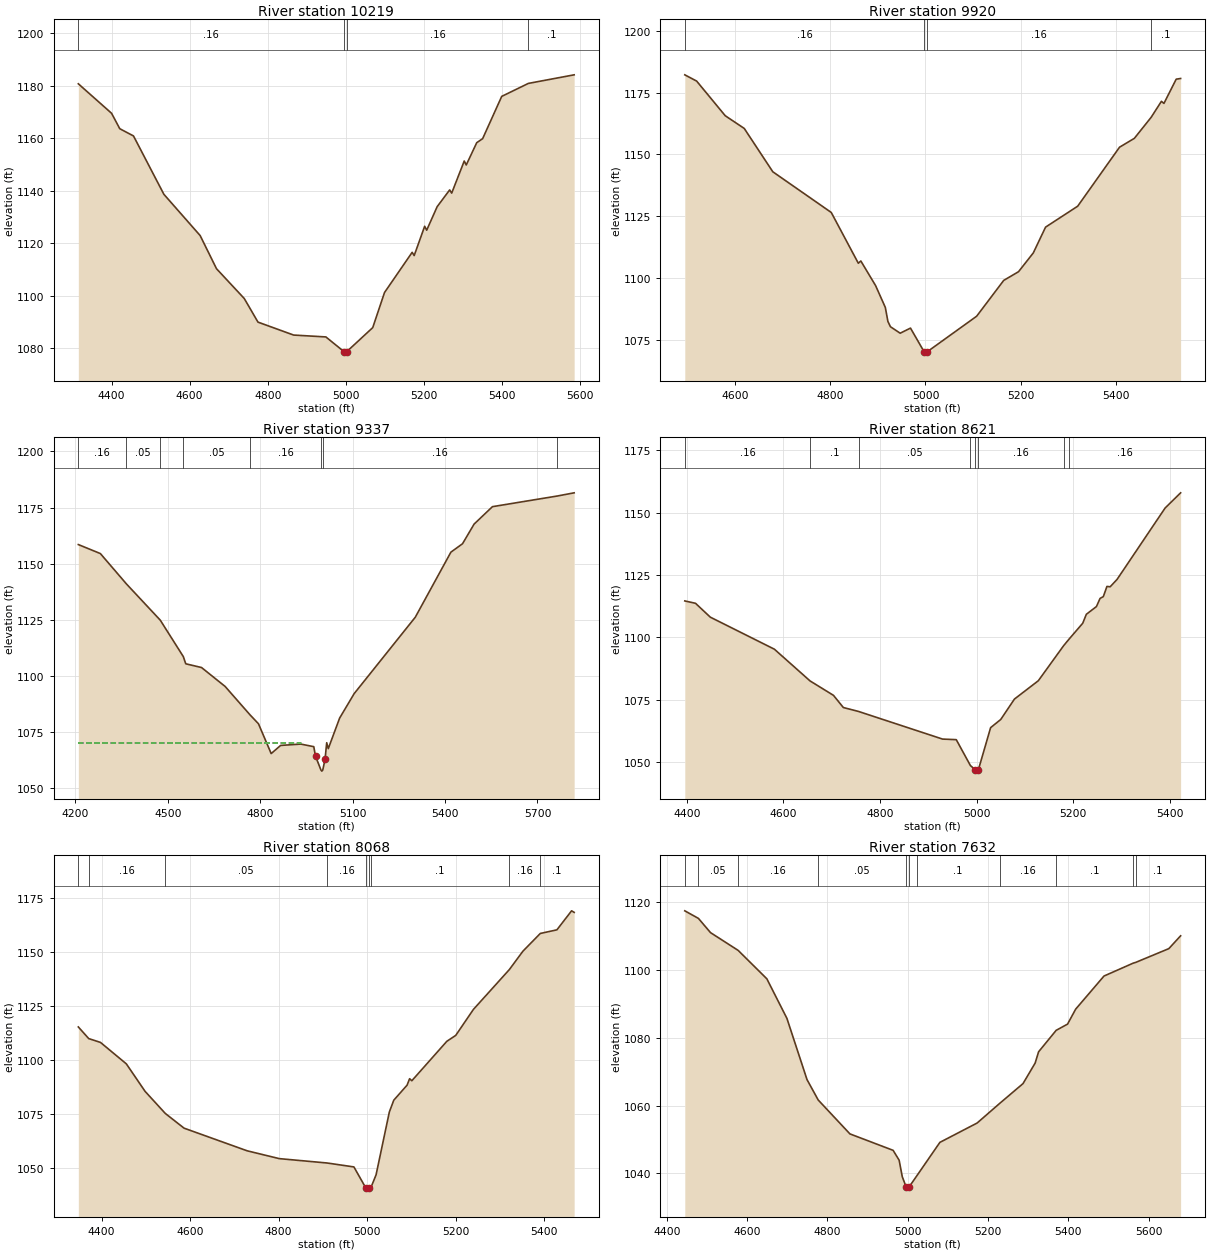
Type RM Length L Ch R = 1 ,10219   ,299,299,299
BEGIN DESCRIPTION:
UNT 1061 IN LATR 23.0
END DESCRIPTION:
XS GIS Cut Line= 4
      2985012.43     10071630.05      2985381.33     10072046.69
      2985628.73     10072055.37       2986071.4     10071912.15
#Sta/Elev= 30
    4315  1180.8  4400.1 1169.57  4421.1 1163.69  4456.2 1160.94    4534 1138.71
  4626.9 1122.98  4668.7 1110.36  4739.8    1099  4774.9 1090.01  4866.2 1085.08
  4948.7 1084.37  4995.7  1078.7  4998.4  1078.2  5001.7  1078.7  5068.7 1087.92
  5098.8 1101.28  5169.6  1116.6  5174.8 1115.37  5201.6 1126.53  5206.8 1125.03
  5233.6 1133.99  5265.6 1140.37  5270.8 1139.15  5302.9 1151.38  5308.1 1149.88
  5334.9 1158.37    5350 1159.89  5398.9 1176.01  5467.1 1180.95  5584.3 1184.22
#Mann= 4 ,-1 , 0
    4315     .16       0  4995.7     .07       0  5001.7     .16       0
  5467.1      .1       0
Bank Sta=4995.7,5001.7
XS Rating Curve= 0 ,0
Exp/Cntr=0.3,0.1

Type RM Length L Ch R = 1 ,9920    ,583,583,583
BEGIN DESCRIPTION:
UNT 1061 IN LATR 22.0
END DESCRIPTION:
XS GIS Cut Line= 3
      2984873.53     10072367.87      2985177.34     10072359.19
      2985874.82     10072116.59
#Sta/Elev= 30
    4494  1182.2  4518.9 1179.67    4579 1165.66    4619 1160.51    4679 1142.99
  4801.9 1126.53  4858.8 1105.99  4864.1  1106.9  4895.2 1096.92  4915.6  1088.1
    4921 1082.45  4926.3 1080.32  4946.8 1077.69  4968.5 1079.75  4997.3 1070.13
    5000 1069.63  5003.3 1070.13  5107.6 1084.56  5164.5 1099.05  5195.6 1102.56
  5226.7 1110.17  5252.5  1120.6    5320 1129.06    5408 1152.93  5439.1  1156.5
  5474.5 1165.03    5496 1171.48  5501.3 1170.63  5527.1 1180.44  5536.4 1180.72
#Mann= 4 ,-1 , 0
    4494     .16       0  4997.3     .07       0  5003.3     .16       0
  5474.5      .1       0
Bank Sta=4997.3,5003.3
XS Rating Curve= 0 ,0
Exp/Cntr=0.3,0.1

Type RM Length L Ch R = 1 ,9337    ,716,716,716
BEGIN DESCRIPTION:
UNT 1061 IN LATR 20.0
END DESCRIPTION:
XS GIS Cut Line= 4
      2984838.82     10072741.14      2985381.33       10072867.
      2985815.36     10072762.84       2986110.5     10072233.31
#Sta/Elev= 30
  4209.6 1158.52  4281.1 1154.52  4365.3 1141.07  4475.6 1124.88  4550.4 1108.67
  4558.3 1105.47  4609.6  1103.8  4686.1 1095.39  4766.5 1082.82  4794.4 1078.78
  4835.6 1065.52  4866.4 1069.15  4931.9 1069.74  4973.9 1068.59  4979.5 1064.38
  4997.1 1058.21  4999.9 1057.71  5003.1 1058.21  5010.4 1062.92  5015.9 1070.35
    5021 1067.73  5057.9 1081.34    5105 1092.19  5303.4 1126.19    5419 1155.14
  5456.7 1158.88  5494.4 1167.64  5553.9 1175.38  5764.7 1180.13  5819.1 1181.54
#Mann= 8 ,-1 , 0
  4209.6     .16       0  4365.3     .05       0  4475.6      .1       0
  4550.4     .05       0  4766.5     .16       0  4997.1     .07       0
  5003.1     .16       0  5764.7      .1       0
#XS Ineff= 2 , 0
         4931.25 1070.44
Permanent Ineff=
       T       T
Bank Sta=4979.5,5010.4
XS Rating Curve= 0 ,0
Exp/Cntr=0.3,0.1

Type RM Length L Ch R = 1 ,8621    ,553,553,553
BEGIN DESCRIPTION:
UNT 1061 IN LATR 19.0
END DESCRIPTION:
XS GIS Cut Line= 3
      2985016.72      10073201.2      2985429.07     10073283.67
      2985880.49     10073687.34
#Sta/Elev= 30
    4396 1114.64  4418.2 1113.69  4448.8 1108.13  4581.3 1095.29  4655.3 1082.54
  4703.7 1076.76  4724.1 1071.88  4755.9 1070.28  4929.4 1059.22  4957.8 1058.98
  4987.1 1048.59  4997.5 1046.86  5000.2 1046.36  5003.5 1046.86  5028.9 1063.81
  5049.8 1067.07  5078.2 1075.27  5127.6 1082.62  5179.9 1096.66  5190.6 1099.18
  5219.5 1105.68    5227 1109.28  5247.9 1112.39  5255.4 1115.65  5262.1 1116.36
  5269.6 1120.45  5276.3 1120.32  5290.6 1123.28    5390 1151.91  5422.1 1158.01
#Mann= 8 ,-1 , 0
    4396     .16       0  4655.3      .1       0  4755.9     .05       0
  4987.1     .16       0  4997.5     .07       0  5003.5     .16       0
  5179.9      .1       0  5190.6     .16       0
Bank Sta=4997.5,5003.5
XS Rating Curve= 0 ,0
Exp/Cntr=0.3,0.1

Type RM Length L Ch R = 1 ,8068    ,436,436,436
BEGIN DESCRIPTION:
UNT 1061 IN LATR 18.0
END DESCRIPTION:
XS GIS Cut Line= 4
      2984856.18     10073617.88      2985294.52     10073895.65
      2985728.55     10073882.63      2985889.14     10073930.37
#Sta/Elev= 30
  4347.4 1115.16  4370.9 1109.78  4397.5 1108.01  4455.9  1098.1  4498.3 1085.38
  4543.9 1075.19  4586.4 1068.37  4728.9 1057.91  4801.6 1054.29  4909.6 1052.27
  4970.3 1050.45  4997.3 1040.69  5000.1 1040.19  5003.3 1040.69  5008.5 1040.79
  5020.4 1046.81  5050.4 1075.86  5060.4  1081.3  5090.4 1088.24  5096.2 1091.24
  5101.2 1090.29  5180.4 1108.54  5200.4 1111.25  5240.5 1123.29  5321.7  1141.7
  5352.3 1150.18  5391.6 1158.38  5429.1 1160.05  5462.3 1168.84  5468.1 1168.13
#Mann= 9 ,-1 , 0
  4347.4      .1       0  4370.9     .16       0  4543.9     .05       0
  4909.6     .16       0  4997.3     .07       0  5003.3     .16       0
  5008.5      .1       0  5321.7     .16       0  5391.6      .1       0
Bank Sta=4997.3,5003.3
XS Rating Curve= 0 ,0
Exp/Cntr=0.3,0.1

Type RM Length L Ch R = 1 ,7632    ,465,465,465
BEGIN DESCRIPTION:
UNT 1061 IN LATR 17.0
END DESCRIPTION:
XS GIS Cut Line= 4
      2984604.39     10074103.98      2984990.71     10074086.62
      2985307.55     10074303.63      2985767.61     10074242.87
#Sta/Elev= 30
    4445 1117.46  4478.9 1115.23  4509.1 1111.03  4577.9 1105.79  4649.3 1097.42
  4699.3 1085.75  4749.4 1067.68  4777.3 1061.67  4856.2 1051.68  4963.8 1046.83
  4978.8 1043.92  4986.6 1039.05  4996.7 1035.89  4999.5 1035.39  5002.7 1035.89
  5022.2 1039.21  5080.3 1049.18  5173.1 1054.89  5228.8 1060.63  5287.3 1066.51
  5317.5 1072.56  5326.1 1075.89  5369.9 1082.22  5398.2 1084.05  5418.4 1088.46
    5489 1098.23  5561.9 1102.04  5567.7 1102.24  5650.4 1106.31  5679.8 1110.09
#Mann= 11 ,-1 , 0
    4445      .1       0  4478.9     .05       0  4577.9     .16       0
  4777.3     .05       0  4996.7    .035       0  5002.7     .05       0
  5022.2      .1       0  5228.8     .16       0  5369.9      .1       0
  5561.9     .16       0  5567.7      .1       0
Bank Sta=4996.7,5002.7
XS Rating Curve= 0 ,0
Exp/Cntr=0.3,0.1

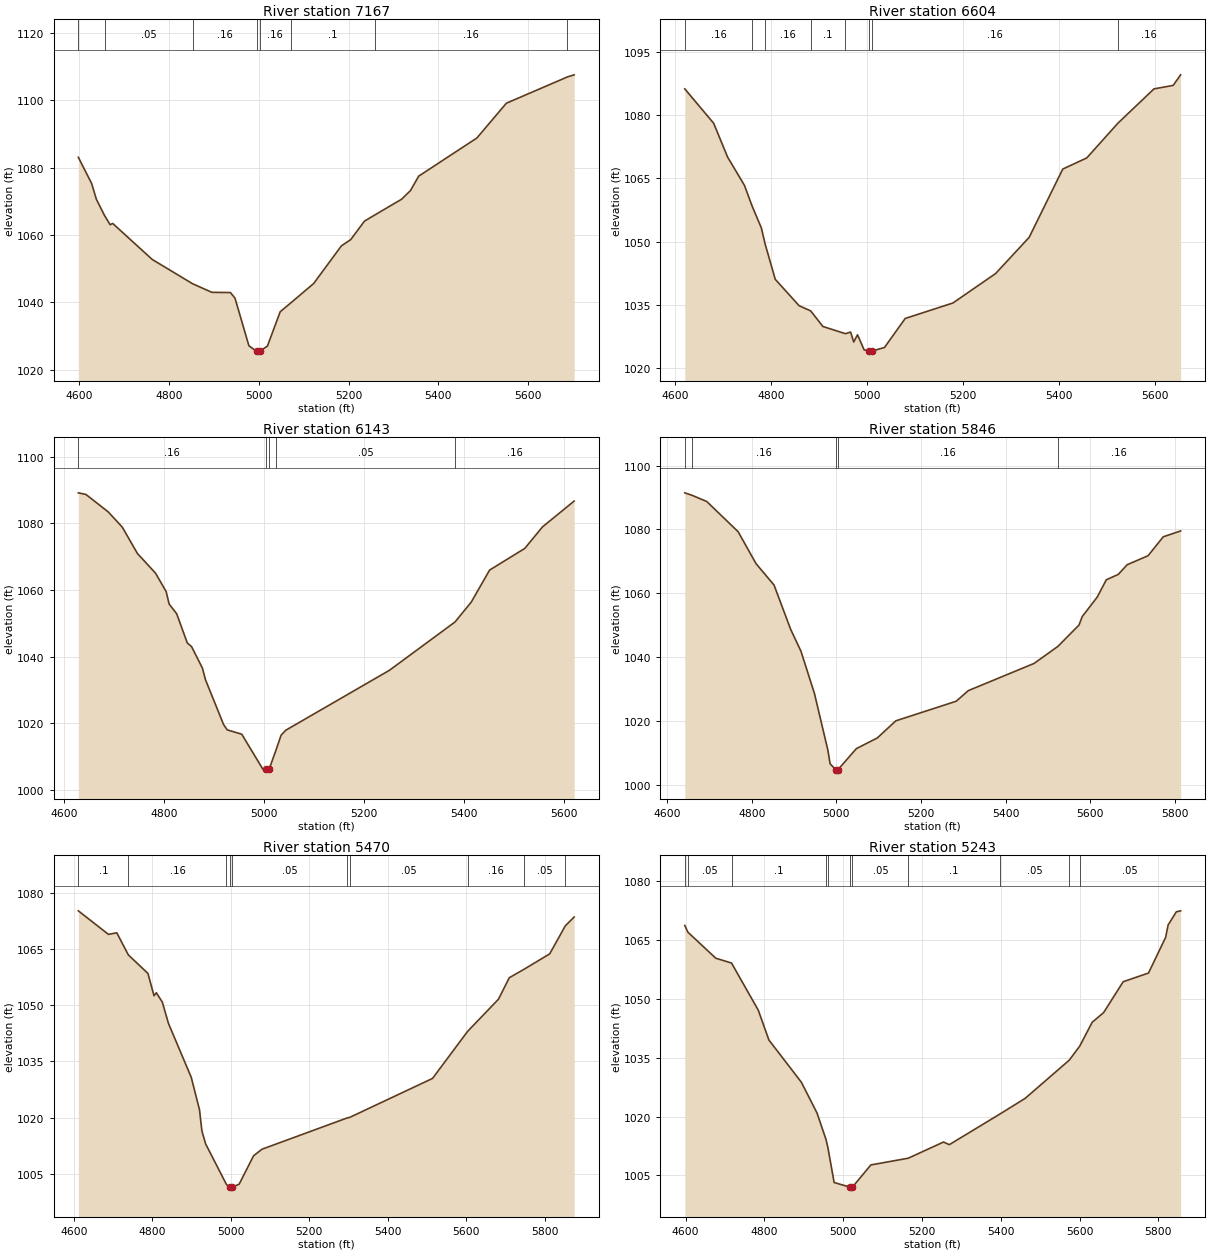
Type RM Length L Ch R = 1 ,7167    ,563,563,563
BEGIN DESCRIPTION:
UNT 1061 IN LATR 16.0
END DESCRIPTION:
XS GIS Cut Line= 3
      2984569.72     10074490.27      2985307.55     10074672.56
      2985607.01     10074841.82
#Sta/Elev= 30
  4598.4  1083.1    4628 1075.32  4638.6 1070.62  4656.9 1065.78  4669.2 1063.08
  4674.9 1063.46  4762.9 1052.77  4852.7 1045.57  4895.8 1043.01    4937 1042.95
  4947.3 1041.27  4978.2 1027.16  4995.8 1025.47  4998.6 1024.97  5001.8 1025.47
  5019.4 1027.06  5047.9 1037.26  5071.5 1039.88  5122.4 1045.63  5184.2 1056.82
  5204.8 1058.65  5235.7 1064.16  5258.6 1065.98  5318.2 1070.64    5338 1073.22
  5356.3  1077.5  5485.8 1088.81  5551.4 1099.13  5687.5 1106.94  5702.4 1107.56
#Mann= 8 ,-1 , 0
  4598.4      .1       0  4656.9     .05       0  4852.7     .16       0
  4995.8     .07       0  5001.8     .16       0  5071.5      .1       0
  5258.6     .16       0  5687.5      .1       0
Bank Sta=4995.8,5001.8
XS Rating Curve= 0 ,0
Exp/Cntr=0.3,0.1

Type RM Length L Ch R = 1 ,6604    ,461,461,461
BEGIN DESCRIPTION:
UNT 1061 IN LATR 15.0
END DESCRIPTION:
XS GIS Cut Line= 3
      2984396.08     10074811.44       2984882.2     10075197.73
      2985293.98     10075197.73
#Sta/Elev= 30
  4620.5 1086.17  4680.7 1078.02  4709.6 1070.03  4744.8 1063.32  4760.7 1058.43
    4780 1053.23    4788 1049.37  4808.9 1041.08  4858.6 1034.83  4882.7  1033.6
  4908.2 1029.91    4955 1028.21  4965.9 1028.58  4972.3 1026.24  4980.3 1027.94
    4994 1024.38  5004.5  1024.1  5007.3  1023.6  5010.5  1024.1  5036.4 1024.93
  5079.6 1031.81  5178.9 1035.47  5267.7 1042.43  5337.7 1051.01  5407.7 1067.18
  5457.7 1069.82  5522.7 1078.06  5597.7 1086.17  5637.7    1087  5653.2  1089.5
#Mann= 8 ,-1 , 0
  4620.5     .16       0  4760.7     .05       0    4788     .16       0
  4882.7      .1       0    4955     .16       0  5004.5     .07       0
  5010.5     .16       0  5522.7     .16       0
Bank Sta=5004.5,5010.5
XS Rating Curve= 0 ,0
Exp/Cntr=0.3,0.1

Type RM Length L Ch R = 1 ,6143    ,297,297,297
BEGIN DESCRIPTION:
UNT 1061 IN LATR 14.0
END DESCRIPTION:
XS GIS Cut Line= 3
       2984226.8     10075093.53       2984526.3     10075557.97
      2984869.18     10075831.41
#Sta/Elev= 30
    4629 1089.12  4644.2 1088.63  4688.7 1083.41  4716.8 1078.84  4747.1 1070.93
  4783.4    1065  4804.6 1059.48  4810.5 1055.76  4825.7 1052.81  4846.8 1044.08
  4855.3    1043  4877.2 1036.49  4883.1 1033.08  4919.4 1019.59  4926.7    1018
  4955.7  1016.7  4998.1 1006.15  5004.2 1006.12    5007 1005.62  5010.2 1006.12
  5023.5 1011.63  5034.3 1016.38  5043.5 1017.87  5250.9 1035.87  5382.1 1050.38
  5414.6 1056.36  5451.1 1065.93  5521.5 1072.44  5556.7 1078.87  5620.2 1086.65
#Mann= 5 ,-1 , 0
    4629     .16       0  5004.2     .07       0  5010.2     .16       0
  5023.5     .05       0  5382.1     .16       0
Bank Sta=5004.2,5010.2
XS Rating Curve= 0 ,0
Exp/Cntr=0.3,0.1

Type RM Length L Ch R = 1 ,5846    ,376,376,376
BEGIN DESCRIPTION:
UNT 1061 IN LATR 13.0
END DESCRIPTION:
XS GIS Cut Line= 3
      2984040.19     10075184.73      2984226.82     10075718.57
      2984678.23     10076122.24
#Sta/Elev= 30
    4642 1091.44  4659.2 1090.66  4693.9 1088.72    4768 1079.25  4810.4 1069.22
  4852.8 1062.54  4892.1 1048.64  4916.4 1041.79  4948.2 1028.57  4979.9 1010.82
  4985.2 1006.53  4998.1 1004.72  5000.9 1004.22  5004.1 1004.72  5047.3 1011.28
  5096.5  1014.6  5140.4 1019.98  5283.1 1026.13  5311.6 1029.45  5467.1 1037.98
  5523.3 1043.32  5573.2 1050.02  5580.7 1052.65  5615.9 1058.72  5637.6 1064.19
  5665.8 1065.87  5686.9 1068.91  5736.2 1071.73  5772.1 1077.66  5813.1  1079.5
#Mann= 5 ,-1 , 0
    4642      .1       0  4659.2     .16       0  4998.1    .035       0
  5004.1     .16       0  5523.3     .16       0
Bank Sta=4998.1,5004.1
XS Rating Curve= 0 ,0
Exp/Cntr=0.3,0.1

Type RM Length L Ch R = 1 ,5470    ,227,227,227
BEGIN DESCRIPTION:
UNT 1061 IN LATR 12.0
END DESCRIPTION:
XS GIS Cut Line= 3
      2983662.59     10075414.76      2983979.42     10075935.58
      2984296.26     10076508.49
#Sta/Elev= 30
  4610.9 1075.18  4687.7  1068.9    4709 1069.32  4738.4 1063.43  4788.4 1058.48
  4803.9 1052.52  4809.8 1053.34  4825.2 1050.81  4840.7 1045.16  4898.8 1030.78
  4919.9 1022.12    4926 1016.47  4935.6    1013  4988.6 1002.19  4996.6 1001.45
  4999.4 1000.95  5002.6 1001.45  5020.9 1002.26  5057.7 1009.84  5079.1 1011.59
  5295.7 1019.91    5303 1020.09    5514 1030.47  5603.4 1043.01  5682.3 1051.62
  5709.8 1057.34  5746.8 1059.55  5812.9 1063.71  5852.6 1071.17  5875.2 1073.53
#Mann= 10 ,-1 , 0
  4610.9      .1       0  4738.4     .16       0  4988.6     .05       0
  4996.6    .035       0  5002.6     .05       0  5295.7      .1       0
    5303     .05       0  5603.4     .16       0  5746.8     .05       0
  5852.6     .16       0
Bank Sta=4996.6,5002.6
XS Rating Curve= 0 ,0
Exp/Cntr=0.3,0.1

Type RM Length L Ch R = 1 ,5243    ,281,281,281
BEGIN DESCRIPTION:
Mapping XS 0059b398
END DESCRIPTION:
XS GIS Cut Line= 3
      2983465.84      10075568.7      2983630.75     10075811.72
      2984223.21     10076573.45
#Sta/Elev= 30
    4598 1068.77  4605.9 1067.06  4676.6 1060.42  4716.6 1059.19  4784.5 1047.17
  4811.5 1039.55  4893.9 1028.78  4933.6 1020.94  4956.6 1014.13  4961.5 1011.98
  4977.1 1003.19  5017.5    1002  5020.3  1001.5  5023.5    1002  5070.3 1007.67
  5165.2 1009.39  5254.9 1013.52  5269.4 1012.84  5397.8 1020.65  5462.1 1024.66
  5574.1 1034.42  5600.7 1038.01  5632.2 1044.08  5661.2 1046.54  5710.9 1054.42
  5775.2 1056.64  5818.6 1065.73    5825 1068.91  5845.8 1072.26  5856.7 1072.51
#Mann= 11 ,-1 , 0
    4598      .1       0  4605.9     .05       0  4716.6      .1       0
  4956.6     .16       0  4961.5     .05       0  5017.5    .035       0
  5023.5     .05       0  5165.2      .1       0  5397.8     .05       0
  5574.1      .1       0  5600.7     .05       0
Bank Sta=5017.5,5023.5
XS Rating Curve= 0 ,0
Exp/Cntr=0.3,0.1

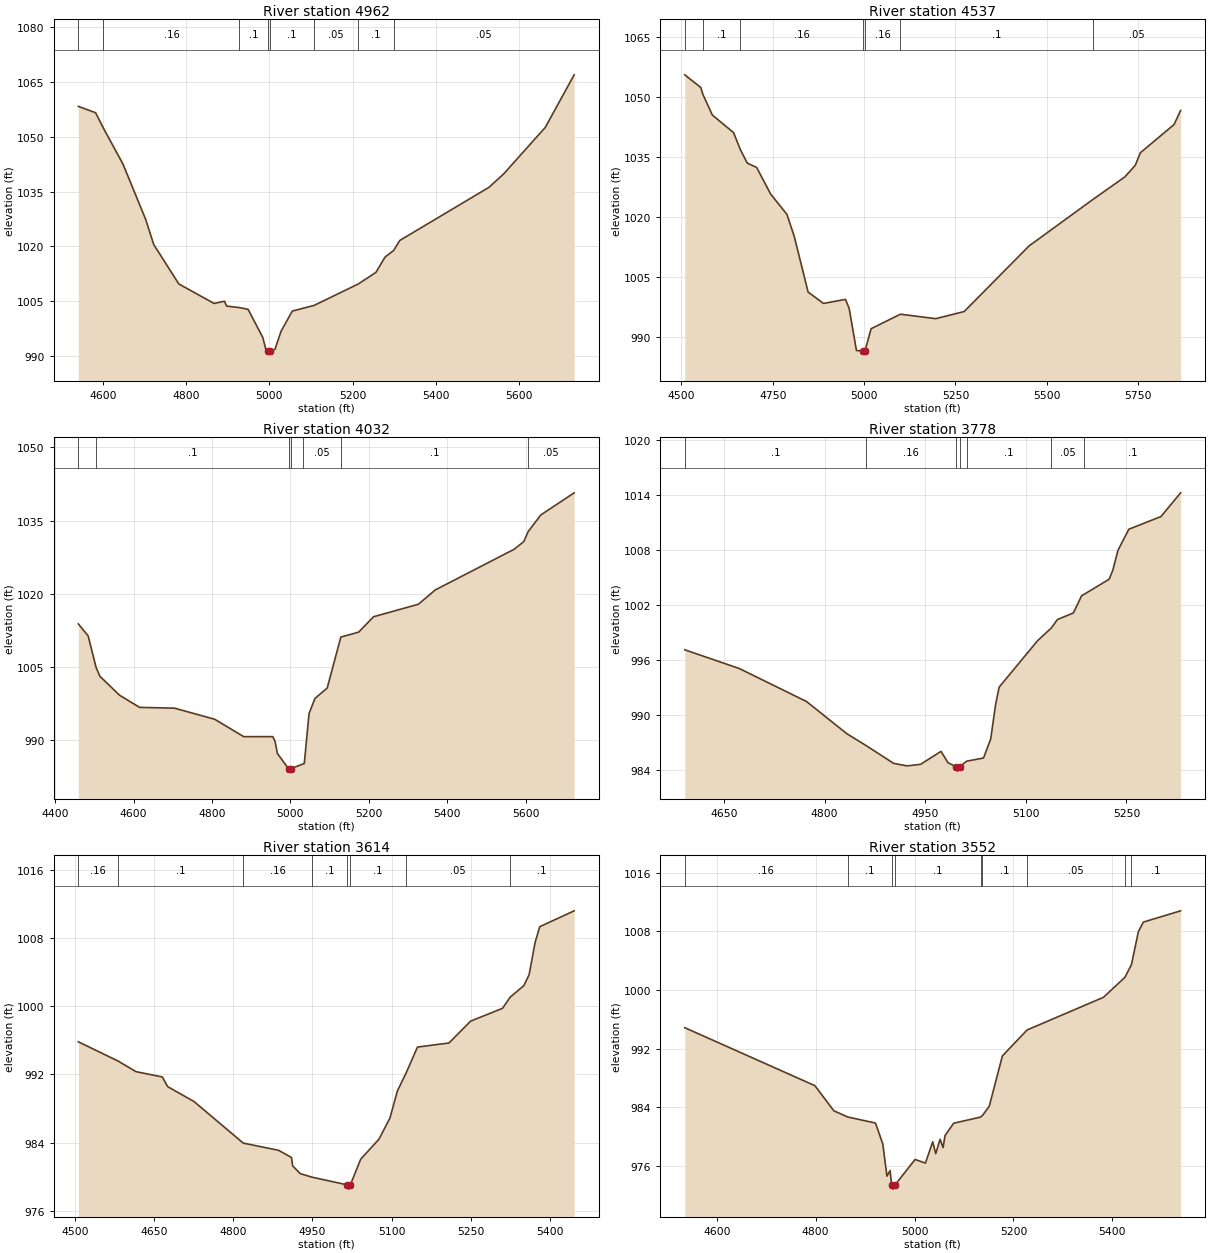
Type RM Length L Ch R = 1 ,4962    ,425,425,425
BEGIN DESCRIPTION:
UNT 1061 IN LATR 11.0
END DESCRIPTION:
XS GIS Cut Line= 3
      2983326.94     10075694.57      2983457.14     10076035.25
      2983956.25     10076692.77
#Sta/Elev= 30
  4541.3 1058.32  4582.7 1056.59  4601.7 1052.33  4648.2 1042.61    4703  1027.4
  4722.3 1020.53  4782.5 1009.75  4867.3 1004.41    4892 1005.03  4897.4 1003.69
  4927.7 1003.29  4948.8 1002.81  4984.2  995.08    4992  991.57  4995.7  991.33
  4998.5  990.83  5001.7  991.33  5013.3  991.87  5027.8  996.77  5054.9 1002.33
  5107.4 1003.89  5213.6 1009.76  5255.6 1012.91  5277.4 1017.08  5298.4 1018.93
  5312.8 1021.64    5527 1036.18  5562.4 1039.86  5662.2 1052.57  5731.5 1066.95
#Mann= 8 ,-1 , 0
  4541.3      .1       0  4601.7     .16       0  4927.7      .1       0
  4995.7     .07       0  5001.7      .1       0  5107.4     .05       0
  5213.6      .1       0  5298.4     .05       0
Bank Sta=4995.7,5001.7
XS Rating Curve= 0 ,0
Exp/Cntr=0.3,0.1

Type RM Length L Ch R = 1 ,4537    ,505,505,505
BEGIN DESCRIPTION:
UNT 1061 IN LATR 10.0
END DESCRIPTION:
XS GIS Cut Line= 4
      2983206.85     10075696.87      2983128.73     10075935.58
      2983150.43     10076343.57      2983674.53     10076802.69
#Sta/Elev= 30
  4509.5 1055.63    4553 1052.47  4559.5 1050.62  4584.9 1045.55    4643 1041.13
  4661.6 1036.85  4680.5 1033.48  4706.1  1032.4  4744.2 1025.76  4788.9 1020.64
  4808.9 1015.13  4846.9 1001.15    4889   998.3  4949.1  999.32  4959.1  997.08
  4979.1  986.51  4996.2  986.34  4998.9  985.84  5002.2  986.34  5019.2  991.96
  5099.3   995.6  5196.1  994.48  5273.9  996.27  5451.3 1012.72  5626.4  1024.4
  5713.3 1030.02  5741.8 1032.92    5756  1036.1  5848.1 1043.17    5866  1046.7
#Mann= 7 ,-1 , 0
  4509.5     .05       0  4559.5      .1       0  4661.6     .16       0
  4996.2     .07       0  5002.2     .16       0  5099.3      .1       0
  5626.4     .05       0
Bank Sta=4996.2,5002.2
XS Rating Curve= 0 ,0
Exp/Cntr=0.3,0.1

Type RM Length L Ch R = 1 ,4032    ,254,254,254
BEGIN DESCRIPTION:
UNT 1061 IN LATR 9.0
END DESCRIPTION:
XS GIS Cut Line= 4
      2982863.97     10076078.76      2982885.67     10076426.03
      2983080.98     10076760.23      2983597.52     10076877.43
#Sta/Elev= 30
  4459.2 1013.82  4484.2 1011.38  4504.6 1004.87  4514.3 1003.08  4564.4   999.2
  4615.5  996.71  4704.6  996.55  4807.1  994.27  4880.9  990.71  4955.1  990.71
  4961.1  989.73  4966.9  987.27  4995.3  984.14    4998  983.64  5001.3  984.14
  5033.4  985.14  5035.5  985.18  5047.7  995.45  5062.8  998.55    5094 1000.67
  5128.8 1011.13  5174.3 1012.14  5212.2 1015.29  5326.6 1017.86  5369.7 1020.79
  5571.1 1029.14  5595.5 1030.71  5606.3 1032.71  5638.6 1036.15  5723.9  1040.7
#Mann= 7 ,-1 , 0
  4459.2     .16       0  4504.6      .1       0  4995.3     .07       0
  5001.3      .1       0  5033.4     .05       0  5128.8      .1       0
  5606.3     .05       0
Bank Sta=4995.3,5001.3
XS Rating Curve= 0 ,0
Exp/Cntr=0.3,0.1

Type RM Length L Ch R = 1 ,3778    ,164,164,164
BEGIN DESCRIPTION:
Mapping XS 3e66b6c5
END DESCRIPTION:
XS GIS Cut Line= 4
      2982767.69     10076292.41       2982753.8     10076669.12
      2982790.26     10076771.55      2983024.86     10076868.15
#Sta/Elev= 30
  4591.5  997.13  4672.9  995.09  4772.9  991.51    4833  988.01  4861.7  986.72
    4903  984.77    4923   984.5  4943.1  984.67  4973.6  986.08    4984  984.84
  4995.6  984.43  4998.3  983.93  5001.6  984.43  5011.8  985.01    5037  985.36
  5047.7  987.43  5054.9  991.13  5060.3  993.07  5117.7  998.13  5138.3  999.52
  5147.1 1000.42    5171 1001.14  5183.4 1003.03  5187.5 1003.19  5224.3 1004.81
  5229.7 1005.77  5237.5 1007.96  5253.7 1010.25  5301.6 1011.63  5330.9 1014.21
#Mann= 7 ,-1 , 0
  4591.5      .1       0  4861.7     .16       0  4995.6     .07       0
  5001.6     .16       0  5011.8      .1       0  5138.3     .05       0
  5187.5      .1       0
Bank Sta=4995.6,5001.6
XS Rating Curve= 0 ,0
Exp/Cntr=0.3,0.1

Type RM Length L Ch R = 1 ,3614    ,62,62,62
BEGIN DESCRIPTION:
Mapping XS e2bd8bb1
END DESCRIPTION:
XS GIS Cut Line= 5
      2982694.11     10076284.56      2982675.88     10076688.24
      2982593.85     10076798.92      2982645.93     10076857.51
      2982963.11     10076898.77
#Sta/Elev= 30
  4506.2  995.82  4581.7  993.56  4615.5  992.32  4665.5   991.7  4675.5  990.57
  4725.6  988.82  4818.9  983.95  4885.8  983.11  4910.3  982.27  4912.6  981.28
  4927.2  980.37  4949.4  979.96    5016  979.06  5018.8  978.56    5022  979.06
  5041.6  982.07  5076.1   984.4    5097  986.88  5111.2  990.07  5127.3  992.11
  5149.2   995.2    5209  995.68    5250  998.24  5310.5  999.74  5325.2 1001.06
  5350.9  1002.4  5360.9 1003.67  5372.3 1007.47  5381.1  1009.3  5446.3 1011.16
#Mann= 8 ,-1 , 0
  4506.2     .16       0  4581.7      .1       0  4818.9     .16       0
  4949.4      .1       0    5016     .07       0    5022      .1       0
  5127.3     .05       0  5325.2      .1       0
Bank Sta=5016,5022
XS Rating Curve= 0 ,0
Exp/Cntr=0.3,0.1

Type RM Length L Ch R = 1 ,3552    ,231,231,231
BEGIN DESCRIPTION:
Mapping XS 24714864
END DESCRIPTION:
XS GIS Cut Line= 5
      2982668.07     10076294.97      2982618.59      10076663.5
      2982528.74      10076791.1      2982600.36     10076886.16
      2982953.22     10076931.73
#Sta/Elev= 30
  4535.4  994.84  4798.5  986.93  4836.8   983.5  4865.1  982.65    4921  981.83
  4935.8  978.98  4944.2  974.58  4950.6  975.35  4953.7  973.31  4956.5  972.81
  4959.7  973.31  5001.1  976.86    5022  976.36  5036.8  979.27  5042.9  977.66
  5051.6  979.61  5057.7  978.48  5061.8  980.14  5079.1   981.8  5133.4  982.64
  5137.4  982.86  5151.1  984.12  5177.7  990.99  5227.6  994.53  5382.1  998.99
  5425.5 1001.72  5438.7 1003.45  5452.6 1007.94  5462.7 1009.25  5538.1 1010.79
#Mann= 9 ,-1 , 0
  4535.4     .16       0  4865.1      .1       0  4953.7     .07       0
  4959.7      .1       0  5133.4     .16       0  5137.4      .1       0
  5227.6     .05       0  5425.5     .16       0  5438.7      .1       0
Bank Sta=4953.7,4959.7
XS Rating Curve= 0 ,0
Exp/Cntr=0.3,0.1

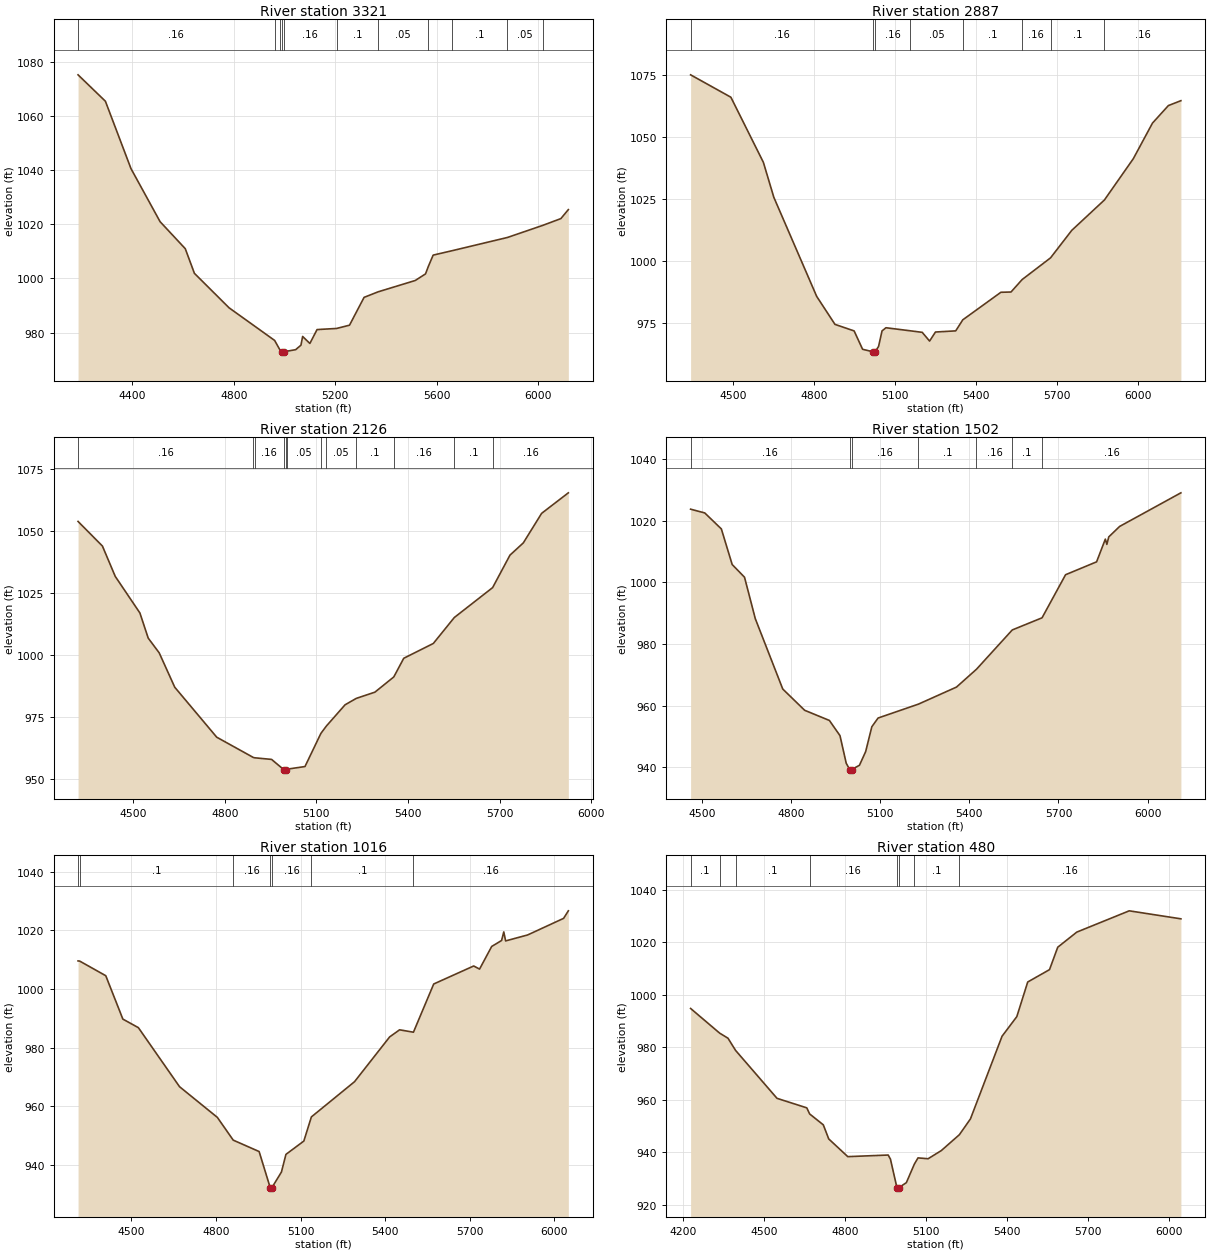
Type RM Length L Ch R = 1 ,3321    ,434,434,434
BEGIN DESCRIPTION:
UNT 1061 IN LATR 8.0
END DESCRIPTION:
XS GIS Cut Line= 4
      2981745.38     10076206.53      2982193.27     10076525.96
       2982564.8     10076935.68      2983387.74     10077025.96
#Sta/Elev= 30
  4186.8 1075.12  4294.5 1065.38  4395.3 1040.51  4509.9 1020.94  4609.1 1010.97
  4645.1 1001.88  4781.5  989.17  4961.1  977.12  4980.9   973.8  4990.7  972.94
  4993.5  972.44  4996.7  972.94  5043.8  973.71  5064.7  975.37  5071.4  978.59
  5099.8  976.01  5128.2  981.13    5205  981.54    5256  982.75  5313.4  993.02
  5368.8  995.06    5515  999.24  5555.3 1001.67  5566.4  1004.4  5585.4  1008.6
  5660.6 1010.24    5878 1015.11  6016.7 1019.56  6088.4 1022.07  6117.9 1025.39
#Mann= 11 ,-1 , 0
  4186.8     .16       0  4961.1      .1       0  4980.9     .16       0
  4990.7     .07       0  4996.7     .16       0    5205      .1       0
  5368.8     .05       0  5566.4     .16       0  5660.6      .1       0
    5878     .05       0  6016.7      .1       0
Bank Sta=4990.7,4996.7
XS Rating Curve= 0 ,0
Exp/Cntr=0.3,0.1

Type RM Length L Ch R = 1 ,2887    ,761,761,761
BEGIN DESCRIPTION:
UNT 1061 IN LATR 6.0
END DESCRIPTION:
XS GIS Cut Line= 4
      2981501.11     10076816.65      2981969.87     10076855.72
       2982382.2     10077584.88      2982793.99     10077883.97
#Sta/Elev= 30
  4341.2 1074.97  4490.4 1065.96  4610.8 1039.76  4649.6 1025.66  4808.4  985.77
  4876.2  974.49  4947.2  971.85  4978.6  964.45  5018.9  963.41  5021.7  962.91
  5024.9  963.41  5037.8   965.6  5050.6  971.86  5065.2  973.13    5156  971.89
  5199.5  971.28  5226.9  967.76  5248.6  971.41  5323.7  971.87  5349.8  976.31
  5491.1  987.41  5528.6  987.52  5569.8  992.53  5675.1 1001.27  5753.8 1012.35
  5874.8 1024.58  5981.8 1041.19  6052.9 1055.53  6111.7 1062.58  6158.2 1064.56
#Mann= 8 ,-1 , 0
  4341.2     .16       0  5018.9     .07       0  5024.9     .16       0
    5156     .05       0  5349.8      .1       0  5569.8     .16       0
  5675.1      .1       0  5874.8     .16       0
Bank Sta=5018.9,5024.9
XS Rating Curve= 0 ,0
Exp/Cntr=0.3,0.1

Type RM Length L Ch R = 1 ,2126    ,624,624,624
BEGIN DESCRIPTION:
UNT 1061 IN LATR 5.0
END DESCRIPTION:
XS GIS Cut Line= 3
      2981240.67      10077341.8      2981561.89     10077558.84
      2982632.16     10078139.48
#Sta/Elev= 30
  4319.6 1053.99  4399.4 1044.05  4441.4  1031.8  4522.1 1017.04  4549.3 1006.89
  4585.3 1000.94  4636.2  987.06  4773.6  966.89  4893.1  958.73  4897.4  958.58
  4953.3  957.92  4994.1  953.69  4996.8  953.19  5000.1  953.69  5002.8  953.96
  5062.6  955.04  5114.7  968.42  5132.4  971.35  5193.8  979.96  5230.3  982.54
  5291.7  985.08  5353.4  991.22    5386  998.75  5482.8 1004.73  5551.5  1015.2
    5677 1027.28  5733.8 1040.39  5777.5 1045.33  5837.4 1057.25  5924.9 1065.54
#Mann= 12 ,-1 , 0
  4319.6     .16       0  4893.1      .1       0  4897.4     .16       0
  4994.1     .07       0  5000.1     .16       0  5002.8     .05       0
  5114.7      .1       0  5132.4     .05       0  5230.3      .1       0
  5353.4     .16       0  5551.5      .1       0    5677     .16       0
Bank Sta=4994.1,5000.1
XS Rating Curve= 0 ,0
Exp/Cntr=0.3,0.1

Type RM Length L Ch R = 1 ,1502    ,486,486,486
BEGIN DESCRIPTION:
UNT 1061 IN LATR 3.0
END DESCRIPTION:
XS GIS Cut Line= 4
      2981049.73     10077775.85      2981344.87     10078023.25
      2981535.84     10078296.69      2982445.35     10078504.58
#Sta/Elev= 30
  4460.8 1023.68  4508.4 1022.47  4564.4 1017.28  4600.8 1005.76  4642.4 1001.64
  4678.8  988.19  4771.2  965.42    4845  958.53  4928.3  955.24    4964  950.32
    4985  941.38  4996.8  939.32  4999.6  938.82  5002.8  939.32  5029.5  940.71
  5050.4  945.12  5071.3   953.2  5092.3  956.02  5228.4  960.53  5356.5  966.05
  5423.8  971.83  5544.4  984.56  5644.7  988.49  5723.9 1002.45  5828.4 1006.62
  5857.9 1013.98    5863 1012.28  5869.4  1014.7    5906 1018.09  6112.4 1028.98
#Mann= 7 ,-1 , 0
  4460.8     .16       0  4996.8     .07       0  5002.8     .16       0
  5228.4      .1       0  5423.8     .16       0  5544.4      .1       0
  5644.7     .16       0
Bank Sta=4996.8,5002.8
XS Rating Curve= 0 ,0
Exp/Cntr=0.3,0.1

Type RM Length L Ch R = 1 ,1016    ,536,536,536
BEGIN DESCRIPTION:
UNT 1061 IN LATR 2.0
END DESCRIPTION:
XS GIS Cut Line= 4
      2980897.81     10078079.65      2981067.09     10078531.07
      2981635.67     10078726.38      2982056.23     10079229.32
#Sta/Elev= 30
  4310.8 1009.58  4316.6 1009.52  4409.1 1004.53  4469.7  989.72  4524.8  986.79
  4670.8  966.63  4804.9  956.16  4861.1   948.4    4953   944.5  4992.3  932.17
    4995  931.67  4998.3  932.17  5032.1   937.5  5048.1  943.53  5111.6  948.08
  5138.3  956.32  5291.3  968.34    5416  983.64  5451.2  986.06  5500.3  985.24
  5572.2  1001.7    5714 1007.85  5734.8 1006.79  5777.8 1014.51  5812.9 1016.55
  5820.7 1019.48  5827.2 1016.41  5905.3 1018.44  6032.9 1024.11  6049.7 1026.68
#Mann= 7 ,-1 , 0
  4310.8     .16       0  4316.6      .1       0  4861.1     .16       0
  4992.3     .07       0  4998.3     .16       0  5138.3      .1       0
  5500.3     .16       0
Bank Sta=4992.3,4998.3
XS Rating Curve= 0 ,0
Exp/Cntr=0.3,0.1

Type RM Length L Ch R = 1 ,480     ,420,420,420
BEGIN DESCRIPTION:
Mapping XS 6f91533d
END DESCRIPTION:
XS GIS Cut Line= 4
      2980821.65     10078306.41      2980923.21     10079014.75
      2981170.61     10079155.37      2981980.46     10079277.76
#Sta/Elev= 30
  4226.8  994.85  4334.4  985.46  4365.5  983.51  4393.6  978.87  4547.4   960.6
  4657.9  956.97  4668.5  954.65  4719.1  950.51  4739.3  945.13    4810  938.38
  4959.9  938.99  4968.2  937.46  4992.5   926.5  4995.3     926  4998.5   926.5
  5027.3  928.46  5056.9  935.51  5070.5   937.9    5108  937.58    5157  940.69
    5224  946.73  5265.2  952.77  5382.4  984.26  5437.2  991.74  5477.6 1004.92
  5558.5 1009.64    5589 1018.18  5659.7 1023.94  5854.3 1032.05    6046    1029
#Mann= 8 ,-1 , 0
  4226.8      .1       0  4334.4     .16       0  4393.6      .1       0
  4668.5     .16       0  4992.5     .07       0  4998.5     .16       0
  5056.9      .1       0    5224     .16       0
Bank Sta=4992.5,4998.5
XS Rating Curve= 0 ,0
Exp/Cntr=0.3,0.1

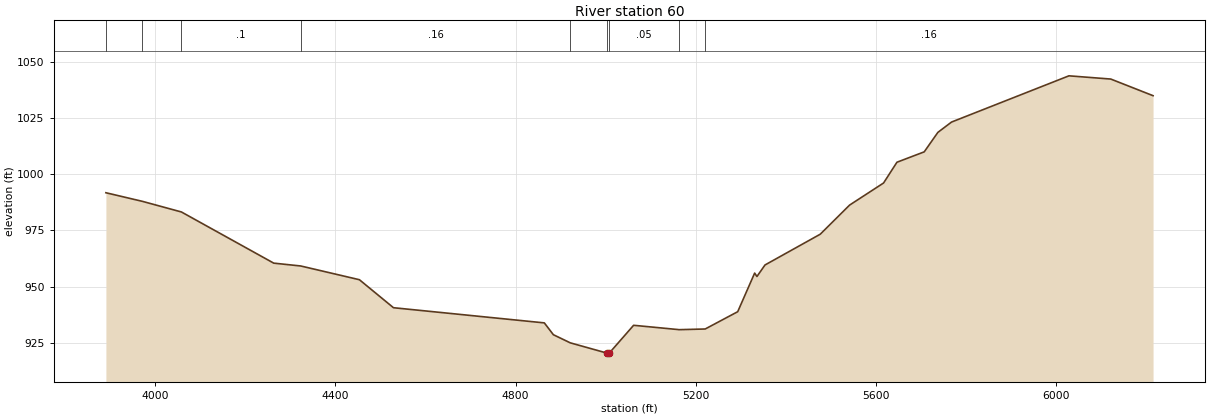
Type RM Length L Ch R = 1 ,60      ,0,0,0
BEGIN DESCRIPTION:
UNT 1061 IN LATR 1.0
END DESCRIPTION:
XS GIS Cut Line= 4
      2980800.82     10078311.65      2980738.32     10079379.33
      2980860.71     10079488.71      2981941.42     10079332.46
#Sta/Elev= 30
  3890.2  991.81  3971.3  987.97  4057.9  983.24  4262.9  960.44  4322.9  959.17
  4453.2  953.05  4528.9  940.57  4863.9  933.81    4884  928.54  4921.5  924.92
  5002.3  920.39  5005.1  919.89  5008.3  920.39  5062.2  932.74  5163.5  930.79
  5221.2  931.09  5293.4   938.8    5331     956  5336.1  954.49    5354  959.62
  5476.7  973.33  5541.9  986.31  5617.3  996.15    5647  1005.4  5707.6 1010.03
  5737.9  1018.7  5768.2  1023.3    6029 1043.91  6121.9 1042.47  6215.8 1035.06
#Mann= 9 ,-1 , 0
  3890.2      .1       0  3971.3     .16       0  4057.9      .1       0
  4322.9     .16       0  4921.5     .05       0  5002.3    .035       0
  5008.3     .05       0  5163.5      .1       0  5221.2     .16       0
Bank Sta=5002.3,5008.3
XS Rating Curve= 0 ,0
Exp/Cntr=0.3,0.1

Chan Stop Cuts=-1
Use User Specified Reach Order=0
Composite Channel Slope=5