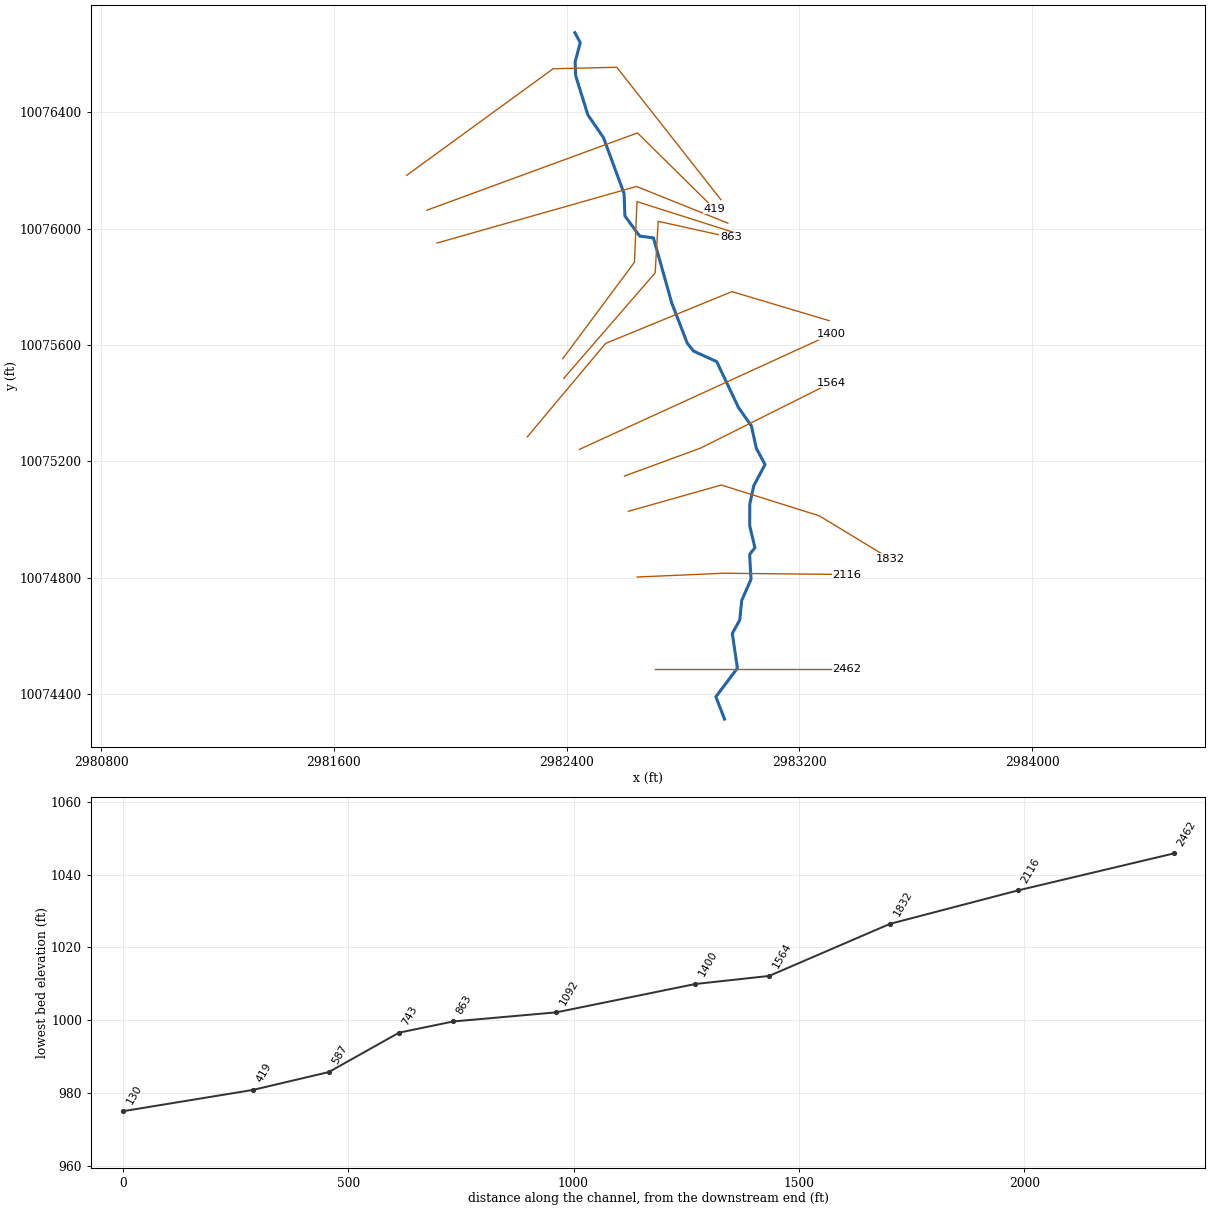
--- UNT 1062 IN LATR.prj (project) ---

Proj Title=UNT 1062 IN LATR Base Level Engineering
Current Plan=p01
Default Exp/Contr=0.3,0.1
English Units
Geom File=g01
Flow File=f01
Plan File=p01
Y Axis Title=Elevation
X Axis Title(PF)=Main Channel Distance
X Axis Title(XS)=Station
BEGIN DESCRIPTION:
UNT 1062 IN LATR
END DESCRIPTION:
DSS Export Rating Curves= 0
DSS Export Rating Curve Sorted= 0
DSS Export Volume Flow Curves= 0
DXF OffsetX= 0
DXF OffsetY= 0
DXF ScaleX= 1
DXF ScaleY= 10

--- UNT 1062 IN LATR.p01 (plan) ---

Plan Title=Multiple Run
Short Identifier=Multiple
Geom File=g01
Flow File=f01
Subcritical Flow
K Sum by GR= 0
Std Step Tol= 0.01
Critical Tol= 0.01
Num of Std Step Trials= 20
Max Error Tol= 0.3
Flow Tol Ratio= 0.001
Split Flow NTrial= 30
Split Flow Tol= 0.02
Split Flow Ratio= 0.02
Log Output Level= 0
Friction Slope Method= 1
Unsteady Friction Slope Method= 2
Unsteady Bridges Friction Slope Method= 1
Parabolic Critical Depth
Global Vel Dist=  1 , 1 , 1
Global Log Level= 0
CheckData=True
Encroach Param= -1, 0, 0, 0
BEGIN DESCRIPTION:
Multiple Run
END DESCRIPTION:

--- UNT 1062 IN LATR.f01 (steady flow) ---

Flow Title=Multiple
Number of Profiles=7
Profile Names=10-year,25-year,50-year,1pct_min,100-year,1pct_plu,500-year
River Rch & RM= UNT 1062 IN LATR,Reach-1,2462
     331     452     552     496     671     908     991
Boundary for River Rch & Prof#=UNT 1062 IN LATR,Reach-1,1
Up Type=0
Dn Type=3
Dn Slope=0.005
Boundary for River Rch & Prof#=UNT 1062 IN LATR,Reach-1,2
Up Type=0
Dn Type=3
Dn Slope=0.005
Boundary for River Rch & Prof#=UNT 1062 IN LATR,Reach-1,3
Up Type=0
Dn Type=3
Dn Slope=0.005
Boundary for River Rch & Prof#=UNT 1062 IN LATR,Reach-1,4
Up Type=0
Dn Type=3
Dn Slope=0.005
Boundary for River Rch & Prof#=UNT 1062 IN LATR,Reach-1,5
Up Type=0
Dn Type=3
Dn Slope=0.005
Boundary for River Rch & Prof#=UNT 1062 IN LATR,Reach-1,6
Up Type=0
Dn Type=3
Dn Slope=0.005
Boundary for River Rch & Prof#=UNT 1062 IN LATR,Reach-1,7
Up Type=0
Dn Type=3
Dn Slope=0.005

--- UNT 1062 IN LATR.g01 (geometry) ---

Geom Title=Existing Conditions
Program Version=4.10

River Reach=UNT 1062 IN LATR,Reach-1
Reach XY= 30
      2982942.71     10074314.56      2982912.95     10074391.31
      2982987.03     10074489.44      2982969.53     10074608.88
      2982995.03     10074655.08      2983001.81     10074722.33
      2983033.75     10074794.98      2983029.05     10074880.34
      2983047.26     10074903.48      2983029.29     10074978.91
      2983029.51     10075053.24      2983043.19     10075116.54
      2983082.01     10075189.34      2983052.09     10075245.12
      2983035.09     10075322.33      2982990.98     10075384.77
      2982915.97     10075542.83      2982836.13     10075579.49
      2982814.57     10075606.55      2982761.24     10075744.98
      2982698.57     10075968.22      2982651.17     10075974.57
      2982600.46     10076043.53      2982597.42     10076121.28
      2982526.65     10076312.98      2982473.11     10076390.94
      2982431.38     10076525.08       2982429.3     10076573.17
      2982447.01     10076639.34      2982428.47     10076673.73

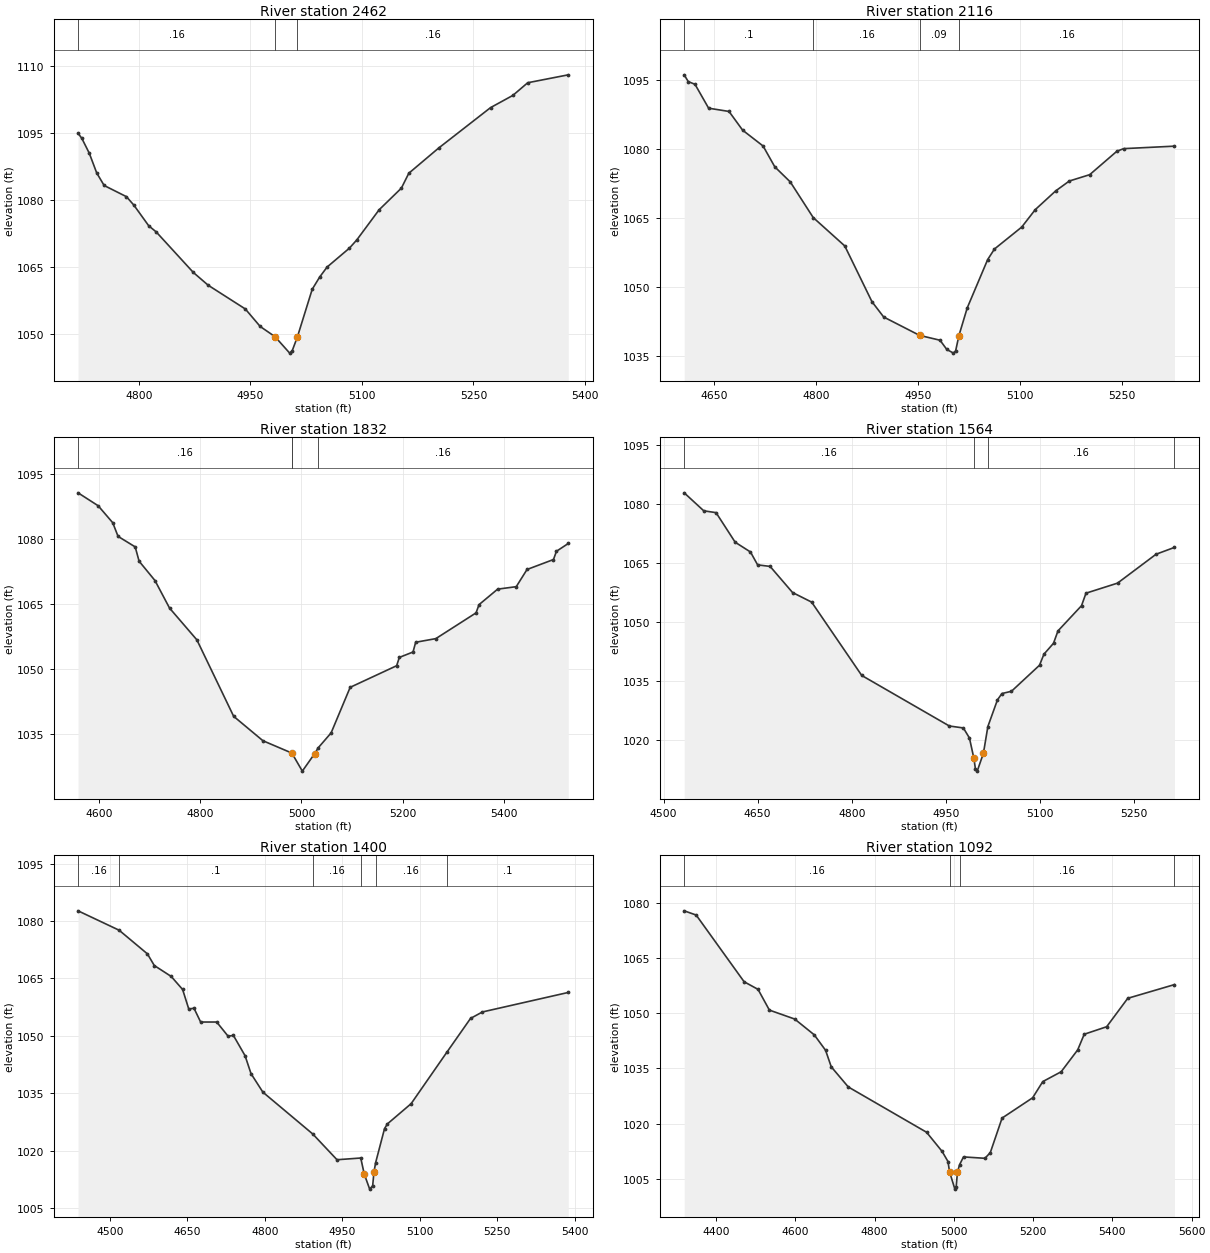
Type RM Length L Ch R = 1 ,2462    ,346,346,346
BEGIN DESCRIPTION:
UNT 1062 IN LATR 5.0
END DESCRIPTION:
XS GIS Cut Line= 2
      2982703.41     10074485.93      2983363.11     10074485.93
#Sta/Elev= 30
    4718 1094.97  4723.1 1093.82  4733.1 1090.51  4743.1  1086.1  4753.1 1083.29
  4783.1 1080.79  4793.1  1078.9  4813.1 1074.28  4823.1 1072.92  4873.1 1063.85
  4893.1 1060.99  4943.1 1055.68  4963.1 1051.77  4983.1 1049.48  5002.8 1045.81
  5006.1 1046.31  5013.1  1049.4  5033.1 1060.08  5043.1 1062.81  5053.1 1065.05
  5083.1 1069.27  5093.1 1071.12  5123.1 1077.85  5153.1  1082.7  5163.1 1086.03
  5203.1 1091.64  5273.1  1100.7  5303.1 1103.43  5323.1 1106.26  5377.7 1108.03
#Mann= 3 , 0 , 0
    4718     .16       0  4983.1     .09       0  5013.1     .16       0
Bank Sta=4983.1,5013.1
XS Rating Curve= 0 ,0
Exp/Cntr=0.3,0.1

Type RM Length L Ch R = 1 ,2116    ,284,284,284
BEGIN DESCRIPTION:
UNT 1062 IN LATR 4.0
END DESCRIPTION:
XS GIS Cut Line= 3
      2982642.61     10074802.77      2982937.75     10074815.79
       2983363.1     10074811.45
#Sta/Elev= 30
  4606.5 1096.04  4612.4 1094.58  4622.4 1093.98  4642.4  1088.8  4672.4 1088.09
  4692.4 1084.03  4722.5 1080.59  4739.7 1076.07  4762.5 1072.79  4796.2 1065.06
  4842.6  1058.9  4882.6 1046.79  4899.8 1043.48  4952.6 1039.49  4982.6 1038.44
  4992.6 1036.44  5002.4 1035.64  5005.6 1036.14 5010.45 1039.46  5022.6 1045.44
  5052.7 1055.95  5062.7 1058.24  5102.7 1062.99  5122.7 1066.79  5152.7 1070.85
  5172.7 1072.99  5202.7 1074.37  5242.7 1079.46  5252.7 1080.02  5327.3 1080.56
#Mann= 4 ,-1 , 0
  4606.5      .1       0  4796.2     .16       0  4952.6     .09       0
 5010.45     .16       0
Bank Sta=4952.6,5010.45
XS Rating Curve= 0 ,0
Exp/Cntr=0.3,0.1

Type RM Length L Ch R = 1 ,1832    ,268,268,268
BEGIN DESCRIPTION:
Mapping XS 97f957f5
END DESCRIPTION:
XS GIS Cut Line= 4
      2982612.36     10075028.69      2982931.82     10075118.97
      2983268.62     10075013.07       2983511.7     10074865.49
#Sta/Elev= 30
  4558.2 1090.74    4598 1087.75  4626.8 1083.83  4637.3 1080.68  4671.2 1078.25
  4678.9 1074.95  4710.3 1070.48  4739.1 1064.12  4793.2 1056.77  4865.9 1039.11
  4923.8 1033.47    4981 1030.62  5001.7 1026.45  5026.2 1030.52  5033.4 1031.88
  5058.6 1035.28  5096.3 1045.81  5188.2  1050.8  5193.5 1052.72  5220.6 1053.97
  5225.8 1056.22  5265.7 1057.06  5345.2 1063.01  5351.1 1064.91  5387.9 1068.49
  5424.7 1069.06    5446 1073.03  5498.3 1075.33  5504.2 1077.24  5527.6 1079.04
#Mann= 4 ,-1 , 0
  4558.2     .16       0    4981      .1       0    4981     .09       0
  5033.4     .16       0
Bank Sta=4981,5026.2
XS Rating Curve= 0 ,0
Exp/Cntr=0.3,0.1

Type RM Length L Ch R = 1 ,1564    ,164,164,164
BEGIN DESCRIPTION:
UNT 1062 IN LATR 3.0
END DESCRIPTION:
XS GIS Cut Line= 3
      2982599.21     10075149.99      2982859.63     10075245.47
      2983310.98     10075471.15
#Sta/Elev= 30
  4532.8 1082.81    4564 1078.24  4583.6 1077.78  4614.1 1070.27  4638.5 1067.79
  4649.9 1064.52  4669.8 1064.13  4705.6  1057.5  4736.1 1055.06    4816 1036.44
  4955.7 1023.61  4978.1 1023.11  4987.8 1020.56  4994.8 1015.46  4997.4 1012.65
  5000.2 1012.15  5010.1 1016.69  5017.2 1023.48  5032.5 1030.25  5039.6 1031.85
  5054.8 1032.42  5099.6 1039.04  5106.6 1041.84  5121.9 1044.61    5129 1047.75
  5166.6 1054.16  5173.7 1057.33    5224 1059.88  5285.5 1067.22  5314.8 1068.95
#Mann= 4 ,-1 , 0
  4532.8     .16       0  4994.8     .09       0  5017.2     .16       0
  5314.8     .05       0
Bank Sta=4994.8,5010.1
XS Rating Curve= 0 ,0
Exp/Cntr=0.3,0.1

Type RM Length L Ch R = 1 ,1400    ,308,308,308
BEGIN DESCRIPTION:
Mapping XS 0c54e4fd
END DESCRIPTION:
XS GIS Cut Line= 2
      2982444.17     10075241.48      2983307.94     10075636.48
#Sta/Elev= 30
    4438 1082.66  4517.6 1077.59  4572.4 1071.41  4585.7 1068.37  4618.5 1065.51
  4640.6  1062.1  4652.5    1057  4662.6 1057.21  4675.5  1053.6  4706.6  1053.6
  4728.6 1049.91    4739 1050.09  4761.6 1044.79  4773.1 1040.11  4796.1 1035.27
  4892.8 1024.33  4939.7 1017.61  4985.7 1018.06  4992.5 1013.86    5003 1009.93
  5008.8 1010.83 5011.36 1014.42  5014.5 1016.83  5031.8 1025.75  5037.3 1026.97
  5083.3 1032.26  5152.4 1045.68  5198.4 1054.54  5221.4 1056.23  5387.8 1061.33
#Mann= 6 ,-1 , 0
    4438     .16       0  4517.6      .1       0  4892.8     .16       0
  4985.7     .07       0  5014.5     .16       0  5152.4      .1       0
Bank Sta=4992.5,5011.36
XS Rating Curve= 0 ,0
Exp/Cntr=0.3,0.1

Type RM Length L Ch R = 1 ,1092    ,229,229,229
BEGIN DESCRIPTION:
UNT 1062 IN LATR 2.0
END DESCRIPTION:
XS GIS Cut Line= 4
      2982265.01     10075284.53      2982534.11     10075605.72
      2982968.14     10075783.67      2983302.33     10075683.84
#Sta/Elev= 30
  4319.7  1077.9  4349.9 1076.75  4470.8  1058.6    4506 1056.52  4534.6 1050.88
  4598.4 1048.45  4647.8 1044.15  4676.4 1039.94  4690.7 1035.44  4733.7 1029.96
  4931.2 1017.63  4970.4 1012.42  4985.3 1009.65 4989.09 1006.91  5002.6 1002.15
  5005.8 1002.65  5009.2 1006.84  5014.7 1008.85  5024.4 1010.92  5078.5 1010.54
    5092 1012.09  5121.7 1021.49  5198.8 1027.01  5224.4 1031.42  5270.8  1034.1
  5312.5 1040.05    5329 1044.31  5385.6 1046.35  5438.8 1054.09  5556.6 1057.82
#Mann= 4 ,-1 , 0
  4319.7     .16       0 4989.09     .09       0  5014.7     .16       0
  5556.6      .1       0
Bank Sta=4989.09,5009.2
XS Rating Curve= 0 ,0
Exp/Cntr=0.3,0.1

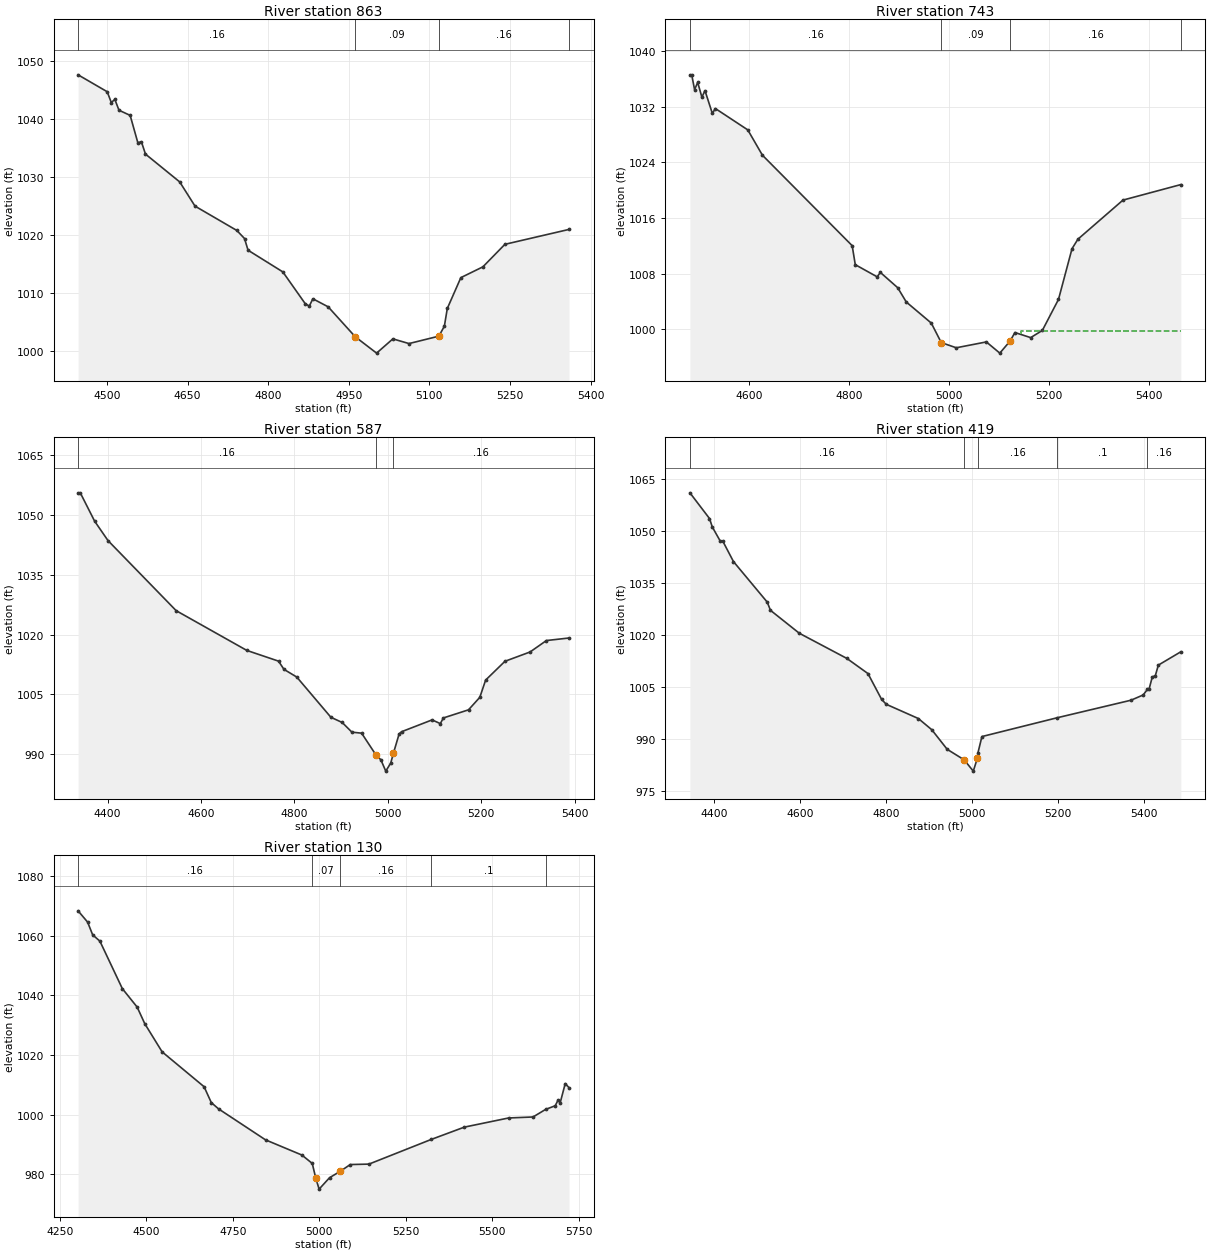
Type RM Length L Ch R = 1 ,863     ,120,120,120
BEGIN DESCRIPTION:
Mapping XS 24f46552
END DESCRIPTION:
XS GIS Cut Line= 4
      2982390.15     10075485.29      2982704.38     10075848.14
       2982714.8     10076025.22      2982964.99     10075970.01
#Sta/Elev= 30
  4446.3 1047.67  4500.5 1044.75  4508.1 1042.89  4514.7 1043.43  4522.4 1041.56
  4543.2 1040.67  4557.5 1035.95  4564.1 1036.12  4571.7 1033.99  4635.4 1029.19
  4663.9 1025.01  4741.7 1020.81    4756 1019.42  4762.6  1017.4  4827.3 1013.66
    4869 1008.17  4876.6 1007.76  4883.2 1009.02  4911.7 1007.63    4962 1002.47
  5001.8  999.64  5032.1  1002.1  5062.1 1001.29  5117.7 1002.57  5127.9 1004.28
  5133.4 1007.35  5158.6 1012.67  5199.6 1014.53  5240.6 1018.42  5359.9 1020.99
#Mann= 4 ,-1 , 0
  4446.3     .16       0    4962     .09       0  5117.7     .16       0
  5359.9     .16       0
Bank Sta=4962,5117.7
XS Rating Curve= 0 ,0
Exp/Cntr=0.3,0.1

Type RM Length L Ch R = 1 ,743     ,156,156,156
BEGIN DESCRIPTION:
Mapping XS 7ae958d5
END DESCRIPTION:
XS GIS Cut Line= 4
      2982386.67     10075552.99       2982633.2      10075884.6
      2982641.88     10076092.93      2982984.53     10075983.91
#Sta/Elev= 30
  4481.9 1036.56  4485.5 1036.56  4491.2 1034.43  4497.4 1035.47  4505.8 1033.35
    4512 1034.29  4526.6 1031.03  4532.9 1031.71  4597.5 1028.65  4626.8 1025.01
  4806.2 1012.01  4812.4 1009.28  4856.2 1007.53  4862.5 1008.17  4897.2 1005.97
  4914.3 1003.92  4964.3 1000.89  4984.3  998.08  5014.3  997.34  5074.4  998.18
  5101.3  996.57  5121.9  998.31  5131.5  999.53    5163   998.8  5186.3  999.83
  5218.6 1004.29  5245.6 1011.57  5257.4 1012.94  5347.5 1018.56  5463.2 1020.79
#Mann= 4 ,-1 , 0
  4481.9     .16       0  4984.3     .09       0  5121.9     .16       0
  5463.2     .16       0
#XS Ineff= 2 , 0
                         5143.18          999.76
Permanent Ineff=
       F       F
Bank Sta=4984.3,5121.9
XS Rating Curve= 0 ,0
Exp/Cntr=0.3,0.1

Type RM Length L Ch R = 1 ,587     ,168,168,168
BEGIN DESCRIPTION:
Mapping XS f4472017
END DESCRIPTION:
XS GIS Cut Line= 3
      2981954.41     10075950.58      2982640.15     10076145.01
      2982954.25     10076019.03
#Sta/Elev= 30
  4336.9  1055.6  4341.6  1055.6  4372.3 1048.49  4400.9 1043.62  4546.9 1026.02
  4698.2 1016.04  4766.1 1013.35  4777.7 1011.29  4805.2 1009.35  4878.2  999.26
  4902.4  997.95  4923.2  995.52    4944  995.27  4975.2  989.71  4985.2   988.6
  4995.7  985.74  5006.3  987.74 5012.05  990.21  5024.3  995.08  5029.5  995.63
  5094.9   998.6  5112.5  997.67  5119.1  999.09  5172.9 1001.13  5197.1 1004.27
  5209.5 1008.59  5250.9 1013.31  5304.7 1015.65  5339.7 1018.52  5388.1 1019.16
#Mann= 3 , 0 , 0
  4336.9     .16       0  4975.2     .07       0 5012.05     .16       0
Bank Sta=4975.2,5012.05
XS Rating Curve= 0 ,0
Exp/Cntr=0.3,0.1

Type RM Length L Ch R = 1 ,419     ,289,289,289
BEGIN DESCRIPTION:
Mapping XS d2ec1ced
END DESCRIPTION:
XS GIS Cut Line= 3
      2981919.69     10076063.43      2982643.62     10076329.04
      2982907.46     10076068.67
#Sta/Elev= 30
  4343.4 1061.02  4388.9 1053.62  4395.4 1051.19  4414.1 1047.07  4419.4  1047.2
  4444.6 1041.22  4523.2 1029.53  4530.7 1027.17  4597.7 1020.57  4708.4 1013.31
  4757.5 1008.94  4789.2 1001.51  4800.1 1000.09  4874.7  995.99  4905.9  992.77
  4941.7  987.13  4981.2  984.09  5002.4  980.84 5012.16  984.63  5013.2  986.08
  5022.5   990.8  5197.6  996.22  5369.2 1001.27  5397.5 1002.78  5407.3 1004.37
  5411.6 1004.64  5418.7 1007.95  5425.8 1008.34  5432.8 1011.38  5485.2 1015.23
#Mann= 5 ,-1 , 0
  4343.4     .16       0  4981.2     .07       0  5013.2     .16       0
  5197.6      .1       0  5407.3     .16       0
Bank Sta=4981.2,5012.16
XS Rating Curve= 0 ,0
Exp/Cntr=0.3,0.1

Type RM Length L Ch R = 1 ,130     ,0,0,0
BEGIN DESCRIPTION:
UNT 1062 IN LATR 1.0
END DESCRIPTION:
XS GIS Cut Line= 4
      2981850.23     10076183.22      2982353.69     10076549.53
      2982572.44     10076554.74      2982930.11     10076099.84
#Sta/Elev= 30
  4302.4  1068.4  4329.9 1064.62  4344.6 1060.33  4365.5 1058.22  4430.4 1042.28
  4473.3 1036.08  4495.3 1030.51  4545.5 1021.06  4666.9 1009.35  4687.7 1004.03
  4708.6 1001.93  4844.6  991.52  4949.8  986.42  4979.8   983.6  4989.8  978.73
  4999.6  974.98  5029.8  978.82  5059.8   980.9  5089.8  983.23  5143.8  983.38
  5323.5  991.64  5419.6  995.79  5547.9  998.87  5618.4   999.2  5654.6 1001.73
  5682.6 1002.97  5690.7 1004.86    5697 1003.99  5711.5 1010.41  5722.5 1009.04
#Mann= 5 ,-1 , 0
  4302.4     .16       0  4979.8     .07       0  5059.8     .16       0
  5323.5      .1       0  5654.6     .16       0
Bank Sta=4989.8,5059.8
XS Rating Curve= 0 ,0
Exp/Cntr=0.3,0.1

Chan Stop Cuts=-1
Use User Specified Reach Order=0
Composite Channel Slope=5