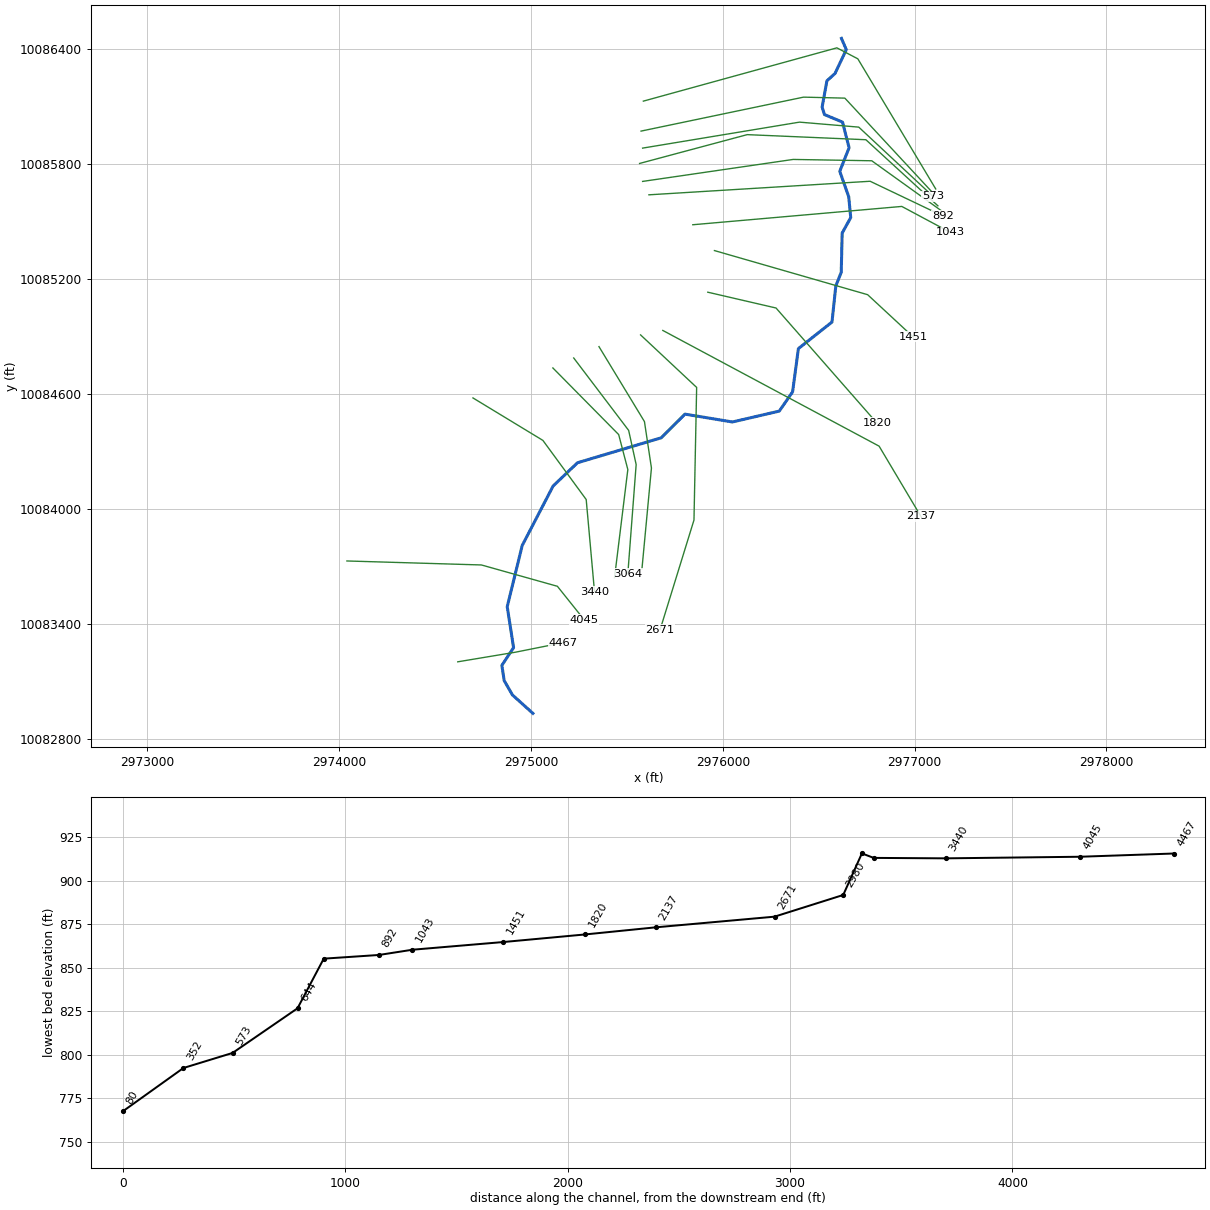
--- UNT 1063 IN LATR.prj (project) ---

Proj Title=UNT 1063 IN LATR Base Level Engineering
Current Plan=p01
Default Exp/Contr=0.3,0.1
English Units
Geom File=g01
Flow File=f01
Plan File=p01
Y Axis Title=Elevation
X Axis Title(PF)=Main Channel Distance
X Axis Title(XS)=Station
BEGIN DESCRIPTION:
UNT 1063 IN LATR
END DESCRIPTION:
DSS Export Rating Curves= 0
DSS Export Rating Curve Sorted= 0
DSS Export Volume Flow Curves= 0
DXF OffsetX= 0
DXF OffsetY= 0
DXF ScaleX= 1
DXF ScaleY= 10

--- UNT 1063 IN LATR.p01 (plan) ---

Plan Title=Multiple Run
Short Identifier=Multiple
Geom File=g01
Flow File=f01
Subcritical Flow
K Sum by GR= 0
Std Step Tol= 0.01
Critical Tol= 0.01
Num of Std Step Trials= 20
Max Error Tol= 0.3
Flow Tol Ratio= 0.001
Split Flow NTrial= 30
Split Flow Tol= 0.02
Split Flow Ratio= 0.02
Log Output Level= 0
Friction Slope Method= 1
Unsteady Friction Slope Method= 2
Unsteady Bridges Friction Slope Method= 1
Parabolic Critical Depth
Global Vel Dist=  1 , 1 , 1
Global Log Level= 0
CheckData=True
Encroach Param= -1, 0, 0, 0
BEGIN DESCRIPTION:
Multiple Run
END DESCRIPTION:

--- UNT 1063 IN LATR.f01 (steady flow) ---

Flow Title=Multiple
Number of Profiles=7
Profile Names=10-year,25-year,50-year,1pct_min,100-year,1pct_plu,500-year
River Rch & RM= UNT 1063 IN LATR,Reach-1,4467
     653     936    1180    1091    1476    1996    2316
River Rch & RM= UNT 1063 IN LATR,Reach-1,2137
     911    1336    1710    1604    2170    2934    3505
Boundary for River Rch & Prof#=UNT 1063 IN LATR,Reach-1,1
Up Type=0
Dn Type=3
Dn Slope=0.005
Boundary for River Rch & Prof#=UNT 1063 IN LATR,Reach-1,2
Up Type=0
Dn Type=3
Dn Slope=0.005
Boundary for River Rch & Prof#=UNT 1063 IN LATR,Reach-1,3
Up Type=0
Dn Type=3
Dn Slope=0.005
Boundary for River Rch & Prof#=UNT 1063 IN LATR,Reach-1,4
Up Type=0
Dn Type=3
Dn Slope=0.005
Boundary for River Rch & Prof#=UNT 1063 IN LATR,Reach-1,5
Up Type=0
Dn Type=3
Dn Slope=0.005
Boundary for River Rch & Prof#=UNT 1063 IN LATR,Reach-1,6
Up Type=0
Dn Type=3
Dn Slope=0.005
Boundary for River Rch & Prof#=UNT 1063 IN LATR,Reach-1,7
Up Type=0
Dn Type=3
Dn Slope=0.005

--- UNT 1063 IN LATR.g01 (geometry) ---

Geom Title=Existing Conditions
Program Version=4.10

River Reach=UNT 1063 IN LATR,Reach-1
Reach XY= 30
      2975010.21     10082934.97      2974903.46     10083031.07
      2974860.51     10083105.96       2974848.4     10083185.09
      2974909.43     10083277.66      2974876.33     10083491.06
      2974954.43       10083810.      2975115.57     10084120.13
      2975242.65     10084241.41      2975679.24      10084371.5
      2975802.73     10084494.86      2976050.12     10084453.95
      2976294.62     10084510.67      2976363.86      10084610.9
      2976394.07      10084836.4       2976569.2     10084974.81
      2976589.24     10085163.28      2976617.36     10085234.18
      2976622.33     10085438.82      2976666.96     10085519.45
      2976656.32     10085628.38       2976609.8     10085760.72
      2976658.45     10085883.51      2976624.17     10086016.92
      2976529.88     10086056.38      2976517.88     10086095.55
      2976542.73     10086232.24      2976585.04     10086270.58
      2976643.83     10086394.77      2976618.47     10086453.73

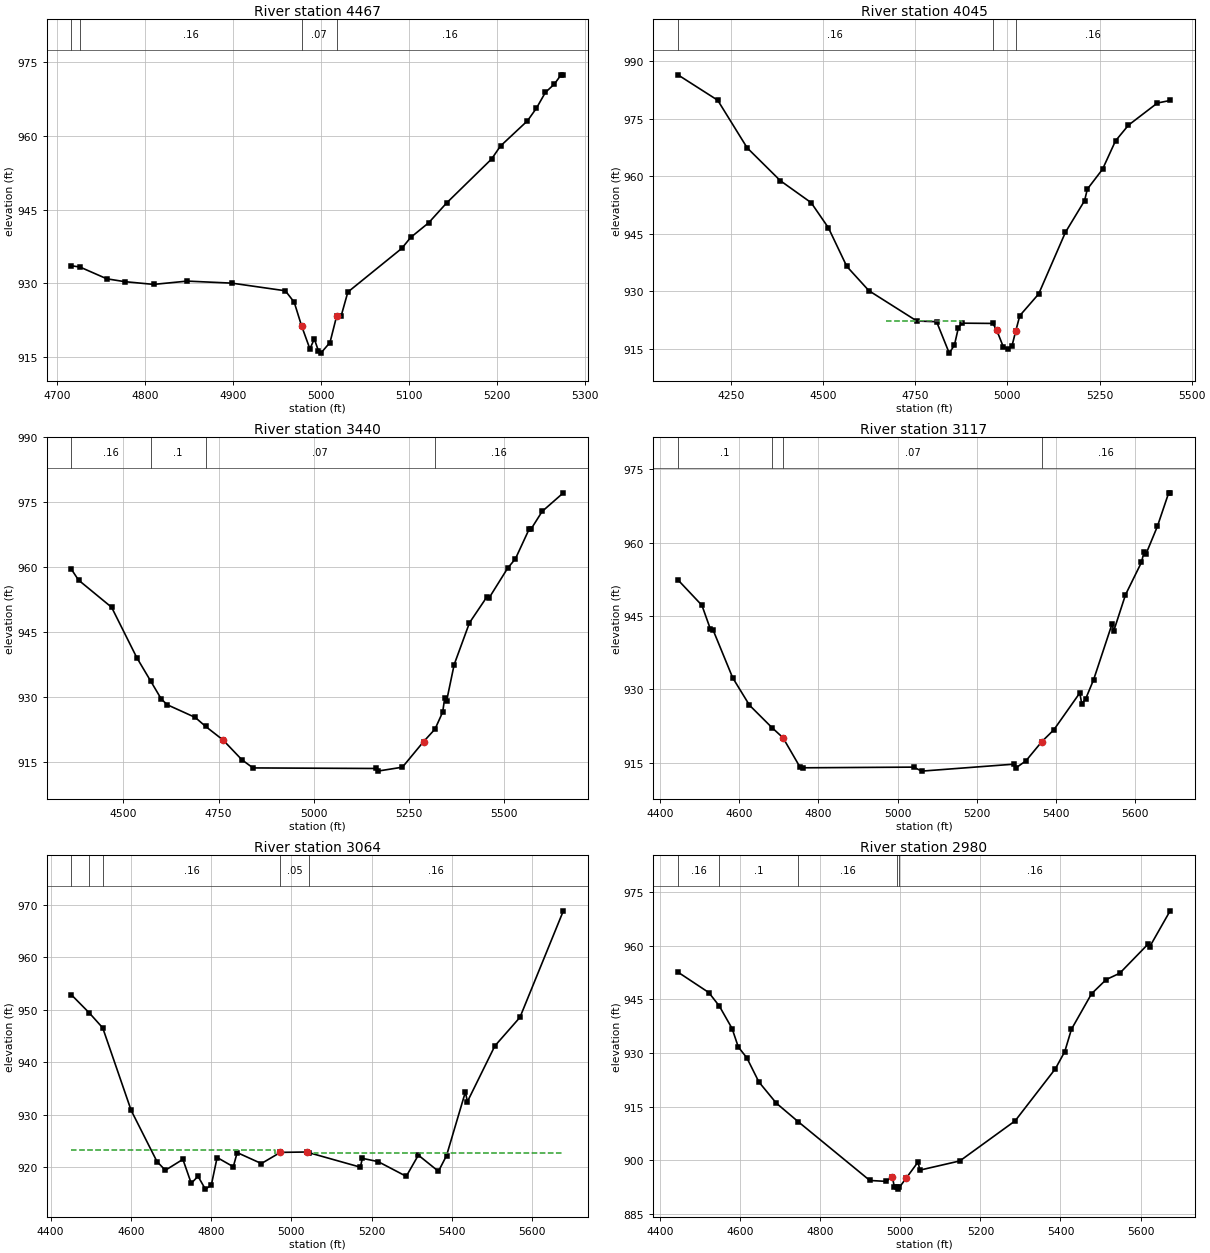
Type RM Length L Ch R = 1 ,4467    ,422,422,422
BEGIN DESCRIPTION:
UNT 1063 IN LATR 10.0
END DESCRIPTION:
XS GIS Cut Line= 3
       2974618.5     10083203.74      2974918.47     10083253.73
      2975168.51     10083303.74
#Sta/Elev= 30
  4715.9  933.57    4726  933.29  4756.4   930.9  4776.7  930.32  4809.6  929.76
  4847.7  930.43  4898.3  930.02  4959.2  928.46  4969.3  926.12  4977.6  921.33
  4987.1  916.62  4992.1  918.65  4996.7  916.26  4999.5  915.76  5009.9  917.92
  5017.5  923.33  5022.6  923.33  5030.2   928.2  5091.4  937.09  5101.6  939.33
    5122  942.31  5142.4  946.35  5193.4  955.29  5203.6  957.95  5234.2  963.08
  5244.4  965.65  5254.6  968.87  5264.8  970.57  5272.4  972.45    5275  972.45
#Mann= 4 ,-1 , 0
  4715.9     .05       0    4726     .16       0  4977.6     .07       0
  5017.5     .16       0
Bank Sta=4977.6,5017.5
XS Rating Curve= 0 ,0
Exp/Cntr=0.3,0.1

Type RM Length L Ch R = 1 ,4045    ,605,605,605
BEGIN DESCRIPTION:
Mapping XS 8ea4765a
END DESCRIPTION:
XS GIS Cut Line= 4
      2974040.61     10083729.42      2974742.01     10083708.58
      2975137.84     10083597.47      2975276.75     10083423.84
#Sta/Elev= 30
  4106.4  986.52  4214.3  979.89  4294.3  967.46  4384.4  958.88  4467.8  953.16
  4514.4  946.64  4564.5  936.53  4624.5  930.19  4754.5  922.28  4808.1   922.1
  4842.4   913.9  4856.4  915.97  4866.8  920.37  4876.8  921.72  4960.5  921.65
  4970.6  920.03  4989.4  915.45  5001.8  915.06  5012.2  915.63  5022.5  919.57
  5033.8  923.68  5084.9  929.33  5157.6  945.43  5209.4  953.66    5217  956.69
  5258.2  961.88  5293.4  969.28  5328.6  973.39    5407  979.16  5441.6  979.83
#Mann= 3 ,-1 , 0
  4106.4     .16       0  4960.5     .13       0  5022.5     .16       0
#XS Ineff= 1 ,-1
    4670 4877.27  922.22
Permanent Ineff=
       T
Bank Sta=4970.6,5022.5
XS Rating Curve= 0 ,0
Exp/Cntr=0.3,0.1

Type RM Length L Ch R = 1 ,3440    ,323,323,323
BEGIN DESCRIPTION:
Mapping XS 4ebb5776
END DESCRIPTION:
XS GIS Cut Line= 4
       2974697.7     10084579.26      2975062.32     10084357.89
      2975288.01     10084049.73      2975331.39     10083568.31
#Sta/Elev= 30
  4362.9  959.62  4382.3  957.04  4469.1  950.77  4535.4  939.12  4572.2  933.67
  4599.4  929.62  4614.9   928.3  4688.5  925.37  4715.7   923.3  4761.6  920.16
  4810.8  915.62  4840.1  913.72    5162  913.59  5167.3  912.98  5232.4  913.89
  5287.9  919.79    5318  922.68  5338.1  926.61  5343.4  929.89  5348.4   929.2
  5368.2  937.55  5408.4   947.2  5454.3  953.19  5459.3  952.85  5508.8  959.82
  5528.9  961.94  5565.3  968.86  5570.3  968.86  5599.2  972.89  5654.8  977.17
#Mann= 4 ,-1 , 0
  4362.9     .16       0  4572.2      .1       0  4715.7     .07       0
    5318     .16       0
Bank Sta=4761.6,5287.9
XS Rating Curve= 0 ,0
Exp/Cntr=0.3,0.1

Type RM Length L Ch R = 1 ,3117    ,53,53,53
BEGIN DESCRIPTION:
UNT 1063 IN LATR 9.0
END DESCRIPTION:
XS GIS Cut Line= 4
      2975114.38     10084735.52      2975457.29     10084388.27
      2975505.03     10084205.98      2975435.58      10083641.7
#Sta/Elev= 30
  4444.5  952.38  4505.2  947.17  4526.4  942.35  4533.5  942.11    4583  932.35
  4625.5  926.73  4682.3  922.15  4710.3  920.07  4752.7  914.15  4759.8  913.92
  5040.8  914.06    5061  913.24  5293.5  914.66  5298.5  913.85  5324.7  915.34
    5365  919.28  5395.3  921.69    5461  929.24    5466     927  5475.9  928.04
    5496  931.96  5542.2  943.26  5547.2  942.01  5576.6  949.33  5616.9  955.96
  5623.4  958.06  5628.5  957.69  5657.2  963.31  5685.9  970.19  5689.5  970.19
#Mann= 4 ,-1 , 0
  4444.5      .1       0  4682.3     .05       0  4710.3     .07       0
    5365     .16       0
Bank Sta=4710.3,5365
XS Rating Curve= 0 ,0
Exp/Cntr=0.3,0.1

Type RM Length L Ch R = 1 ,3064    ,84,84,84
BEGIN DESCRIPTION:
UNT 1063 IN LATR 8.0
END DESCRIPTION:
XS GIS Cut Line= 4
      2975222.94     10084787.54      2975509.37     10084409.97
      2975548.43     10084232.02      2975505.03     10083663.48
#Sta/Elev= 30
  4451.2  952.93  4496.4  949.43  4529.9  946.57  4600.7  930.84  4665.1  921.07
  4685.9  919.42  4729.6   921.5  4750.4  916.93  4767.3  918.27  4785.5  915.82
  4800.3  916.56  4814.9  921.85  4855.2  920.09  4864.8  922.79  4925.1   920.7
  4972.5  922.83  5038.3   922.9  5044.1  922.76  5171.7  920.01  5176.7  921.69
  5215.9  921.07  5286.1  918.26  5316.2   922.3  5366.3  919.22  5386.4  922.21
  5433.4  934.35  5438.4   932.5  5506.8  943.13  5569.3  948.58  5677.5   968.9
#Mann= 5 ,-1 , 0
  4451.2     .16       0  4496.4      .1       0  4529.9     .16       0
  4972.5     .05       0  5044.1     .16       0
#XS Ineff= 2 , 0
            4960  923.29 5055.75          922.63
Permanent Ineff=
       T       T
Bank Sta=4972.5,5038.3
XS Rating Curve= 0 ,0
Exp/Cntr=0.3,0.1

Type RM Length L Ch R = 1 ,2980    ,309,309,309
BEGIN DESCRIPTION:
UNT 1063 IN LATR 7.0
END DESCRIPTION:
XS GIS Cut Line= 4
      2975354.65     10084846.73      2975591.64     10084456.08
       2975628.1      10084213.9      2975578.66     10083688.25
#Sta/Elev= 30
  4444.2  952.62  4521.4   946.9  4547.8   943.1  4579.6  936.82    4595  931.68
  4616.4  928.64  4646.5  921.88    4690  915.96  4744.5  910.79  4923.7  894.32
  4964.2  894.07    4980  895.39    4985  892.44  4991.5   892.4  4994.3   891.9
  4997.5   892.4  5014.7     895  5043.9  899.45  5048.9  897.22  5148.6  899.79
  5286.8  911.01  5387.3  925.58  5410.7  930.37  5427.4  936.63  5477.7  946.57
  5514.3  950.54    5548   952.3  5617.9  960.35    5623  959.72    5674  969.77
#Mann= 5 ,-1 , 0
  4444.2     .16       0  4547.8      .1       0  4744.5     .16       0
  4991.5     .07       0  4997.5     .16       0
Bank Sta=4980,5014.7
XS Rating Curve= 0 ,0
Exp/Cntr=0.3,0.1

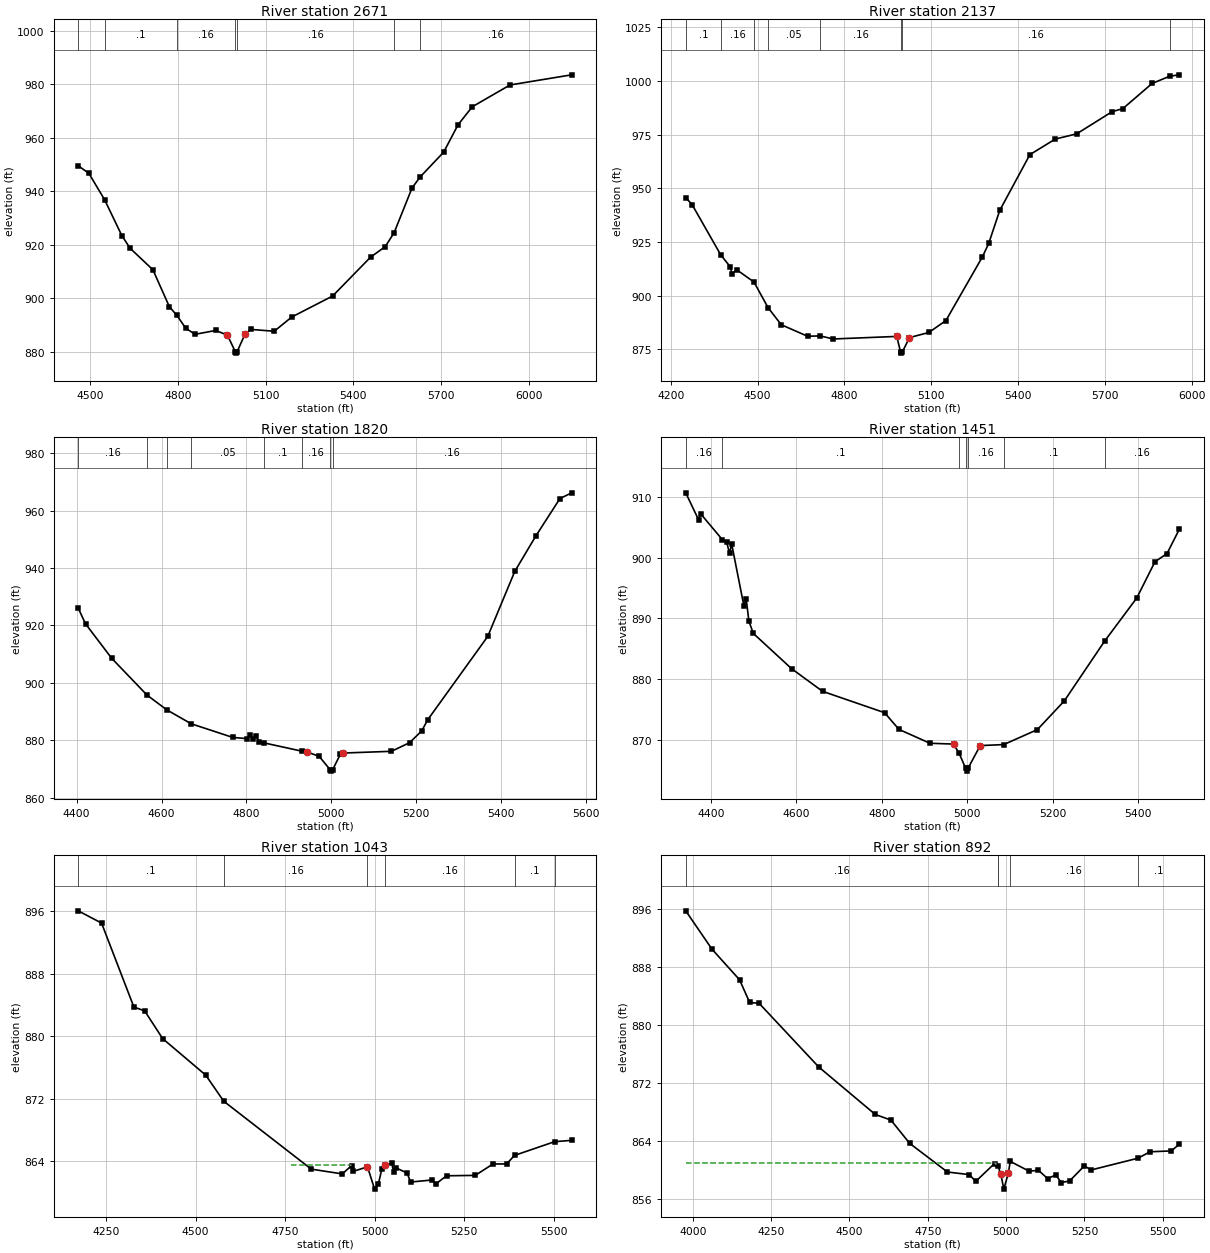
Type RM Length L Ch R = 1 ,2671    ,534,534,534
BEGIN DESCRIPTION:
UNT 1063 IN LATR 6.0
END DESCRIPTION:
XS GIS Cut Line= 4
      2975571.45     10084907.81      2975863.74     10084634.07
      2975849.82     10083942.74      2975673.51     10083372.08
#Sta/Elev= 30
  4458.1  949.47  4494.5  946.63  4548.5  936.75  4607.3  923.38  4635.6  918.64
  4713.8  910.57    4770   896.8  4795.6  893.56  4826.6  888.67  4858.4  886.46
  4928.9  887.89  4968.9  886.14  4995.9  879.92  4998.7  879.42  5001.9  879.92
  5028.9  886.48  5048.9  888.29    5129  887.59    5189  892.91    5329  900.77
    5459  915.31    5509  919.22  5539.5  924.44  5600.8  941.15  5628.7  945.29
  5709.1  954.54  5758.3  964.78  5807.1  971.52  5936.2  979.66  6147.3  983.45
#Mann= 7 ,-1 , 0
  4458.1     .16       0  4548.5      .1       0  4795.6     .16       0
  4995.9     .07       0  5001.9     .16       0  5539.5      .1       0
  5628.7     .16       0
Bank Sta=4968.9,5028.9
XS Rating Curve= 0 ,0
Exp/Cntr=0.3,0.1

Type RM Length L Ch R = 1 ,2137    ,317,317,317
BEGIN DESCRIPTION:
UNT 1063 IN LATR 5.0
END DESCRIPTION:
XS GIS Cut Line= 3
      2975687.41     10084931.03      2976814.89     10084327.85
      2977032.97      10083961.3
#Sta/Elev= 30
  4251.9  945.73    4274  942.41  4373.2  918.97  4405.7  913.51  4411.9  910.18
  4427.6  912.15  4487.7   906.4  4536.3  894.49    4582  886.51  4672.7  881.16
  4716.7   881.3  4761.7  879.88  4981.1  881.07  4994.3  873.79  4997.1  873.29
  5000.3  873.79    5025  880.52  5092.3  882.92  5150.9  888.45  5276.9  918.07
  5298.8  924.34    5337  939.75  5441.1  965.71  5528.8  972.96  5602.7  975.39
  5725.4  985.73  5762.4  987.14  5863.6  998.87  5923.9 1002.22  5957.1 1002.88
#Mann= 8 ,-1 , 0
  4251.9      .1       0  4373.2     .16       0  4487.7      .1       0
  4536.3     .05       0  4716.7     .16       0  4994.3     .07       0
  5000.3     .16       0  5923.9     .08       0
Bank Sta=4981.1,5025
XS Rating Curve= 0 ,0
Exp/Cntr=0.3,0.1

Type RM Length L Ch R = 1 ,1820    ,369,369,369
BEGIN DESCRIPTION:
UNT 1063 IN LATR 4.0
END DESCRIPTION:
XS GIS Cut Line= 3
      2975921.71     10085130.45       2976277.6     10085047.99
      2976802.77     10084449.04
#Sta/Elev= 30
  4403.9  926.05  4421.1  920.58  4482.7  908.57  4565.8  895.73  4612.1  890.61
  4669.8  885.72  4767.6  880.97  4801.5  880.53  4808.3  881.84  4814.9  880.34
  4822.5  881.48  4829.2  879.49  4841.6  879.04  4930.9  876.15    4943   875.9
  4971.5  874.31    4997   869.7  4999.7   869.2    5003   869.7  5020.9  875.02
  5027.6  875.51  5141.4  876.11  5184.1  879.12  5212.6   883.2  5226.8  887.11
  5368.2  916.19  5431.8  938.86  5481.1  951.15  5538.1  964.27  5565.8  966.27
#Mann= 8 ,-1 , 0
  4403.9     .16       0  4565.8      .1       0  4612.1     .16       0
  4669.8     .05       0  4841.6      .1       0  4930.9     .16       0
    4997     .07       0    5003     .16       0
Bank Sta=4943,5027.6
XS Rating Curve= 0 ,0
Exp/Cntr=0.3,0.1

Type RM Length L Ch R = 1 ,1451    ,408,408,408
BEGIN DESCRIPTION:
UNT 1063 IN LATR 3.0
END DESCRIPTION:
XS GIS Cut Line= 3
      2975956.42     10085347.47      2976755.03     10085117.44
      2976992.19     10084897.53
#Sta/Elev= 30
  4341.1  910.68    4371  906.26  4376.2  907.21  4426.6  902.98  4436.9  902.51
  4443.5  900.77  4448.7  902.22  4477.2  892.03  4482.4  893.26  4488.9  889.53
  4499.3  887.51  4588.6  881.71  4661.2  877.97  4806.3  874.45  4839.9   871.7
  4912.5  869.41  4967.6  869.28  4980.9  867.73  4995.8  865.32  4998.6  864.82
  5001.8  865.32  5030.1  869.03  5084.9  869.19  5163.8  871.66  5226.8  876.39
  5320.9  886.22  5396.4  893.36  5438.9  899.32  5467.2  900.68  5495.6  904.64
#Mann= 7 ,-1 , 0
  4341.1     .16       0  4426.6      .1       0  4980.9     .16       0
  4995.8     .07       0  5001.8     .16       0  5084.9      .1       0
  5320.9     .16       0
Bank Sta=4967.6,5030.1
XS Rating Curve= 0 ,0
Exp/Cntr=0.3,0.1

Type RM Length L Ch R = 1 ,1043    ,151,151,151
BEGIN DESCRIPTION:
UNT 1063 IN LATR 2.0
END DESCRIPTION:
XS GIS Cut Line= 3
      2975843.54     10085482.02      2976932.98     10085577.51
      2977184.05     10085443.31
#Sta/Elev= 30
    4172  896.06  4237.2  894.49  4327.5  883.73  4357.6  883.24  4407.8  879.69
  4528.3     875  4578.5  871.66    4823  862.96  4909.7  862.35  4935.5  863.42
  4940.5  862.68    4980  863.26  4999.8   860.4  5010.1  861.03  5020.2  862.99
  5030.2  863.55  5047.9  863.69  5052.9  862.63  5060.3  863.11  5090.4  862.46
  5100.5  861.31  5160.4  861.57  5170.7  861.06  5200.9  862.11  5280.9  862.16
  5330.4  863.62  5368.6  863.63  5390.6  864.72  5502.5  866.48  5550.3  866.65
#Mann= 6 ,-1 , 0
    4172      .1       0  4578.5     .16       0    4980     .07       0
  5030.2     .16       0  5390.6      .1       0  5502.5     .05       0
#XS Ineff= 2 ,-1
 4767.67 4933.47  863.48 5046.22 5377.82  863.67
Permanent Ineff=
       T       T
Bank Sta=4980,5030.2
XS Rating Curve= 0 ,0
Exp/Cntr=0.3,0.1

Type RM Length L Ch R = 1 ,892     ,248,248,248
BEGIN DESCRIPTION:
Mapping XS f9a362d8
END DESCRIPTION:
XS GIS Cut Line= 3
      2975614.84     10085638.04        2976768.     10085708.73
      2977146.73     10085528.18
#Sta/Elev= 30
  3977.7  895.76  4061.5  890.47  4149.5  886.25  4181.7  883.12  4211.8  883.01
  4402.1  874.23  4582.5  867.68  4632.6   866.9  4692.7  863.68  4812.9  859.74
    4883  859.38  4903.1  858.44  4963.2  860.91  4973.9  860.62  4983.2  859.45
    4993  857.38 5007.56  859.63  5013.3  861.21  5073.4  859.86  5103.4  859.97
    5133  858.83  5158.8  859.34  5175.9  858.29  5202.7   858.5  5249.5  860.57
  5272.2  860.03  5421.6  861.65  5459.4  862.53  5527.4  862.65  5552.6  863.56
#Mann= 5 ,-1 , 0
  3977.7     .16       0  4973.9      .1       0  4973.9     .07       0
  5013.3     .16       0  5421.6      .1       0
#XS Ineff= 2 ,-1
  3977.7 4968.43     861  5014.3 5415.34  861.16
Permanent Ineff=
       T       T
Bank Sta=4983.2,5007.56
XS Rating Curve= 0 ,0
Exp/Cntr=0.3,0.1

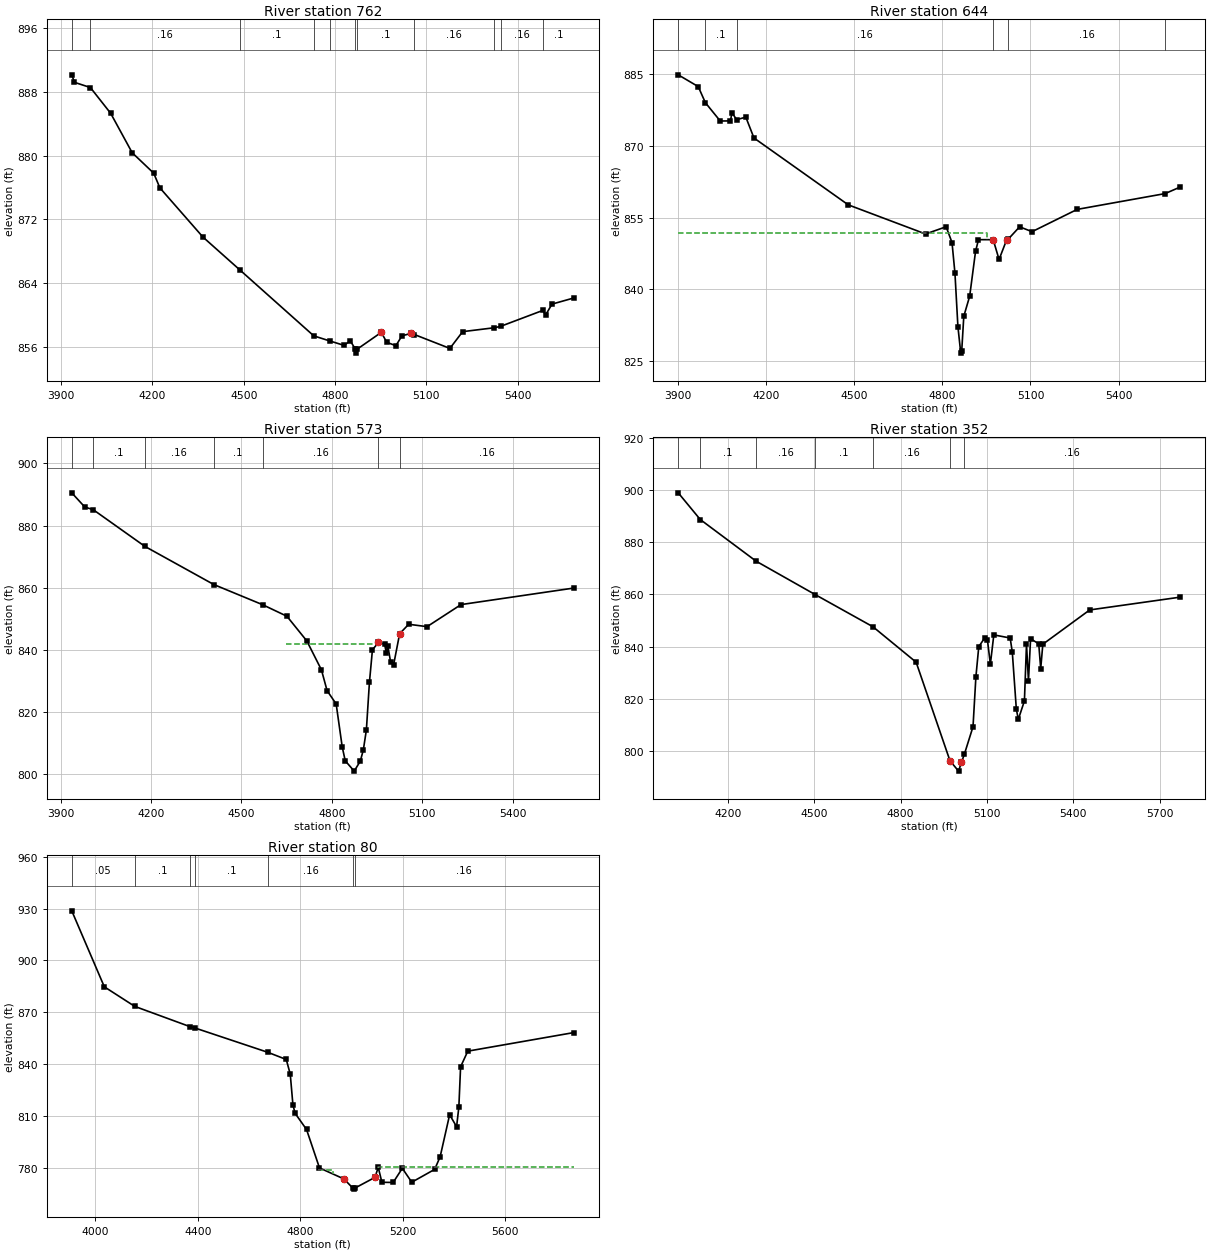
Type RM Length L Ch R = 1 ,762     ,118,118,118
BEGIN DESCRIPTION:
Mapping XS d301364c
END DESCRIPTION:
XS GIS Cut Line= 4
      2975582.04     10085707.89      2976366.79     10085822.48
      2976776.51     10085815.53      2977139.38      10085555.1
#Sta/Elev= 30
  3935.1  890.12  3943.8  889.18  3996.2  888.53  4062.9   885.3  4133.6  880.36
  4204.3   877.8  4224.6  875.96    4366   869.8  4486.8   865.7  4730.3  857.42
  4782.4  856.79  4829.9  856.23  4849.9  856.81  4866.9  855.76  4869.6  855.26
  4872.9  855.76    4952  857.86  4969.9  856.62  4999.9  856.19  5019.9  857.43
  5049.9  857.73  5060.7  857.59  5177.3  855.85  5219.3  857.95  5323.4  858.44
  5343.7  858.61  5482.7  860.61  5491.9  860.04  5512.8   861.4  5584.6  862.17
#Mann= 11 ,-1 , 0
  3935.1      .1       0  3996.2     .16       0  4486.8      .1       0
  4730.3     .16       0  4782.4      .1       0  4866.9     .07       0
  4872.9      .1       0  5060.7     .16       0  5323.4      .1       0
  5343.7     .16       0  5482.7      .1       0
Bank Sta=4952,5049.9
XS Rating Curve= 0 ,0
Exp/Cntr=0.3,0.1

Type RM Length L Ch R = 1 ,644     ,292,292,292
BEGIN DESCRIPTION:
Mapping XS 7b307f1d
END DESCRIPTION:
XS GIS Cut Line= 4
      2975566.21     10085801.52      2976127.34     10085951.74
      2976745.91     10085925.23      2977121.44     10085580.63
#Sta/Elev= 30
  3900.6  884.85  3968.7  882.39  3992.9  879.04  4043.6   875.2  4078.4  875.22
  4083.6  876.94  4099.6  875.46  4130.7  876.02  4158.5  871.65  4479.5  857.68
  4742.9  851.59  4812.9   853.1  4832.9   849.8  4842.9  843.38    4853   832.2
  4862.7  826.69    4866  827.19    4873  834.39    4893  838.58    4913  847.94
    4923   850.4  4973.1   850.4  4993.1  846.26  5018.5   850.3  5023.5  850.46
  5063.1  853.09  5105.4  852.07  5259.2  856.73  5558.5  860.03  5610.3  861.41
#Mann= 6 ,-1 , 0
  3900.6     .16       0  3992.9      .1       0  4099.6     .16       0
  4973.1     .07       0  5023.5     .16       0  5558.5      .1       0
#XS Ineff= 2 , 0
         4952.33  851.79
Permanent Ineff=
       T       T
Bank Sta=4973.1,5018.5
XS Rating Curve= 0 ,0
Exp/Cntr=0.3,0.1

Type RM Length L Ch R = 1 ,573     ,221,221,221
BEGIN DESCRIPTION:
Mapping XS b82c6658
END DESCRIPTION:
XS GIS Cut Line= 4
      2975582.09     10085881.51      2976399.78     10086016.92
      2976708.81     10085990.88      2977094.74     10085630.91
#Sta/Elev= 30
  3936.7  890.53  3979.8  885.97    4008   885.1  4179.6  873.29  4408.2  861.03
  4570.3  854.54  4650.9  850.83    4717  842.89  4765.5  833.58  4784.3  826.88
  4814.4  822.62  4834.5  808.79  4844.5  804.33  4874.3  801.01  4894.7  804.26
  4904.7  807.91  4914.7  814.26  4924.8  829.56  4934.8  840.05  4954.9  842.39
    4975   841.9    4981  839.01  4986.1  841.14    4995  836.21  5005.1  835.22
  5025.1  845.21  5055.2  848.25  5116.1  847.48  5228.9  854.58  5603.4   859.9
#Mann= 7 ,-1 , 0
  3936.7     .05       0    4008      .1       0  4179.6     .16       0
  4408.2      .1       0  4570.3     .16       0  4954.9     .07       0
  5025.1     .16       0
#XS Ineff= 1 ,-1
 4648.84 4949.71  841.85
Permanent Ineff=
       T
Bank Sta=4954.9,5025.1
XS Rating Curve= 0 ,0
Exp/Cntr=0.3,0.1

Type RM Length L Ch R = 1 ,352     ,272,272,272
BEGIN DESCRIPTION:
Mapping XS cb71e1db
END DESCRIPTION:
XS GIS Cut Line= 4
      2975573.79     10085970.14      2976421.04     10086147.23
      2976636.32     10086142.03      2977086.43     10085657.29
#Sta/Elev= 30
  4028.5  898.84  4104.9  888.63  4298.7  872.69  4504.6  859.85  4704.4  847.58
  4854.1  834.03  4971.5  796.33  5001.3  792.35  5011.5  795.76  5021.5  798.82
  5051.5  809.35  5061.5  828.43  5071.5  839.99  5091.5  843.22  5101.6  842.48
  5111.7  833.27  5123.7  844.48  5180.4  843.29  5187.8  837.92  5201.9  815.98
  5208.8  812.18  5229.9  819.22  5237.1  840.92  5243.9  826.89  5251.3  843.02
  5279.6  841.05  5286.4  831.54  5293.8  840.91  5456.5  854.03  5770.9  858.93
#Mann= 7 ,-1 , 0
  4028.5     .05       0  4104.9      .1       0  4298.7     .16       0
  4504.6      .1       0  4704.4     .16       0  4971.5     .07       0
  5021.5     .16       0
Bank Sta=4971.5,5011.5
XS Rating Curve= 0 ,0
Exp/Cntr=0.3,0.1

Type RM Length L Ch R = 1 ,80      ,0,0,0
BEGIN DESCRIPTION:
UNT 1063 IN LATR 1.0
END DESCRIPTION:
XS GIS Cut Line= 4
      2975585.95     10086126.39      2976594.66     10086404.18
      2976704.03     10086346.89      2977110.06     10085668.43
#Sta/Elev= 30
  3907.5  928.77  4034.6  884.73  4153.5  873.38  4370.3  861.58  4387.4  860.92
  4673.8  846.73    4745  842.61  4760.6   834.1    4771  816.33  4779.4  811.44
  4824.2  802.03  4874.7  779.76  4970.2  773.37  5005.7  767.97  5008.5  767.47
  5011.7  767.97  5091.2  774.26  5104.2  780.08  5118.4  771.43  5162.5  771.34
  5198.1  779.54  5235.1  771.48  5324.5  778.92  5345.9  786.27  5382.9  810.59
  5410.1  803.64  5418.9  815.08  5425.7  838.36  5453.8  847.44  5867.9  858.21
#Mann= 7 ,-1 , 0
  3907.5     .05       0  4153.5      .1       0  4370.3     .16       0
  4387.4      .1       0  4673.8     .16       0  5005.7     .07       0
  5011.7     .16       0
#XS Ineff= 2 ,-1
 4868.41 4926.58  778.27 5104.48  5867.9  780.11
Permanent Ineff=
       T       T
Bank Sta=4970.2,5091.2
XS Rating Curve= 0 ,0
Exp/Cntr=0.3,0.1

Chan Stop Cuts=-1
Use User Specified Reach Order=0
Composite Channel Slope=5