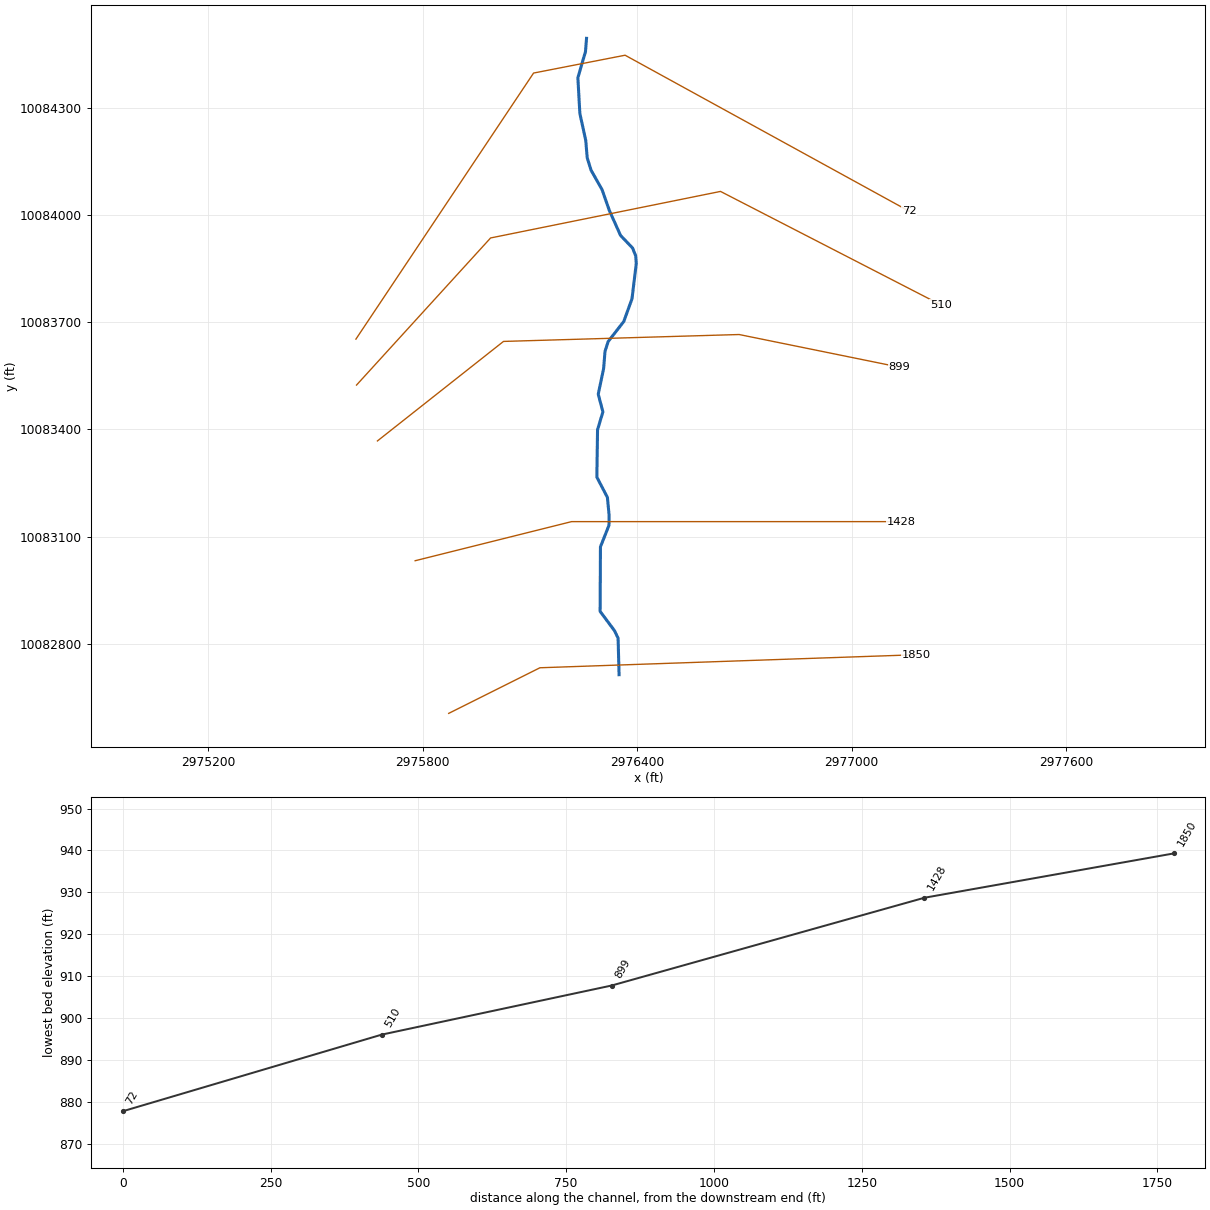
--- UNT 1064 IN LATR.prj (project) ---

Proj Title=UNT 1064 IN LATR Base Level Engineering
Current Plan=p01
Default Exp/Contr=0.3,0.1
English Units
Geom File=g01
Flow File=f01
Plan File=p01
Y Axis Title=Elevation
X Axis Title(PF)=Main Channel Distance
X Axis Title(XS)=Station
BEGIN DESCRIPTION:
UNT 1064 IN LATR
END DESCRIPTION:
DSS Export Rating Curves= 0
DSS Export Rating Curve Sorted= 0
DSS Export Volume Flow Curves= 0
DXF OffsetX= 0
DXF OffsetY= 0
DXF ScaleX= 1
DXF ScaleY= 10

--- UNT 1064 IN LATR.p01 (plan) ---

Plan Title=Multiple Run
Short Identifier=Multiple
Geom File=g01
Flow File=f01
Subcritical Flow
K Sum by GR= 0
Std Step Tol= 0.01
Critical Tol= 0.01
Num of Std Step Trials= 20
Max Error Tol= 0.3
Flow Tol Ratio= 0.001
Split Flow NTrial= 30
Split Flow Tol= 0.02
Split Flow Ratio= 0.02
Log Output Level= 0
Friction Slope Method= 1
Unsteady Friction Slope Method= 2
Unsteady Bridges Friction Slope Method= 1
Parabolic Critical Depth
Global Vel Dist=  1 , 1 , 1
Global Log Level= 0
CheckData=True
Encroach Param= -1, 0, 0, 0
BEGIN DESCRIPTION:
Multiple Run
END DESCRIPTION:

--- UNT 1064 IN LATR.f01 (steady flow) ---

Flow Title=Multiple
Program Version=4.10
Number of Profiles= 7
Profile Names=10-year,25-year,50-year,1pct_min,100-year,1pct_plu,500-year
River Rch & RM=UNT 1064 IN LATR,Reach-1         ,1850
     253     342     414     370     500     676     729
Boundary for River Rch & Prof#=UNT 1064 IN LATR,Reach-1         , 1
Up Type= 0
Dn Type= 3
Dn Slope=0.042
Boundary for River Rch & Prof#=UNT 1064 IN LATR,Reach-1         , 2
Up Type= 0
Dn Type= 3
Dn Slope=0.042
Boundary for River Rch & Prof#=UNT 1064 IN LATR,Reach-1         , 3
Up Type= 0
Dn Type= 3
Dn Slope=0.042
Boundary for River Rch & Prof#=UNT 1064 IN LATR,Reach-1         , 4
Up Type= 0
Dn Type= 3
Dn Slope=0.042
Boundary for River Rch & Prof#=UNT 1064 IN LATR,Reach-1         , 5
Up Type= 0
Dn Type= 3
Dn Slope=0.042
Boundary for River Rch & Prof#=UNT 1064 IN LATR,Reach-1         , 6
Up Type= 0
Dn Type= 3
Dn Slope=0.042
Boundary for River Rch & Prof#=UNT 1064 IN LATR,Reach-1         , 7
Up Type= 0
Dn Type= 3
Dn Slope=0.042
DSS Import GetInterval= 0
DSS Import GetPeak= 0
DSS Import FillOption= 0

--- UNT 1064 IN LATR.g01 (geometry) ---

Geom Title=Existing Conditions
Program Version=4.10

River Reach=UNT 1064 IN LATR,Reach-1
Reach XY= 30
      2976349.56     10082713.42      2976346.74     10082815.78
      2976336.76     10082836.49      2976296.51     10082890.51
       2976297.4     10083071.08      2976321.31     10083131.44
      2976321.66     10083159.23      2976316.88     10083209.52
      2976287.36      10083266.1      2976289.28     10083398.62
      2976304.27     10083448.75      2976291.22     10083498.16
      2976306.24      10083569.6       2976310.2     10083618.01
        2976319.     10083645.51      2976362.63     10083701.45
      2976385.67      10083765.1      2976397.68     10083864.35
      2976396.04     10083885.16      2976387.43     10083906.93
      2976353.66     10083942.28      2976322.24     10084012.38
      2976301.91     10084070.45      2976271.16     10084124.85
      2976260.34     10084159.51      2976256.33     10084207.85
      2976239.77     10084283.78      2976234.27     10084383.64
      2976255.54     10084456.44      2976258.47     10084493.73

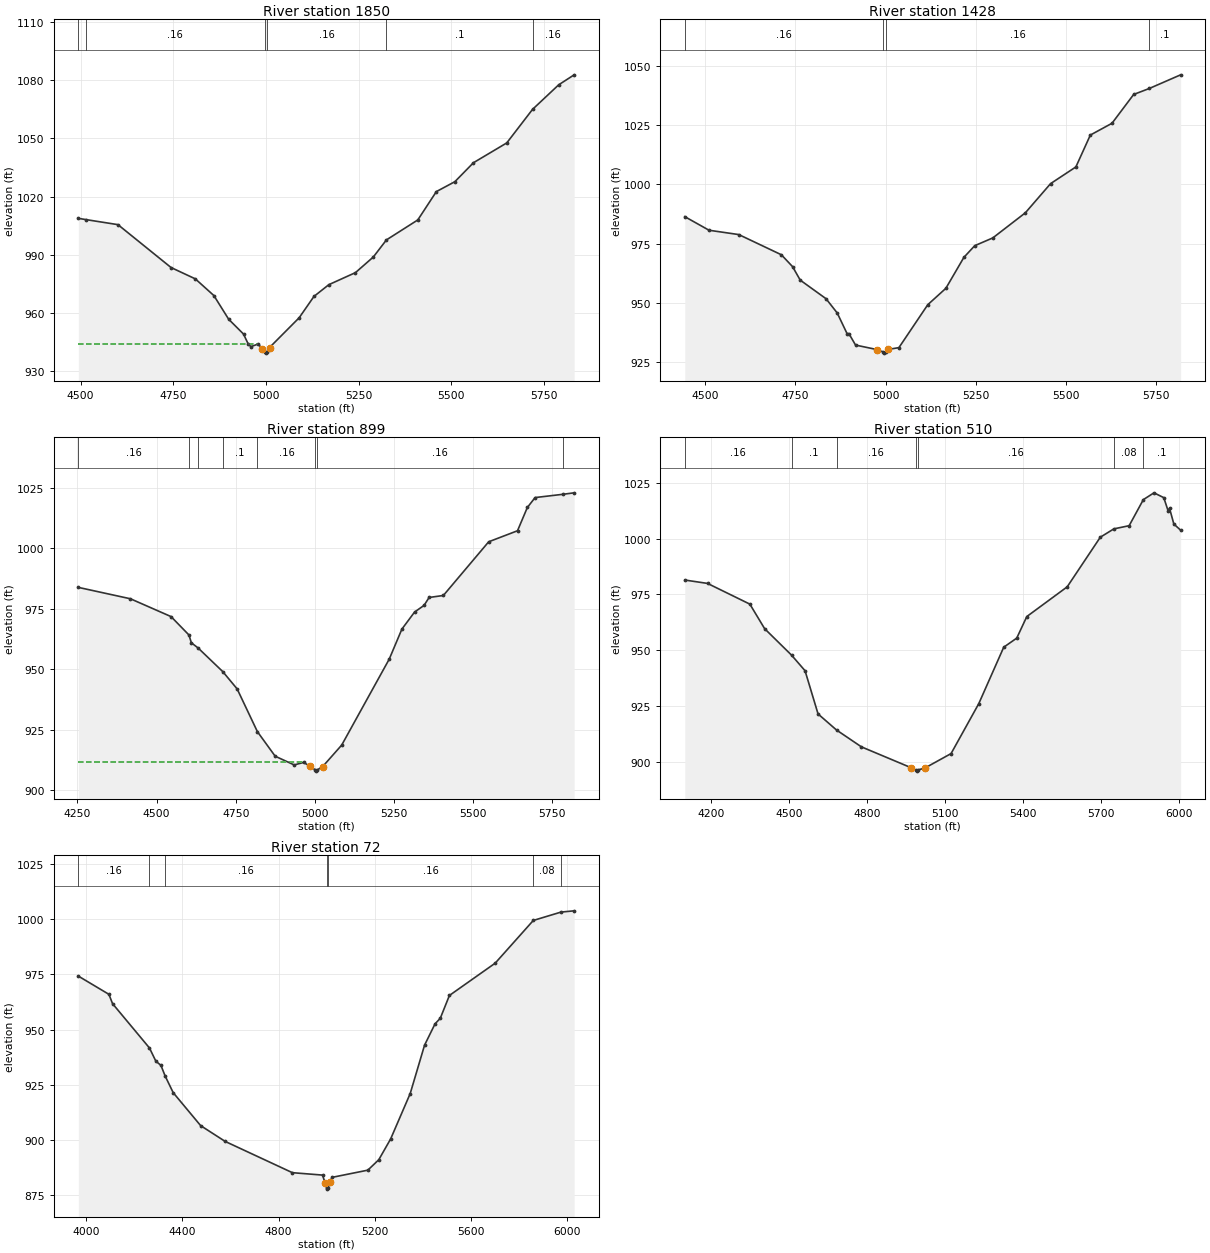
Type RM Length L Ch R = 1 ,1850    ,422,422,422
BEGIN DESCRIPTION:
UNT 1064 IN LATR 4.0
END DESCRIPTION:
XS GIS Cut Line= 3
      2975872.87     10082605.22      2976128.06     10082732.82
      2977180.12     10082769.27
#Sta/Elev= 30
  4493.8 1008.76  4513.2 1008.14  4600.7 1005.51    4744  983.41  4809.5  977.57
  4859.6  968.96  4899.6  956.73  4939.6  949.12  4952.3  943.98  4959.6  942.63
  4979.6  944.05  4989.6   941.4  4996.6   939.8  4999.4   939.3  5002.6   939.8
  5009.7  942.17  5089.7  957.52  5129.7  968.53  5169.8  974.58  5241.7  980.79
  5289.8  988.83  5325.2  997.64  5409.9 1007.94  5459.9 1022.53    5510 1027.66
    5560 1037.41    5650 1047.63  5719.5 1064.91  5790.1 1077.57  5831.8 1082.71
#Mann= 6 ,-1 , 0
  4493.8      .1       0  4513.2     .16       0  4996.6     .07       0
  5002.6     .16       0  5325.2      .1       0  5719.5     .16       0
#XS Ineff= 2 , 0
         4979.55  944.09
Permanent Ineff=
       T       T
Bank Sta=4989.6,5009.7
XS Rating Curve= 0 ,0
Exp/Cntr=0.3,0.1

Type RM Length L Ch R = 1 ,1428    ,529,529,529
BEGIN DESCRIPTION:
UNT 1064 IN LATR 3.0
END DESCRIPTION:
XS GIS Cut Line= 3
      2975779.11      10083032.3       2976216.6     10083141.67
      2977138.44     10083141.67
#Sta/Elev= 30
  4444.2  986.36  4511.3  980.62  4593.7  978.79  4711.5  970.27  4742.5  965.26
  4763.8  959.55  4835.2  951.71  4866.2  945.68  4893.5  936.95  4898.6  936.95
    4917  932.12    4977   930.2    4994  929.22  4996.8  928.72    5000  929.22
    5007  930.27    5037  931.04    5117  949.18    5167  956.09    5217  969.18
    5247   974.1    5297  977.38    5387  987.97    5457 1000.31    5527 1007.36
    5567 1020.82    5627  1025.8    5687 1037.97  5730.5 1040.51    5817 1046.26
#Mann= 4 ,-1 , 0
  4444.2     .16       0    4994     .07       0    5000     .16       0
  5730.5      .1       0
Bank Sta=4977,5007
XS Rating Curve= 0 ,0
Exp/Cntr=0.3,0.1

Type RM Length L Ch R = 1 ,899     ,389,389,389
BEGIN DESCRIPTION:
UNT 1064 IN LATR 2.0
END DESCRIPTION:
XS GIS Cut Line= 4
       2975673.5      10083367.4      2976026.13      10083645.8
      2976685.35     10083665.11      2977133.29     10083573.96
#Sta/Elev= 30
    4253  983.79  4417.6  979.08  4545.8  971.71  4602.4  964.09  4609.9  960.88
  4631.4  958.71  4709.3  948.93  4754.6  941.78  4818.5  924.11  4874.7  913.95
  4934.7  910.35  4964.7  911.38  4984.7  909.78  5001.7  908.28  5004.5  907.78
  5007.7  908.28  5024.8  909.68  5084.8  918.56  5234.8   954.1  5274.9  966.54
  5314.9  973.59  5344.9  976.35  5360.8  979.62  5405.8  980.44    5549 1002.66
    5640 1007.22  5671.1 1016.86  5695.6 1020.95  5782.6 1022.29  5818.9 1022.91
#Mann= 8 ,-1 , 0
    4253     .16       0  4602.4      .1       0  4631.4     .16       0
  4709.3      .1       0  4818.5     .16       0  5001.7     .07       0
  5007.7     .16       0  5782.6      .1       0
#XS Ineff= 2 , 0
         4964.88  911.46
Permanent Ineff=
       T       T
Bank Sta=4984.7,5024.8
XS Rating Curve= 0 ,0
Exp/Cntr=0.3,0.1

Type RM Length L Ch R = 1 ,510     ,438,438,438
BEGIN DESCRIPTION:
Mapping XS a3a2b4a6
END DESCRIPTION:
XS GIS Cut Line= 4
      2975615.05     10083523.76      2975990.08     10083935.25
      2976633.31     10084065.46      2977249.53     10083748.25
#Sta/Elev= 30
  4100.2  981.46  4187.5  979.95  4350.3  970.69  4407.1  959.72  4510.4  947.91
  4562.5  940.92  4612.5  921.61  4683.4  914.44  4779.1  906.91  4971.6  897.52
    4989  896.56  4991.8  896.06    4995  896.56  5022.4  897.39  5123.8   903.9
  5230.3  926.21  5326.3  951.44  5376.3   955.5    5415  965.14  5570.2  978.41
  5697.6  1000.6  5749.6 1004.32  5808.4 1005.74    5863 1017.39  5903.9 1020.43
  5941.5 1018.27    5958 1012.46  5963.6 1013.54  5980.2  1006.5  6006.3 1003.73
#Mann= 7 ,-1 , 0
  4100.2     .16       0  4510.4      .1       0  4683.4     .16       0
    4989     .07       0    4995     .16       0  5749.6     .08       0
    5863      .1       0
Bank Sta=4971.6,5022.4
XS Rating Curve= 0 ,0
Exp/Cntr=0.3,0.1

Type RM Length L Ch R = 1 ,72      ,0,0,0
BEGIN DESCRIPTION:
UNT 1064 IN LATR 1.0
END DESCRIPTION:
XS GIS Cut Line= 4
      2975613.34     10083652.26      2976110.28     10084396.58
      2976366.36      10084446.5      2977160.61     10084010.31
#Sta/Elev= 30
    3967  974.27  4094.2  966.01  4109.2   961.8  4262.8  941.71  4289.4  935.73
  4310.4  933.85  4328.1     929  4361.5  921.48  4475.6  906.55  4577.8  899.38
  4857.2  885.23  4982.6  884.14  4992.6  880.77  4999.7  878.28  5002.5  877.78
  5005.7  878.28  5012.9  881.08  5023.1  883.13  5170.9  886.37  5216.5   891.1
  5265.8  900.51  5347.2  921.08  5406.9     943  5450.5  952.65  5472.3  955.17
  5510.2   965.5  5700.6  980.12  5859.1  999.47  5974.3 1003.26    6029 1003.83
#Mann= 7 ,-1 , 0
    3967     .16       0  4262.8      .1       0  4328.1     .16       0
  4999.7     .07       0  5005.7     .16       0  5859.1     .08       0
  5974.3      .1       0
Bank Sta=4992.6,5012.9
XS Rating Curve= 0 ,0
Exp/Cntr=0.3,0.1

Chan Stop Cuts=-1
Use User Specified Reach Order=0
Composite Channel Slope=5