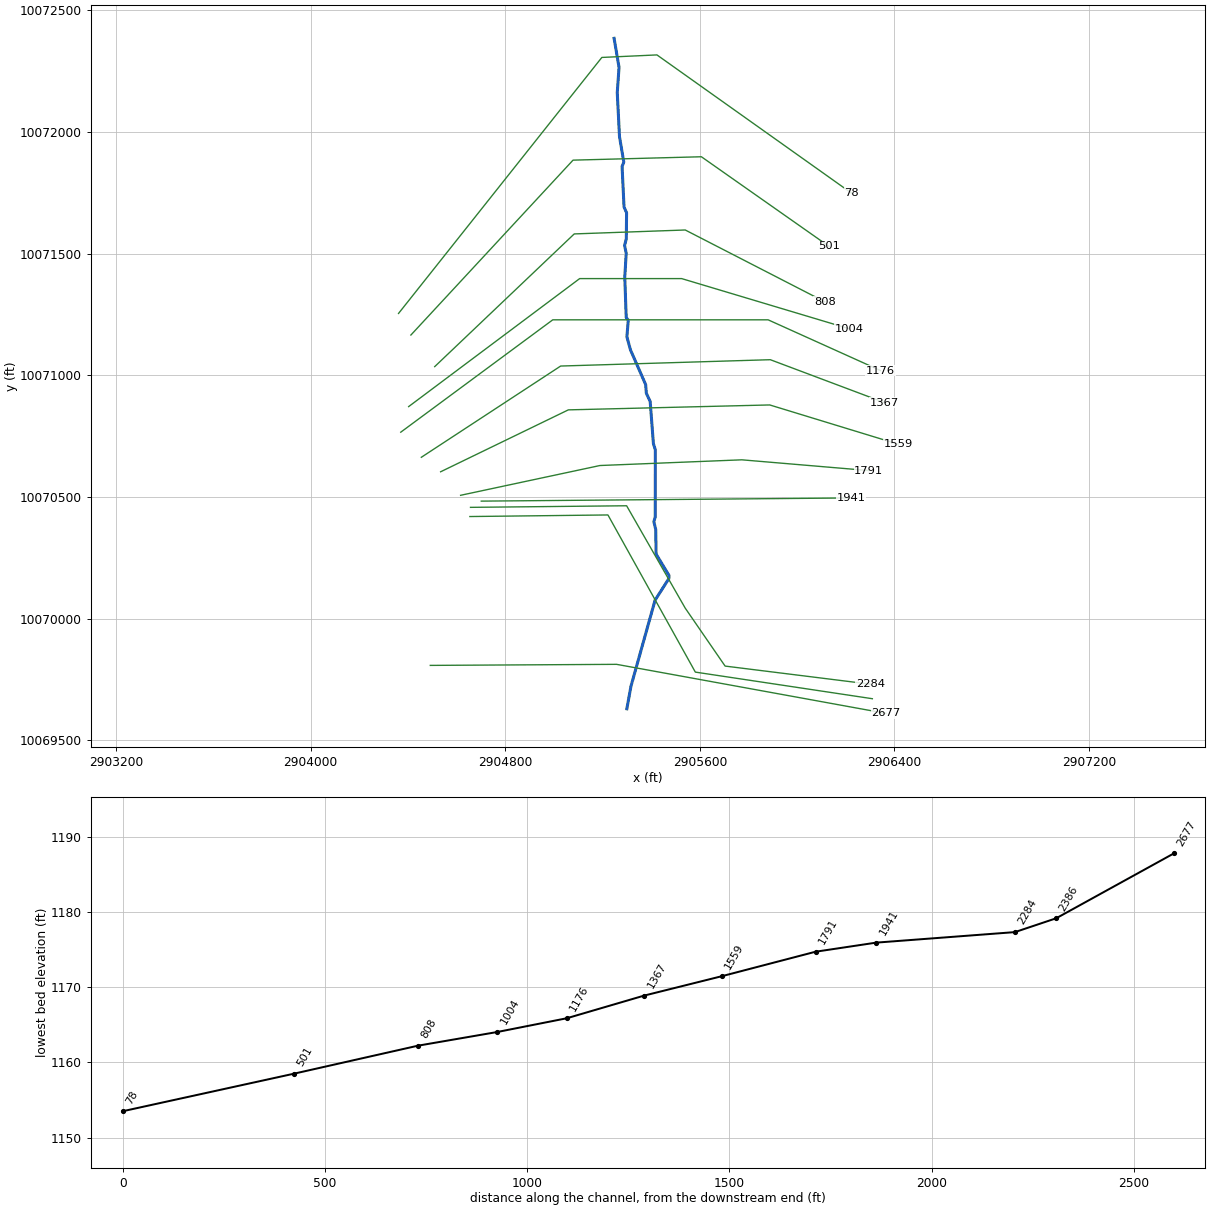
--- UNT 1066 IN LATR.prj (project) ---

Proj Title=UNT 1066 IN LATR Base Level Engineering
Current Plan=p01
Default Exp/Contr=0.3,0.1
English Units
Geom File=g01
Flow File=f01
Plan File=p01
Y Axis Title=Elevation
X Axis Title(PF)=Main Channel Distance
X Axis Title(XS)=Station
BEGIN DESCRIPTION:
UNT 1066 IN LATR
END DESCRIPTION:
DSS Export Rating Curves= 0
DSS Export Rating Curve Sorted= 0
DSS Export Volume Flow Curves= 0
DXF OffsetX= 0
DXF OffsetY= 0
DXF ScaleX= 1
DXF ScaleY= 10

--- UNT 1066 IN LATR.p01 (plan) ---

Plan Title=Multiple Run
Short Identifier=Multiple
Geom File=g01
Flow File=f01
Subcritical Flow
K Sum by GR= 0
Std Step Tol= 0.01
Critical Tol= 0.01
Num of Std Step Trials= 20
Max Error Tol= 0.3
Flow Tol Ratio= 0.001
Split Flow NTrial= 30
Split Flow Tol= 0.02
Split Flow Ratio= 0.02
Log Output Level= 0
Friction Slope Method= 1
Unsteady Friction Slope Method= 2
Unsteady Bridges Friction Slope Method= 1
Parabolic Critical Depth
Global Vel Dist=  1 , 1 , 1
Global Log Level= 0
CheckData=True
Encroach Param= -1, 0, 0, 0
BEGIN DESCRIPTION:
Multiple Run
END DESCRIPTION:

--- UNT 1066 IN LATR.f01 (steady flow) ---

Flow Title=Multiple
Program Version=4.10
Number of Profiles= 7
Profile Names=10-year,25-year,50-year,1pct_min,100-year,1pct_plu,500-year
River Rch & RM=UNT 1066 IN LATR,Reach-1         ,2677
     235     311     372     327     442     598     624
Boundary for River Rch & Prof#=UNT 1066 IN LATR,Reach-1         , 1
Up Type= 0
Dn Type= 3
Dn Slope=0.0117
Boundary for River Rch & Prof#=UNT 1066 IN LATR,Reach-1         , 2
Up Type= 0
Dn Type= 3
Dn Slope=0.0117
Boundary for River Rch & Prof#=UNT 1066 IN LATR,Reach-1         , 3
Up Type= 0
Dn Type= 3
Dn Slope=0.0117
Boundary for River Rch & Prof#=UNT 1066 IN LATR,Reach-1         , 4
Up Type= 0
Dn Type= 3
Dn Slope=0.0117
Boundary for River Rch & Prof#=UNT 1066 IN LATR,Reach-1         , 5
Up Type= 0
Dn Type= 3
Dn Slope=0.0117
Boundary for River Rch & Prof#=UNT 1066 IN LATR,Reach-1         , 6
Up Type= 0
Dn Type= 3
Dn Slope=0.0117
Boundary for River Rch & Prof#=UNT 1066 IN LATR,Reach-1         , 7
Up Type= 0
Dn Type= 3
Dn Slope=0.0117
DSS Import GetInterval= 0
DSS Import GetPeak= 0
DSS Import FillOption= 0

--- UNT 1066 IN LATR.g01 (geometry) ---

Geom Title=Existing Conditions
Program Version=4.10

River Reach=UNT 1066 IN LATR,Reach-1
Reach XY= 30
       2905299.9     10069630.05      2905316.87     10069722.83
      2905415.96     10070076.36      2905472.75     10070165.26
      2905473.45     10070177.89      2905420.19     10070266.16
       2905418.7     10070366.93      2905411.02     10070398.87
      2905416.76     10070419.25      2905417.03     10070694.78
      2905409.17     10070719.69      2905395.85     10070893.23
      2905380.04     10070926.98      2905377.29     10070962.54
      2905314.85     10071105.15      2905300.15     10071158.47
      2905305.81     10071227.56      2905297.38     10071237.47
      2905291.41     10071403.95      2905297.34     10071502.44
       2905290.6     10071534.15      2905297.71     10071561.86
      2905298.85     10071668.63       2905288.4      10071692.2
      2905280.33      10071858.9      2905287.44     10071876.83
      2905269.76     10071981.05      2905260.51     10072162.19
      2905267.83     10072266.19      2905247.44     10072385.49

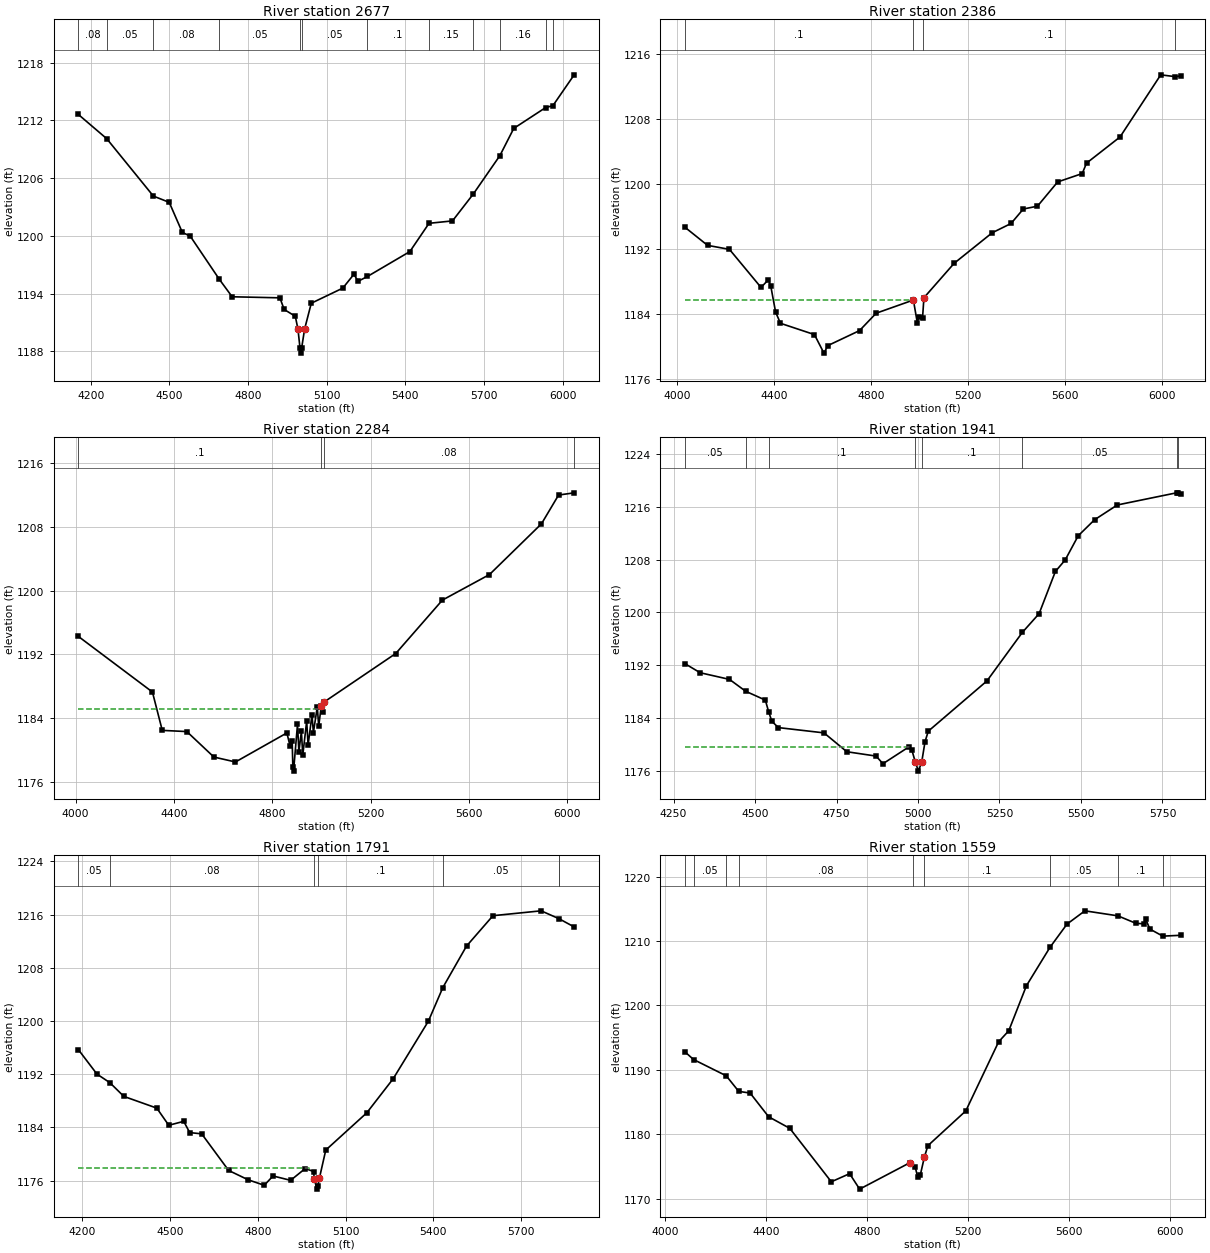
Type RM Length L Ch R = 1 ,2677    ,291,291,291
BEGIN DESCRIPTION:
UNT 1066 IN LATR 6.0
END DESCRIPTION:
XS GIS Cut Line= 3
      2904491.72     10069808.44      2905257.78     10069812.78
      2906365.12     10069611.25
#Sta/Elev= 30
  4152.4 1212.62  4260.7  1210.1  4438.7 1204.13  4499.2 1203.48  4549.2 1200.35
  4579.2 1199.97  4690.7 1195.46  4739.2 1193.66  4921.4 1193.55  4937.7 1192.34
  4980.2 1191.63  4990.3 1190.29  4998.2  1188.3    5001  1187.8  5004.2  1188.3
 5015.62  1190.3  5041.1 1192.99  5161.3 1194.56  5203.8    1196  5219.7 1195.27
  5255.3 1195.77  5417.2 1198.36  5490.3  1201.3  5579.8 1201.55  5659.6 1204.36
  5760.7 1208.34  5813.6 1211.17  5935.5 1213.34  5962.8 1213.53    6044 1216.74
#Mann= 12 ,-1 , 0
  4152.4     .08       0  4260.7     .05       0  4438.7     .08       0
  4690.7     .05       0  4998.2     .07       0  5004.2     .05       0
  5255.3      .1       0  5490.3     .15       0  5659.6      .1       0
  5760.7     .16       0  5935.5      .1       0  5962.8     .05       0
Bank Sta=4990.3,5015.62
XS Rating Curve= 0 ,0
Exp/Cntr=0.3,0.1

Type RM Length L Ch R = 1 ,2386    ,102,102,102
BEGIN DESCRIPTION:
Mapping XS 7fe529b1
END DESCRIPTION:
XS GIS Cut Line= 4
      2904654.53      10070420.2      2905222.19     10070426.71
      2905581.57     10069780.87      2906309.41      10069671.5
#Sta/Elev= 30
  4032.5 1194.66  4126.4 1192.42  4216.4 1191.93  4346.5 1187.25  4376.5 1188.18
  4386.5 1187.45  4406.5 1184.23  4426.5 1182.84  4566.5 1181.45  4605.8 1179.17
  4622.1  1180.1  4752.4 1181.94    4821 1184.08  4974.3  1185.7  4990.3 1182.92
    4996 1183.56    5012 1183.49  5017.7 1185.98  5142.4 1190.22    5299 1193.97
  5376.6 1195.11  5427.2 1196.89  5485.5 1197.24  5568.7 1200.22  5669.9 1201.25
  5687.6 1202.53  5825.7 1205.75  5993.4 1213.39  6054.1 1213.16  6075.3 1213.27
#Mann= 4 ,-1 , 0
  4032.5      .1       0  4974.3     .07       0    5012      .1       0
  6054.1     .16       0
#XS Ineff= 2 , 0
         4960.23 1185.66
Permanent Ineff=
       T       T
Bank Sta=4974.3,5017.7
XS Rating Curve= 0 ,0
Exp/Cntr=0.3,0.1

Type RM Length L Ch R = 1 ,2284    ,343,343,343
BEGIN DESCRIPTION:
UNT 1066 IN LATR 5.0
END DESCRIPTION:
XS GIS Cut Line= 5
       2904657.1     10070457.96      2905299.01     10070464.47
       2905539.9     10070043.89      2905703.96     10069805.61
      2906300.34     10069731.39
#Sta/Elev= 30
    4011 1194.26  4312.4 1187.27  4352.4 1182.45  4452.4  1182.3  4562.4  1179.1
  4650.2 1178.48  4859.3 1182.13  4872.7 1180.45  4880.9 1181.06  4883.6 1177.83
  4886.4 1177.33  4902.5 1183.19  4908.2 1179.79  4918.3 1182.31    4924 1179.34
  4939.9 1183.63  4945.6 1180.59  4961.4  1184.4  4967.2 1182.18    4983  1185.4
  4988.8 1182.97  4998.9 1185.46  5004.6 1184.75    5011 1186.02  5302.2 1192.11
  5491.9 1198.82  5683.4 1202.03    5895 1208.41  5964.5 1212.02  6027.9  1212.3
#Mann= 4 ,-1 , 0
    4011      .1       0  4998.9     .07       0    5011     .08       0
  6027.9     .16       0
#XS Ineff= 2 , 0
         4997.16 1185.16
Permanent Ineff=
       T       T
Bank Sta=4998.9,5011
XS Rating Curve= 0 ,0
Exp/Cntr=0.3,0.1

Type RM Length L Ch R = 1 ,1941    ,150,150,150
BEGIN DESCRIPTION:
UNT 1066 IN LATR 4.0
END DESCRIPTION:
XS GIS Cut Line= 2
      2904701.38     10070483.56      2906222.63     10070496.58
#Sta/Elev= 30
  4284.5 1192.24  4331.6 1190.85  4421.6 1189.84  4471.3 1188.04  4531.6  1186.7
  4541.6 1184.96  4551.6 1183.49  4571.6 1182.53  4711.6 1181.73  4781.6 1178.87
  4871.6 1178.21  4892.4 1177.05  4971.6 1179.59  4981.6 1179.06  4991.6 1177.33
  5001.4 1175.93  5011.6 1177.36  5021.6  1180.4  5031.6 1181.99  5211.6 1189.61
  5320.4 1196.98  5371.6 1199.81  5421.6 1206.21  5451.6 1207.95  5491.6 1211.62
  5541.6 1214.04  5611.6 1216.29  5793.2 1218.13  5798.6 1218.04  5805.8 1217.99
#Mann= 8 ,-1 , 0
  4284.5     .05       0  4471.3     .08       0  4541.6      .1       0
  4991.6     .07       0  5011.6      .1       0  5320.4     .05       0
  5793.2      .1       0  5798.6     .05       0
#XS Ineff= 2 , 0
         4973.18 1179.64
Permanent Ineff=
       T       T
Bank Sta=4991.6,5011.6
XS Rating Curve= 0 ,0
Exp/Cntr=0.3,0.1

Type RM Length L Ch R = 1 ,1791    ,232,232,232
BEGIN DESCRIPTION:
Mapping XS d232eee4
END DESCRIPTION:
XS GIS Cut Line= 4
      2904616.38     10070507.46      2905189.33     10070629.87
      2905772.66      10070653.3      2906294.82     10070609.14
#Sta/Elev= 30
    4187  1195.7  4250.5 1192.02  4294.5 1190.73  4342.5 1188.66    4455  1186.9
  4495.9 1184.32    4547 1184.91  4567.5 1183.22  4608.4 1183.03  4700.4 1177.53
  4767.2 1176.12  4822.1  1175.3  4852.1  1176.7  4912.1 1176.04  4962.2 1177.82
  4990.4 1177.37 4993.18 1176.26  5001.9 1174.72  5005.2 1175.22 5010.23 1176.32
  5032.2 1180.59  5172.3 1186.19  5262.4 1191.31  5382.6 1199.96  5432.2 1205.03
    5513 1211.26  5603.4 1215.83  5767.9 1216.56  5828.7 1215.38  5880.7 1214.14
#Mann= 7 ,-1 , 0
    4187     .05       0  4294.5     .08       0 4993.18     .05       0
  5005.2      .1       0  5432.2     .05       0  5828.7      .1       0
  5828.7     .05       0
#XS Ineff= 2 , 0
         4973.86 1177.95
Permanent Ineff=
       T       T
Bank Sta=4993.18,5010.23
XS Rating Curve= 0 ,0
Exp/Cntr=0.3,0.1

Type RM Length L Ch R = 1 ,1559    ,192,192,192
BEGIN DESCRIPTION:
UNT 1066 IN LATR 3.0
END DESCRIPTION:
XS GIS Cut Line= 4
      2904534.25     10070604.14      2905059.36     10070858.61
      2905887.45     10070878.81      2906415.04     10070717.71
#Sta/Elev= 30
  4078.1  1192.8  4112.7 1191.59  4242.2 1189.06  4291.7 1186.64  4336.8 1186.38
  4410.1  1182.7  4493.9  1180.9  4658.3  1172.6  4730.7 1173.86  4770.5 1171.46
  4970.8 1175.59  4990.8 1174.84  5000.8 1173.28  5010.8 1173.68 5026.99 1176.45
  5040.8 1178.21  5190.9 1183.61  5320.9 1194.34  5360.9 1196.05    5431 1203.05
  5524.4 1209.02  5591.7 1212.62  5662.5 1214.68  5793.4  1213.9  5864.5 1212.74
  5897.4 1212.66  5902.6 1213.45  5919.7 1211.85    5971 1210.75  6041.6 1210.88
#Mann= 9 ,-1 , 0
  4078.1     .08       0  4112.7     .05       0  4242.2     .08       0
  4291.7     .08       0  4980.8     .05       0 5026.99      .1       0
  5524.4     .05       0  5793.4      .1       0    5971     .05       0
#XS Ineff= 2 , 0
         4958.81 1175.19
Permanent Ineff=
       T       T
Bank Sta=4970.8,5026.99
XS Rating Curve= 0 ,0
Exp/Cntr=0.3,0.1

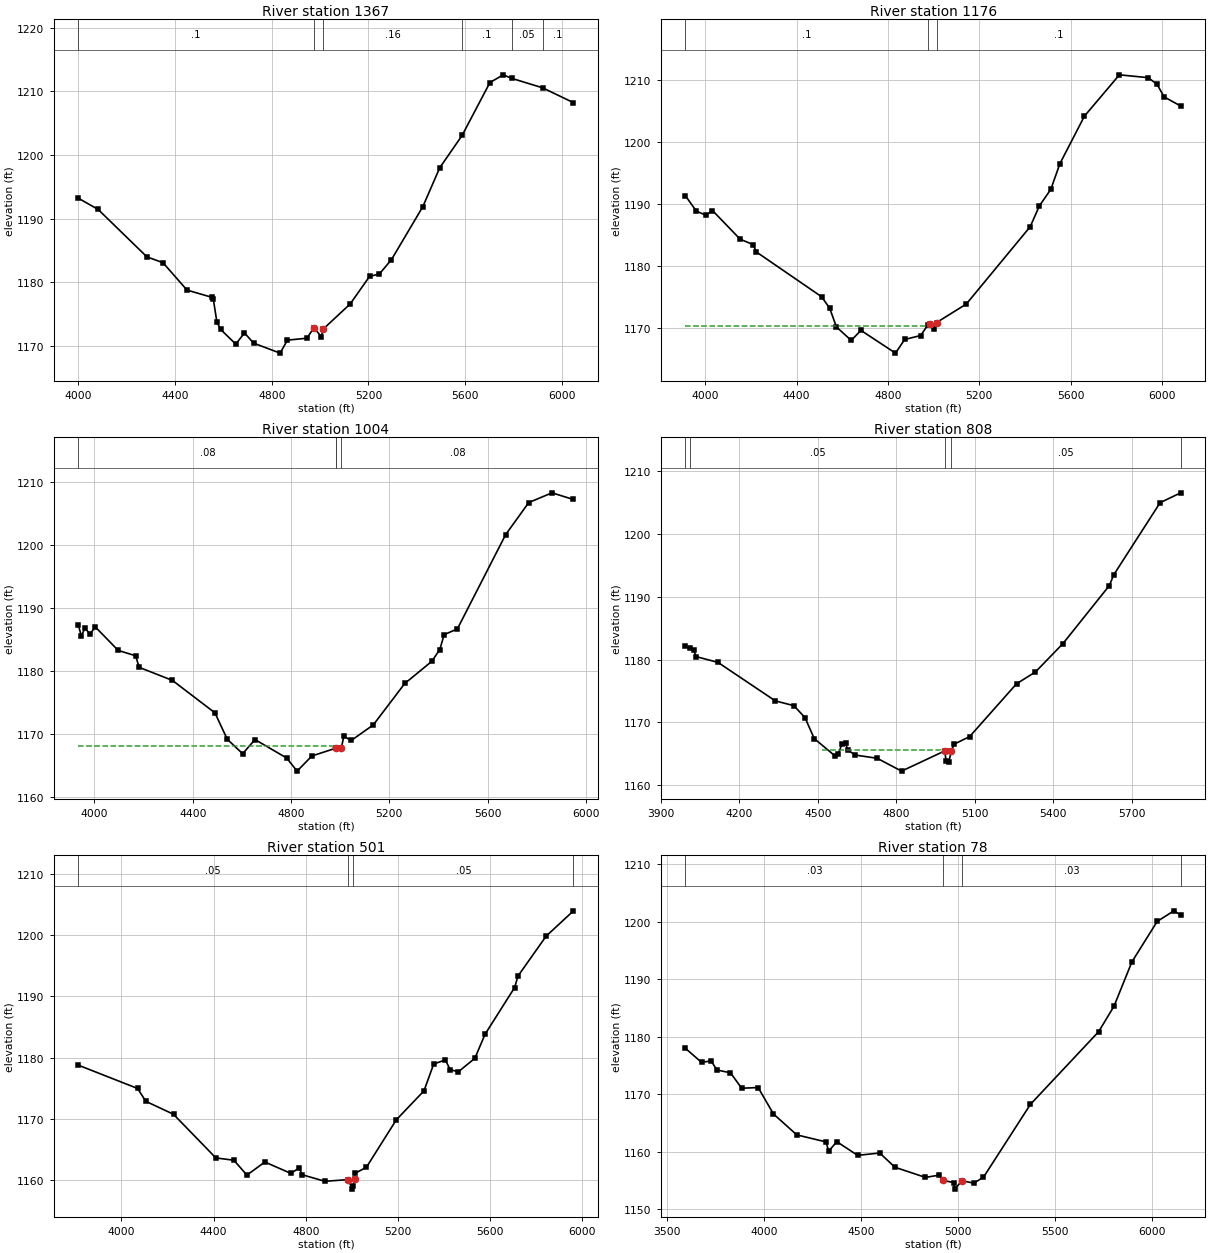
Type RM Length L Ch R = 1 ,1367    ,191,191,191
BEGIN DESCRIPTION:
Mapping XS eb616e14
END DESCRIPTION:
XS GIS Cut Line= 4
      2904454.93     10070663.71      2905027.87     10071038.72
      2905889.85     10071064.76      2906359.84     10070888.19
#Sta/Elev= 30
  3999.4 1193.21  4081.5 1191.44  4283.5 1183.99  4349.9 1183.08  4449.3 1178.78
  4551.9 1177.65  4557.9 1177.41    4573 1173.76  4588.1 1172.61  4651.3 1170.29
  4687.2 1172.06  4724.8 1170.45  4834.6 1168.88  4864.8 1170.92  4944.9 1171.22
  4974.9 1172.86  5004.9 1171.47  5012.8 1172.65    5125 1176.62    5205 1180.94
    5245 1181.29    5295 1183.54  5425.1 1191.87  5495.1 1197.98  5587.7 1203.06
  5702.9 1211.37    5758 1212.58  5793.6 1212.02  5920.9 1210.54  6048.6 1208.21
#Mann= 6 ,-1 , 0
  3999.4      .1       0  4974.9     .05       0  5012.8     .16       0
  5587.7      .1       0  5793.6     .05       0  5920.9      .1       0
#XS Ineff= 2 , 0
         4969.32 1172.47
Permanent Ineff=
       T       T
Bank Sta=4974.9,5012.8
XS Rating Curve= 0 ,0
Exp/Cntr=0.3,0.1

Type RM Length L Ch R = 1 ,1176    ,172,172,172
BEGIN DESCRIPTION:
Mapping XS c104dc73
END DESCRIPTION:
XS GIS Cut Line= 4
      2904370.38     10070766.86      2904995.37     10071228.66
      2905880.78     10071228.66      2906342.56     10071020.34
#Sta/Elev= 30
  3913.4 1191.23  3960.8 1188.79  4002.5 1188.11  4031.7 1188.87  4152.8 1184.25
  4209.4 1183.38  4223.8 1182.19  4509.8 1174.96  4545.3 1173.09  4574.5  1170.1
  4639.3 1167.92  4681.9 1169.54  4833.3 1165.87  4873.6 1168.07  4943.6 1168.71
  4973.6 1170.33  4983.6  1170.5  5003.6 1169.74  5013.6 1170.81  5143.6 1173.79
  5423.6 1186.27  5463.6 1189.62  5513.6 1192.28  5553.6 1196.44  5661.1  1204.1
  5814.1 1210.76  5940.7  1210.3  5979.3 1209.22  6010.1  1207.2  6082.5 1205.73
#Mann= 3 ,-1 , 0
  3913.4      .1       0  4973.6     .05       0  5013.6      .1       0
#XS Ineff= 2 , 0
         4971.02 1170.29
Permanent Ineff=
       T       T
Bank Sta=4983.6,5013.6
XS Rating Curve= 0 ,0
Exp/Cntr=0.3,0.1

Type RM Length L Ch R = 1 ,1004    ,196,196,196
BEGIN DESCRIPTION:
Mapping XS beba3533
END DESCRIPTION:
XS GIS Cut Line= 4
      2904402.83     10070872.03      2905105.99      10071398.1
      2905525.26      10071398.1       2906212.8     10071192.36
#Sta/Elev= 30
  3934.3 1187.31  3946.5 1185.53  3961.1 1186.73    3982 1185.87  4003.8 1186.95
  4096.6 1183.23  4167.4 1182.38    4182 1180.54  4317.5 1178.46  4490.5  1173.3
  4540.5  1169.1  4603.2 1166.81  4653.2 1169.06  4782.2 1166.13  4824.7 1164.04
  4884.9 1166.45  4984.9 1167.72  5004.9 1167.76  5014.9 1169.58  5044.9 1168.91
  5134.9 1171.39  5262.8 1177.97  5372.5 1181.48  5405.6 1183.37    5423 1185.73
    5477 1186.65  5673.5 1201.64  5767.4 1206.73    5862 1208.28  5949.4 1207.22
#Mann= 4 ,-1 , 0
  3934.3     .08       0  4984.9     .05       0  4984.9     .05       0
  5004.9     .08       0
#XS Ineff= 2 , 0
         4971.59 1168.01
Permanent Ineff=
       T       T
Bank Sta=4984.9,5004.9
XS Rating Curve= 0 ,0
Exp/Cntr=0.3,0.1

Type RM Length L Ch R = 1 ,808     ,307,307,307
BEGIN DESCRIPTION:
UNT 1066 IN LATR 2.0
END DESCRIPTION:
XS GIS Cut Line= 4
      2904509.99     10071036.35      2905083.59     10071581.68
      2905540.06     10071597.84       2906113.6     10071302.99
#Sta/Elev= 30
    3994 1182.08  4012.3 1181.77  4026.4 1181.49  4033.3 1180.48  4118.3 1179.54
  4337.5 1173.41  4408.3 1172.65  4450.8 1170.75  4486.3  1167.4    4564  1164.7
  4578.2 1164.93  4592.3 1166.59  4606.5 1166.66  4613.4 1165.65  4641.7 1164.79
  4726.6 1164.27  4820.1 1162.22  4985.1 1165.44  4990.5 1163.79  5000.5  1163.7
  5010.5  1165.4  5020.5  1166.5  5080.5 1167.73  5259.7 1176.14  5331.9 1178.02
  5437.1 1182.54  5614.6 1191.79  5631.1 1193.49  5808.6 1204.99  5887.1 1206.56
#Mann= 5 ,-1 , 0
    3994     .08       0  4012.3     .05       0  4985.1    .035       0
  5010.5     .05       0  5887.1      .1       0
#XS Ineff= 1 ,-1
 4514.62 4970.16 1165.58
Permanent Ineff=
       T
Bank Sta=4985.1,5010.5
XS Rating Curve= 0 ,0
Exp/Cntr=0.3,0.1

Type RM Length L Ch R = 1 ,501     ,423,423,423
BEGIN DESCRIPTION:
Mapping XS 7370df5f
END DESCRIPTION:
XS GIS Cut Line= 4
      2904412.06     10071166.18       2905078.7     10071884.91
      2905606.48      10071898.8      2906130.74     10071530.77
#Sta/Elev= 30
  3812.7 1178.75    4070 1174.94  4105.7 1172.84  4225.9 1170.72  4409.6 1163.59
  4487.9 1163.21  4544.5 1160.78  4622.2 1162.92  4735.6 1161.06  4770.8 1161.96
  4784.9 1160.83  4882.8 1159.77  4982.8 1160.04  5002.6 1158.49  5005.8 1158.99
 5011.36 1160.14  5012.8 1161.06  5062.9 1162.06  5192.9 1169.82  5312.9 1174.56
  5354.9 1178.93  5405.4 1179.61  5426.4 1178.01  5462.1 1177.67  5533.6 1179.87
    5578 1183.81  5706.1 1191.43  5720.9 1193.32  5842.9 1199.83  5961.5 1203.97
#Mann= 4 ,-1 , 0
  3812.7     .05       0  4982.8     .03       0  5005.8     .05       0
  5961.5     .05       0
Bank Sta=4982.8,5011.36
XS Rating Curve= 0 ,0
Exp/Cntr=0.3,0.1

Type RM Length L Ch R = 1 ,78      ,0,0,0
BEGIN DESCRIPTION:
UNT 1066 IN LATR 1.0
END DESCRIPTION:
XS GIS Cut Line= 4
       2904361.2     10071254.86      2905197.14     10072306.95
       2905423.7     10072317.37      2906223.18     10071749.66
#Sta/Elev= 30
  3594.4 1177.96  3677.2 1175.54  3726.9 1175.79  3755.7 1174.22  3826.2 1173.72
  3883.9 1171.04  3968.8 1171.16  4047.3 1166.58  4167.7 1162.93    4318 1161.71
  4332.4 1160.11    4374 1161.75  4481.4 1159.37  4595.1 1159.78  4673.6  1157.3
  4830.6 1155.54  4901.1 1155.93  4921.9 1155.01  4975.8 1154.64  4980.5  1153.5
  5019.6 1154.96  5079.6 1154.54  5129.7 1155.57  5371.5 1168.24  5722.7 1180.86
  5802.1  1185.3  5894.4 1193.01  6024.7 1200.04  6110.8 1201.88  6145.5 1201.16
#Mann= 4 ,-1 , 0
  3594.4     .03       0  4921.9    .025       0  5019.6     .03       0
  6145.5      .1       0
Bank Sta=4921.9,5019.6
XS Rating Curve= 0 ,0
Exp/Cntr=0.3,0.1

Chan Stop Cuts=-1
Use User Specified Reach Order=0
Composite Channel Slope=5