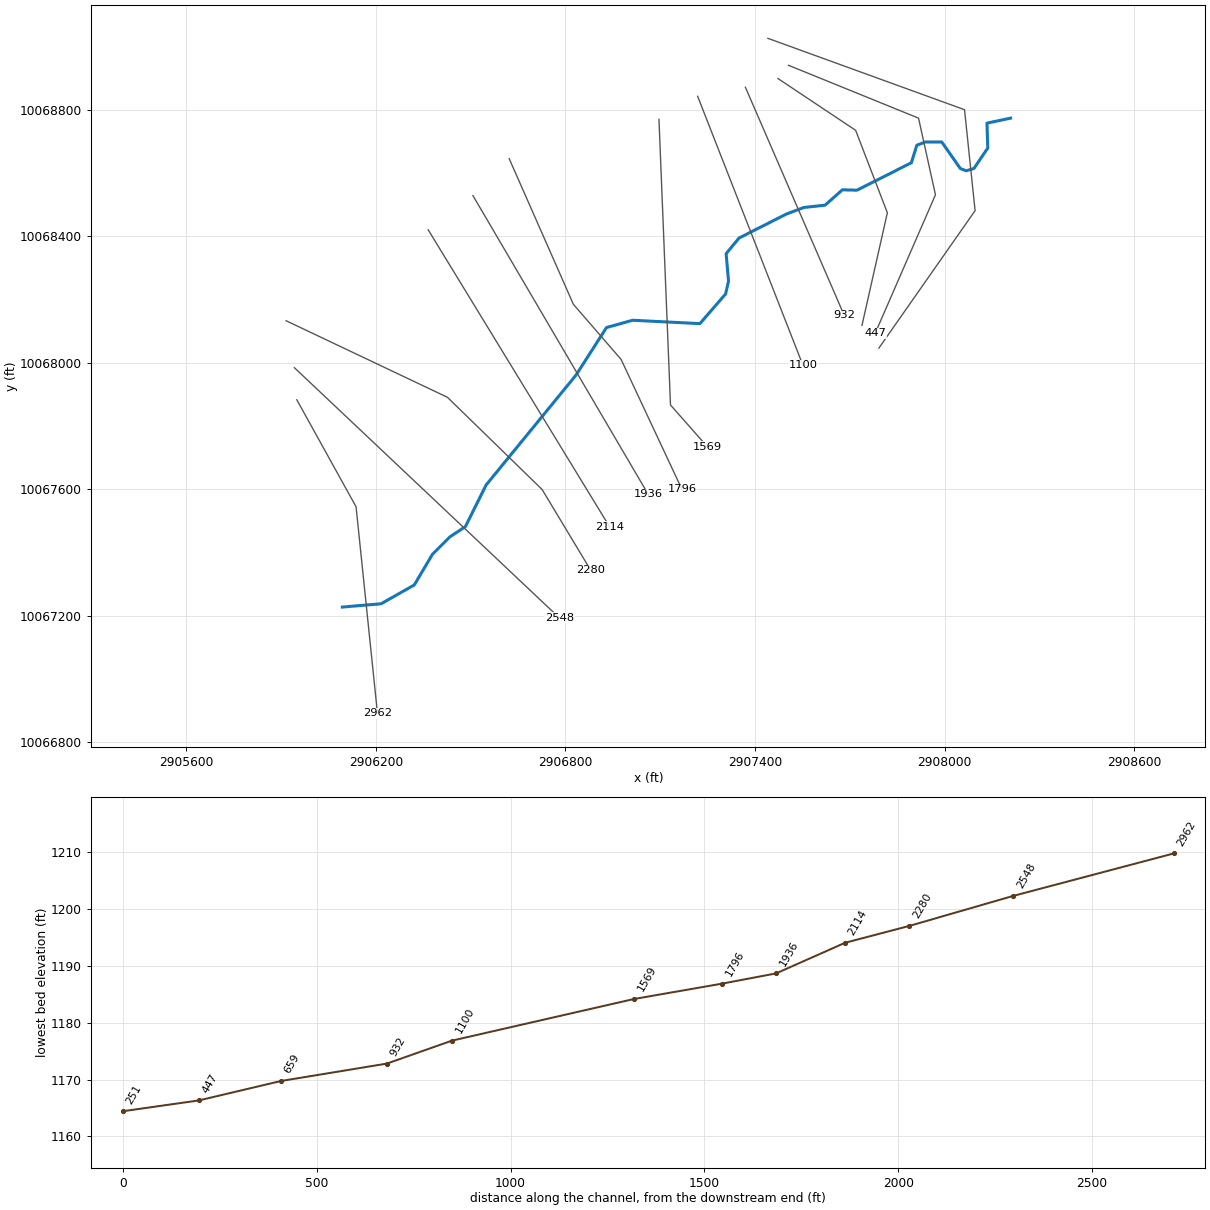
--- UNT 1069 IN LATR.prj (project) ---

Proj Title=UNT 1069 IN LATR Base Level Engineering
Current Plan=p01
Default Exp/Contr=0.3,0.1
English Units
Geom File=g01
Flow File=f01
Plan File=p01
BEGIN DESCRIPTION:
UNT 1069 IN LATR
END DESCRIPTION:

--- UNT 1069 IN LATR.p01 (plan) ---

Plan Title=Multiple Run
Short Identifier=Multiple
Geom File=g01
Flow File=f01
Subcritical Flow
K Sum by GR= 0
Std Step Tol= 0.01
Critical Tol= 0.01
Num of Std Step Trials= 20
Max Error Tol= 0.3
Flow Tol Ratio= 0.001
Split Flow NTrial= 30
Split Flow Tol= 0.02
Split Flow Ratio= 0.02
Log Output Level= 0
Friction Slope Method= 1
Unsteady Friction Slope Method= 2
Unsteady Bridges Friction Slope Method= 1
Parabolic Critical Depth
Global Vel Dist=  1 , 1 , 1
Global Log Level= 0
CheckData=True
Encroach Param= -1, 0, 0, 0
BEGIN DESCRIPTION:
Multiple Run
END DESCRIPTION:

--- UNT 1069 IN LATR.f01 (steady flow) ---

Flow Title=Multiple
Number of Profiles=7
Profile Names=10-year,25-year,50-year,1pct_min,100-year,1pct_plu,500-year
River Rch & RM= UNT 1069 IN LATR,Reach-1,2962
     439     605     742     668     904    1222    1342
Boundary for River Rch & Prof#=UNT 1069 IN LATR,Reach-1,1
Up Type=0
Dn Type=3
Dn Slope=0.005
Boundary for River Rch & Prof#=UNT 1069 IN LATR,Reach-1,2
Up Type=0
Dn Type=3
Dn Slope=0.005
Boundary for River Rch & Prof#=UNT 1069 IN LATR,Reach-1,3
Up Type=0
Dn Type=3
Dn Slope=0.005
Boundary for River Rch & Prof#=UNT 1069 IN LATR,Reach-1,4
Up Type=0
Dn Type=3
Dn Slope=0.005
Boundary for River Rch & Prof#=UNT 1069 IN LATR,Reach-1,5
Up Type=0
Dn Type=3
Dn Slope=0.005
Boundary for River Rch & Prof#=UNT 1069 IN LATR,Reach-1,6
Up Type=0
Dn Type=3
Dn Slope=0.005
Boundary for River Rch & Prof#=UNT 1069 IN LATR,Reach-1,7
Up Type=0
Dn Type=3
Dn Slope=0.005

--- UNT 1069 IN LATR.g01 (geometry) ---

Geom Title=Existing Conditions

River Reach=UNT 1069 IN LATR,Reach-1
Reach XY= 30
      2906094.19     10067226.93      2906216.80     10067237.32
      2906321.80     10067296.83      2906379.40     10067394.00
      2906434.85     10067449.30      2906483.39     10067481.33
      2906549.25     10067613.41      2906833.60     10067961.00
      2906930.00     10068111.25      2907012.56     10068134.33
      2907225.46     10068123.65      2907306.86     10068217.62
      2907316.00     10068258.36      2907308.43     10068344.99
      2907349.23     10068394.45      2907499.69     10068470.63
      2907554.53     10068491.19      2907621.38     10068498.34
      2907676.12     10068546.90      2907722.72     10068546.01
      2907894.51     10068632.65      2907911.80     10068688.07
      2907938.55     10068698.32      2907990.57     10068698.40
      2908049.47     10068614.34      2908067.89     10068607.21
      2908092.43     10068614.52      2908136.23     10068679.32
      2908133.61     10068757.98      2908208.47     10068773.73

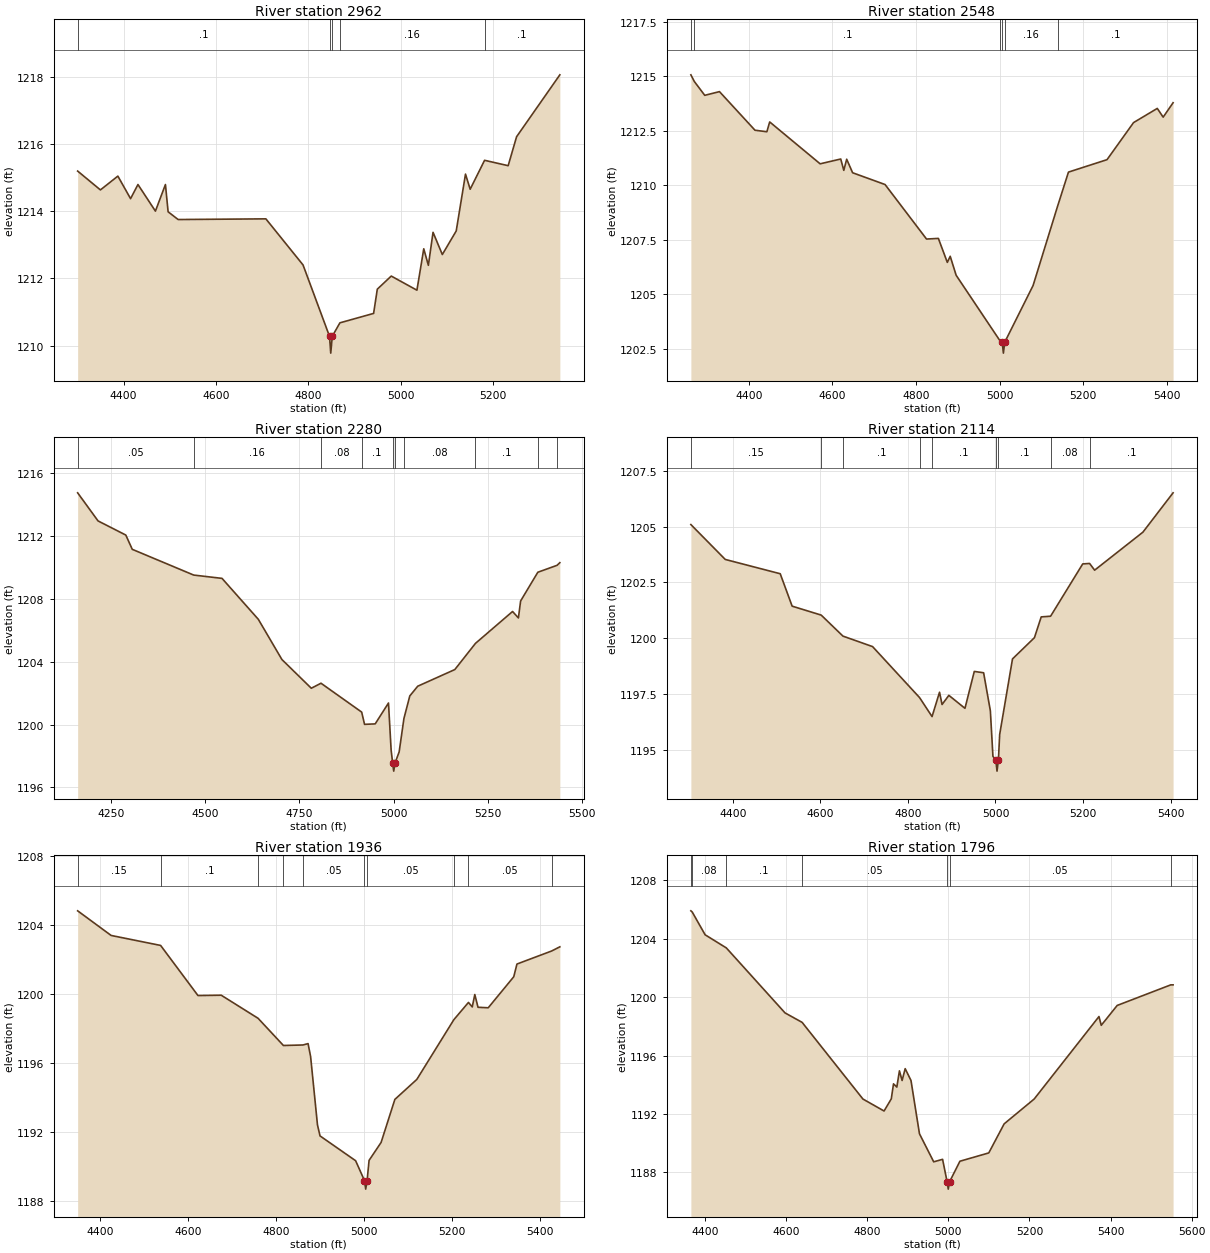
Type RM Length L Ch R = 1,2962,414,414,414
BEGIN DESCRIPTION:
UNT 1069 IN LATR 6.0
END DESCRIPTION:
XS GIS Cut Line= 3
      2905950.10     10067882.81      2906137.61     10067544.25
      2906205.32     10066890.57
#Sta/Elev= 30
  4300.6 1215.19  4349.9 1214.63  4387.7 1215.04  4415.2 1214.37  4431.2 1214.79
  4469.0 1214.00  4490.7 1214.79  4496.5 1213.98  4518.2 1213.75  4708.2 1213.77
  4788.7 1212.40  4846.0 1210.28  4848.7 1209.78  4852.0 1210.28  4868.5 1210.68
  4941.5 1210.96  4949.5 1211.68  4979.7 1212.07  5035.3 1211.65  5050.1 1212.88
  5060.1 1212.39  5070.2 1213.37  5090.3 1212.71  5120.4 1213.41  5140.5 1215.10
  5150.6 1214.65  5181.8 1215.51  5232.9 1215.35  5251.1 1216.21  5344.8 1218.05
#Mann=5,-1,0
  4300.6     0.1       0  4846.0    0.07       0  4852.0     0.1       0
  4868.5    0.16       0  5181.8     0.1       0
Bank Sta=4846,4852
Exp/Cntr=0.3,0.1

Type RM Length L Ch R = 1,2548,268,268,268
BEGIN DESCRIPTION:
Mapping XS 42467ae1
END DESCRIPTION:
XS GIS Cut Line= 2
      2905942.32     10067984.33      2906780.86     10067192.67
#Sta/Elev= 30
  4261.6 1215.07  4270.0 1214.76  4294.8 1214.13  4330.0 1214.30  4414.9 1212.53
  4443.3 1212.46  4450.1 1212.91  4570.7 1210.99  4620.0 1211.21  4627.3 1210.69
  4634.2 1211.20  4648.4 1210.58  4726.0 1210.04  4825.2 1207.54  4853.5 1207.57
  4874.9 1206.47  4881.8 1206.75  4896.0 1205.88  5001.4 1202.86  5006.2 1202.81
  5009.0 1202.31  5012.2 1202.81  5080.0 1205.41  5138.5 1209.04  5164.6 1210.61
  5256.8 1211.18  5320.3 1212.88  5377.0 1213.53  5391.1 1213.13  5414.8 1213.79
#Mann=6,-1,0
  4261.6    0.05       0  4270.0     0.1       0  5001.4    0.16       0
  5006.2    0.07       0  5012.2    0.16       0  5138.5     0.1       0
Bank Sta=5006.2,5012.2
Exp/Cntr=0.3,0.1

Type RM Length L Ch R = 1,2280,166,166,166
BEGIN DESCRIPTION:
Mapping XS ab4f6d22
END DESCRIPTION:
XS GIS Cut Line= 4
      2905916.25     10068132.79      2906426.68     10067890.60
      2906726.15     10067598.93      2906879.80     10067343.72
#Sta/Elev= 30
  4160.7 1214.76  4214.9 1212.97  4288.6 1212.07  4305.8 1211.16  4469.0 1209.52
  4544.2 1209.31  4640.7 1206.70  4703.3 1204.14  4781.4 1202.31  4807.1 1202.63
  4915.2 1200.79  4922.8 1200.01  4951.1 1200.04  4986.4 1201.37  4993.4 1198.38
  4997.5 1197.53  5000.3 1197.03  5003.5 1197.53  5014.7 1198.25  5027.4 1200.38
  5043.0 1201.82  5064.1 1202.44  5162.6 1203.50  5217.5 1205.17  5316.0 1207.20
  5331.5 1206.79  5337.4 1207.87  5383.1 1209.70  5434.0 1210.14  5441.6 1210.31
#Mann=10,-1,0
  4160.7    0.05       0  4469.0    0.16       0  4807.1    0.08       0
  4915.2     0.1       0  4997.5    0.07       0  5003.5     0.1       0
  5027.4    0.08       0  5217.5     0.1       0  5383.1    0.08       0
  5434.0     0.1       0
Bank Sta=4997.5,5003.5
Exp/Cntr=0.3,0.1

Type RM Length L Ch R = 1,2114,178,178,178
BEGIN DESCRIPTION:
Mapping XS c2856ac4
END DESCRIPTION:
XS GIS Cut Line= 2
      2906365.70     10068420.68      2906939.88     10067480.67
#Sta/Elev= 30
  4304.2 1205.09  4382.7 1203.53  4508.3 1202.89  4535.5 1201.44  4601.9 1201.04
  4651.6 1200.10  4719.3 1199.63  4826.6 1197.35  4855.1 1196.50  4872.2 1197.59
  4878.0 1197.04  4893.5 1197.45  4930.3 1196.87  4951.6 1198.52  4972.9 1198.46
  4988.3 1196.76  4994.2 1194.72  5000.7 1194.56  5003.5 1194.06  5006.7 1194.56
  5009.6 1195.70  5038.9 1199.08  5089.0 1200.03  5104.5 1200.96  5125.9 1200.99
  5199.3 1203.33  5215.0 1203.35  5226.5 1203.05  5336.8 1204.75  5405.7 1206.51
#Mann=9,-1,0
  4304.2    0.15       0  4601.9    0.08       0  4651.6     0.1       0
  4826.6    0.08       0  4855.1     0.1       0  5000.7    0.07       0
  5006.7     0.1       0  5125.9    0.08       0  5215.0     0.1       0
Bank Sta=5000.7,5006.7
Exp/Cntr=0.3,0.1

Type RM Length L Ch R = 1,1936,140,140,140
BEGIN DESCRIPTION:
UNT 1069 IN LATR 5.0
END DESCRIPTION:
XS GIS Cut Line= 2
      2906507.41     10068528.61      2907062.08     10067583.33
#Sta/Elev= 30
  4348.5 1204.83  4424.6 1203.40  4537.1 1202.82  4622.0 1199.91  4674.8 1199.93
  4758.6 1198.59  4816.2 1197.01  4860.7 1197.04  4872.2 1197.12  4878.0 1196.37
  4893.6 1192.40  4899.4 1191.76  4980.3 1190.32  5000.4 1189.17  5003.2 1188.67
  5006.4 1189.17  5010.9 1190.34  5038.2 1191.38  5069.5 1193.88  5119.4 1195.04
  5203.6 1198.51  5236.8 1199.51  5245.4 1199.25  5251.2 1199.97  5258.5 1199.23
  5281.7 1199.20  5339.7 1201.00  5347.0 1201.74  5426.1 1202.50  5444.5 1202.74
#Mann=10,-1,0
  4348.5    0.15       0  4537.1     0.1       0  4758.6    0.15       0
  4816.2     0.1       0  4860.7    0.05       0  5000.4    0.04       0
  5006.4    0.05       0  5203.6    0.08       0  5236.8    0.05       0
  5426.1     0.1       0
Bank Sta=5000.4,5006.4
Exp/Cntr=0.3,0.1

Type RM Length L Ch R = 1,1796,227,227,227
BEGIN DESCRIPTION:
Mapping XS 7fc053cb
END DESCRIPTION:
XS GIS Cut Line= 4
      2906621.97     10068645.85      2906825.11     10068184.87
      2906976.15     10068010.39      2907168.87     10067598.91
#Sta/Elev= 30
  4365.3 1205.92  4368.6 1205.84  4400.4 1204.28  4452.7 1203.38  4597.4 1198.93
  4639.6 1198.28  4789.5 1193.03  4841.6 1192.21  4859.4 1193.04  4864.9 1194.07
  4873.1 1193.85  4879.5 1194.96  4886.1 1194.30  4893.7 1195.11  4908.0 1194.30
  4928.9 1190.65  4964.0 1188.73  4985.9 1188.90  4997.1 1187.36  4999.9 1186.86
  5003.1 1187.36  5028.6 1188.77  5099.8 1189.34  5137.7 1191.33  5211.7 1193.03
  5371.5 1198.68  5377.1 1198.08  5416.4 1199.44  5548.6 1200.85  5554.2 1200.85
#Mann=7,-1,0
  4365.3    0.15       0  4368.6    0.08       0  4452.7     0.1       0
  4639.6    0.05       0  4997.1    0.04       0  5003.1    0.05       0
  5548.6     0.1       0
Bank Sta=4997.1,5003.1
Exp/Cntr=0.3,0.1

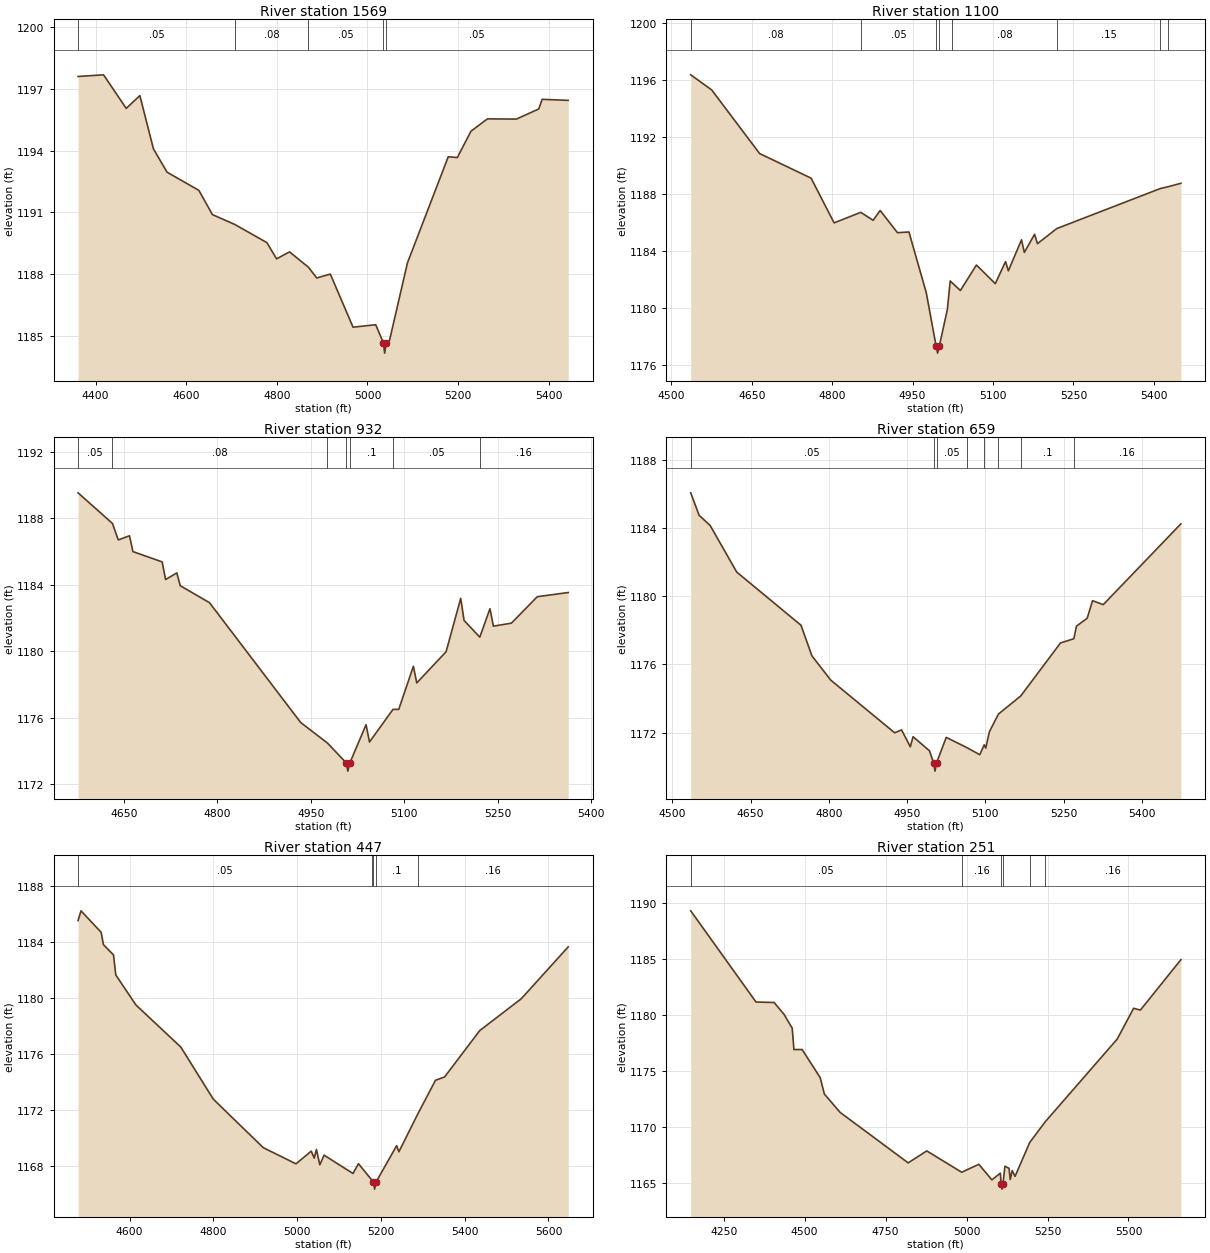
Type RM Length L Ch R = 1,1569,469,469,469
BEGIN DESCRIPTION:
UNT 1069 IN LATR 4.0
END DESCRIPTION:
XS GIS Cut Line= 3
      2907095.94     10068769.99      2907132.40     10067866.29
      2907249.62     10067733.45
#Sta/Elev= 30
  4361.4 1197.60  4417.7 1197.68  4467.7 1196.05  4497.8 1196.67  4527.8 1194.08
  4557.8 1192.95  4627.9 1192.07  4657.9 1190.89  4707.3 1190.41  4778.0 1189.53
  4799.5 1188.74  4828.0 1189.08  4869.9 1188.33  4888.1 1187.81  4918.1 1188.00
  4968.2 1185.42  5018.2 1185.54  5035.2 1184.66  5038.0 1184.16  5041.2 1184.66
  5048.7 1184.78  5088.2 1188.54  5178.3 1193.70  5198.3 1193.66  5228.4 1194.94
  5264.6 1195.54  5328.6 1195.53  5377.9 1196.02  5385.5 1196.49  5443.0 1196.44
#Mann=5,-1,0
  4361.4    0.05       0  4707.3    0.08       0  4869.9    0.05       0
  5035.2    0.04       0  5041.2    0.05       0
Bank Sta=5035.2,5041.2
Exp/Cntr=0.3,0.1

Type RM Length L Ch R = 1,1100,168,168,168
BEGIN DESCRIPTION:
UNT 1069 IN LATR 3.0
END DESCRIPTION:
XS GIS Cut Line= 2
      2907218.34     10068842.86      2907551.68     10067991.27
#Sta/Elev= 30
  4536.1 1196.39  4575.2 1195.33  4664.6 1190.86  4760.7 1189.13  4803.6 1185.99
  4853.3 1186.73  4876.4 1186.17  4889.5 1186.86  4921.8 1185.30  4943.2 1185.35
  4975.5 1181.09  4993.9 1177.34  4996.7 1176.84  4999.9 1177.34  5014.8 1179.89
  5020.2 1181.91  5023.8 1181.78  5039.2 1181.24  5069.1 1183.03  5104.3 1181.72
  5123.4 1183.27  5128.7 1182.62  5153.2 1184.80  5158.5 1183.91  5177.6 1185.19
  5183.0 1184.53  5219.0 1185.59  5412.1 1188.40  5426.8 1188.53  5450.6 1188.77
#Mann=8,-1,0
  4536.1    0.08       0  4853.3    0.05       0  4993.9    0.04       0
  4999.9    0.05       0  5023.8    0.08       0  5219.0    0.15       0
  5412.1    0.08       0  5426.8    0.15       0
Bank Sta=4993.9,4999.9
Exp/Cntr=0.3,0.1

Type RM Length L Ch R = 1,932,273,273,273
BEGIN DESCRIPTION:
UNT 1069 IN LATR 2.0
END DESCRIPTION:
XS GIS Cut Line= 2
      2907369.38     10068871.50      2907681.87     10068150.18
#Sta/Elev= 30
  4576.7 1189.52  4631.9 1187.68  4641.2 1186.69  4659.2 1186.94  4664.7 1185.99
  4711.6 1185.37  4717.1 1184.31  4735.1 1184.71  4740.6 1183.94  4787.5 1182.92
  4933.8 1175.72  4976.6 1174.49  5006.7 1173.30  5009.4 1172.80  5012.7 1173.30
  5038.6 1175.59  5044.1 1174.55  5081.8 1176.51  5091.0 1176.51  5114.5 1179.10
  5119.9 1178.10  5166.9 1179.97  5190.4 1183.18  5195.8 1181.85  5221.0 1180.85
  5237.3 1182.56  5242.8 1181.51  5271.7 1181.69  5313.2 1183.28  5362.8 1183.53
#Mann=7,-1,0
  4576.7    0.05       0  4631.9    0.08       0  4976.6     0.1       0
  5006.7    0.07       0  5012.7     0.1       0  5081.8    0.05       0
  5221.0    0.16       0
Bank Sta=5006.7,5012.7
Exp/Cntr=0.3,0.1

Type RM Length L Ch R = 1,659,212,212,212
BEGIN DESCRIPTION:
Mapping XS 0340c95d
END DESCRIPTION:
XS GIS Cut Line= 4
      2907472.35     10068899.15      2907718.17     10068735.27
      2907818.51     10068474.39      2907738.30     10068118.47
#Sta/Elev= 30
  4535.2 1186.07  4551.3 1184.75  4572.3 1184.16  4623.4 1181.42  4746.6 1178.30
  4767.6 1176.50  4803.7 1175.08  4926.2 1171.99  4939.4 1172.16  4956.2 1171.17
  4961.5 1171.76  4993.0 1170.93  5000.7 1170.24  5003.5 1169.74  5006.7 1170.24
  5025.1 1171.72  5065.3 1171.11  5089.4 1170.70  5097.8 1171.28  5100.8 1171.09
  5107.8 1172.05  5125.2 1173.09  5167.9 1174.15  5244.1 1177.26  5269.7 1177.51
  5274.8 1178.25  5295.3 1178.71  5305.6 1179.74  5326.1 1179.51  5475.0 1184.25
#Mann=8,-1,0
  4535.2    0.05       0  5000.7    0.04       0  5006.7    0.05       0
  5065.3    0.08       0  5097.8     0.1       0  5125.2    0.08       0
  5167.9     0.1       0  5269.7    0.16       0
Bank Sta=5000.7,5006.7
Exp/Cntr=0.3,0.1

Type RM Length L Ch R = 1,447,196,196,196
BEGIN DESCRIPTION:
Mapping XS a68a1ca6
END DESCRIPTION:
XS GIS Cut Line= 4
      2907505.81     10068940.96      2907917.18     10068773.74
      2907970.69     10068531.25      2907780.05     10068093.11
#Sta/Elev= 30
  4477.0 1185.54  4484.1 1186.24  4532.2 1184.70  4537.6 1183.82  4561.7 1183.08
  4567.1 1181.65  4615.2 1179.50  4722.3 1176.49  4799.9 1172.76  4919.1 1169.29
  4997.3 1168.13  5033.7 1169.04  5040.9 1168.54  5046.1 1169.16  5054.2 1168.06
  5064.4 1168.75  5133.4 1167.44  5146.4 1168.14  5178.1 1166.98  5182.3 1166.82
  5185.0 1166.32  5188.3 1166.82  5237.6 1169.43  5243.0 1168.99  5287.4 1171.66
  5330.3 1174.11  5352.1 1174.35  5436.0 1177.67  5535.2 1179.95  5647.2 1183.66
#Mann=5,-1,0
  4477.0    0.05       0  5178.1     0.1       0  5182.3    0.04       0
  5188.3     0.1       0  5287.4    0.16       0
Bank Sta=5182.3,5188.3
Exp/Cntr=0.3,0.1

Type RM Length L Ch R = 1,251,0,0,0
BEGIN DESCRIPTION:
UNT 1069 IN LATR 1.0
END DESCRIPTION:
XS GIS Cut Line= 4
      2907440.55     10069026.27      2908062.67     10068800.50
      2908096.12     10068481.07      2907791.72     10068046.22
#Sta/Elev= 30
  4148.2 1189.32  4349.8 1181.16  4405.7 1181.12  4436.3 1180.06  4461.6 1178.82
  4466.9 1176.91  4492.2 1176.91  4548.1 1174.39  4560.9 1172.93  4609.4 1171.29
  4819.7 1166.77  4877.2 1167.84  4985.0 1165.93  5038.0 1166.64  5078.2 1165.25
  5104.5 1165.85  5106.6 1164.92  5109.3 1164.42  5112.6 1164.92  5118.5 1166.47
  5131.2 1166.28  5134.9 1165.28  5141.0 1166.08  5149.8 1165.56  5195.0 1168.59
  5243.4 1170.46  5465.4 1177.85  5516.0 1180.60  5536.9 1180.44  5662.0 1184.95
#Mann=6,-1,0
  4148.2    0.05       0  4985.0    0.16       0  5106.6    0.07       0
  5112.6    0.16       0  5195.0     0.1       0  5243.4    0.16       0
Bank Sta=5106.6,5112.6
Exp/Cntr=0.3,0.1

Chan Stop Cuts=-1