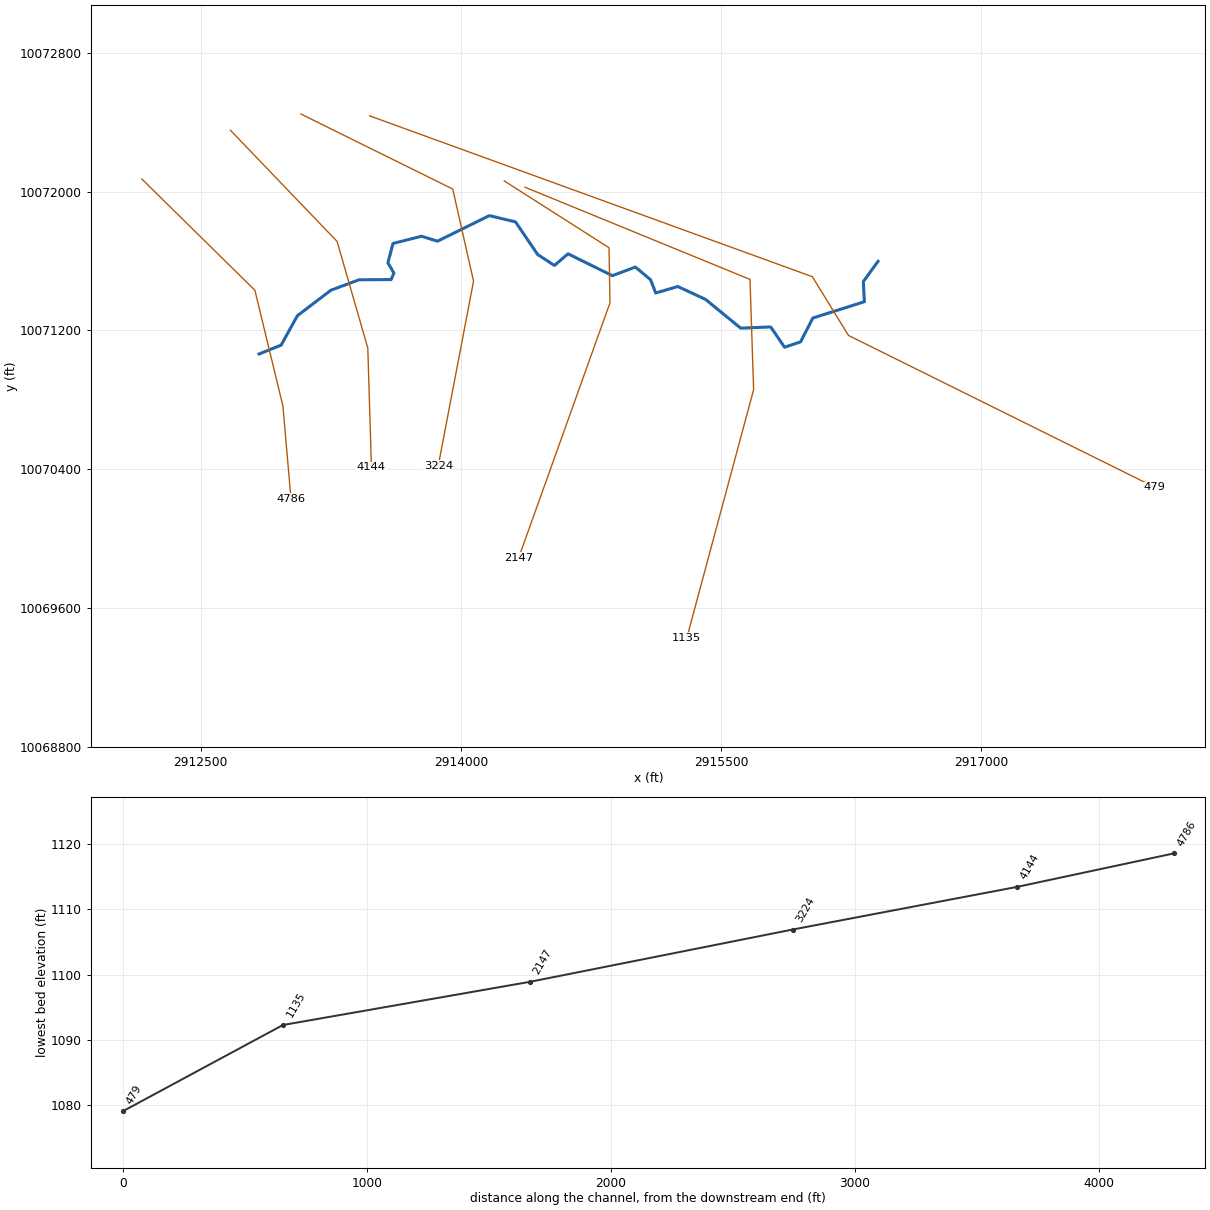
--- UNT 1070 IN LATR.prj (project) ---

Proj Title=UNT 1070 IN LATR Base Level Engineering
Current Plan=p01
Default Exp/Contr=0.3,0.1
English Units
Geom File=g01
Flow File=f01
Plan File=p01
BEGIN DESCRIPTION:
UNT 1070 IN LATR
END DESCRIPTION:

--- UNT 1070 IN LATR.p01 (plan) ---

Plan Title=Multiple Run
Short Identifier=Multiple
Geom File=g01
Flow File=f01
Subcritical Flow
K Sum by GR= 0
Std Step Tol= 0.01
Critical Tol= 0.01
Num of Std Step Trials= 20
Max Error Tol= 0.3
Flow Tol Ratio= 0.001
Split Flow NTrial= 30
Split Flow Tol= 0.02
Split Flow Ratio= 0.02
Log Output Level= 0
Friction Slope Method= 1
Unsteady Friction Slope Method= 2
Unsteady Bridges Friction Slope Method= 1
Parabolic Critical Depth
Global Vel Dist=  1 , 1 , 1
Global Log Level= 0
CheckData=True
Encroach Param= -1, 0, 0, 0
BEGIN DESCRIPTION:
Multiple Run
END DESCRIPTION:

--- UNT 1070 IN LATR.f01 (steady flow) ---

Flow Title=Multiple
Number of Profiles=7
Profile Names=10-year,25-year,50-year,1pct_min,100-year,1pct_plu,500-year
River Rch & RM= UNT 1070 IN LATR,Reach-1,4786
     833    1190    1496    1376    1861    2517    2891
River Rch & RM= UNT 1070 IN LATR,Reach-1,479
    1000    1446    1831    1697    2294    3103    3615
Boundary for River Rch & Prof#=UNT 1070 IN LATR,Reach-1,1
Up Type=0
Dn Type=3
Dn Slope=0.005
Boundary for River Rch & Prof#=UNT 1070 IN LATR,Reach-1,2
Up Type=0
Dn Type=3
Dn Slope=0.005
Boundary for River Rch & Prof#=UNT 1070 IN LATR,Reach-1,3
Up Type=0
Dn Type=3
Dn Slope=0.005
Boundary for River Rch & Prof#=UNT 1070 IN LATR,Reach-1,4
Up Type=0
Dn Type=3
Dn Slope=0.005
Boundary for River Rch & Prof#=UNT 1070 IN LATR,Reach-1,5
Up Type=0
Dn Type=3
Dn Slope=0.005
Boundary for River Rch & Prof#=UNT 1070 IN LATR,Reach-1,6
Up Type=0
Dn Type=3
Dn Slope=0.005
Boundary for River Rch & Prof#=UNT 1070 IN LATR,Reach-1,7
Up Type=0
Dn Type=3
Dn Slope=0.005

--- UNT 1070 IN LATR.g01 (geometry) ---

Geom Title=Existing Conditions

River Reach=UNT 1070 IN LATR,Reach-1
Reach XY= 30
      2912837.42     10071064.21      2912964.40     10071115.46
      2913058.03     10071284.80      2913251.11     10071431.70
      2913413.74     10071491.93      2913598.46     10071493.26
      2913614.50     10071530.35      2913579.91     10071589.82
      2913609.17     10071701.40      2913773.79     10071742.99
      2913865.72     10071714.42      2914164.48     10071861.65
      2914315.33     10071825.96      2914443.01     10071637.75
      2914539.99     10071574.46      2914618.28     10071641.78
      2914873.57     10071515.61      2915006.70     10071565.43
      2915094.47     10071491.79      2915123.55     10071415.60
      2915251.05     10071453.27      2915411.15     10071378.83
      2915613.32     10071213.21      2915786.48     10071220.20
      2915866.32     10071103.29      2915958.47     10071133.73
      2916029.27     10071271.50      2916326.64     10071365.57
      2916320.36     10071481.47      2916405.54     10071598.61

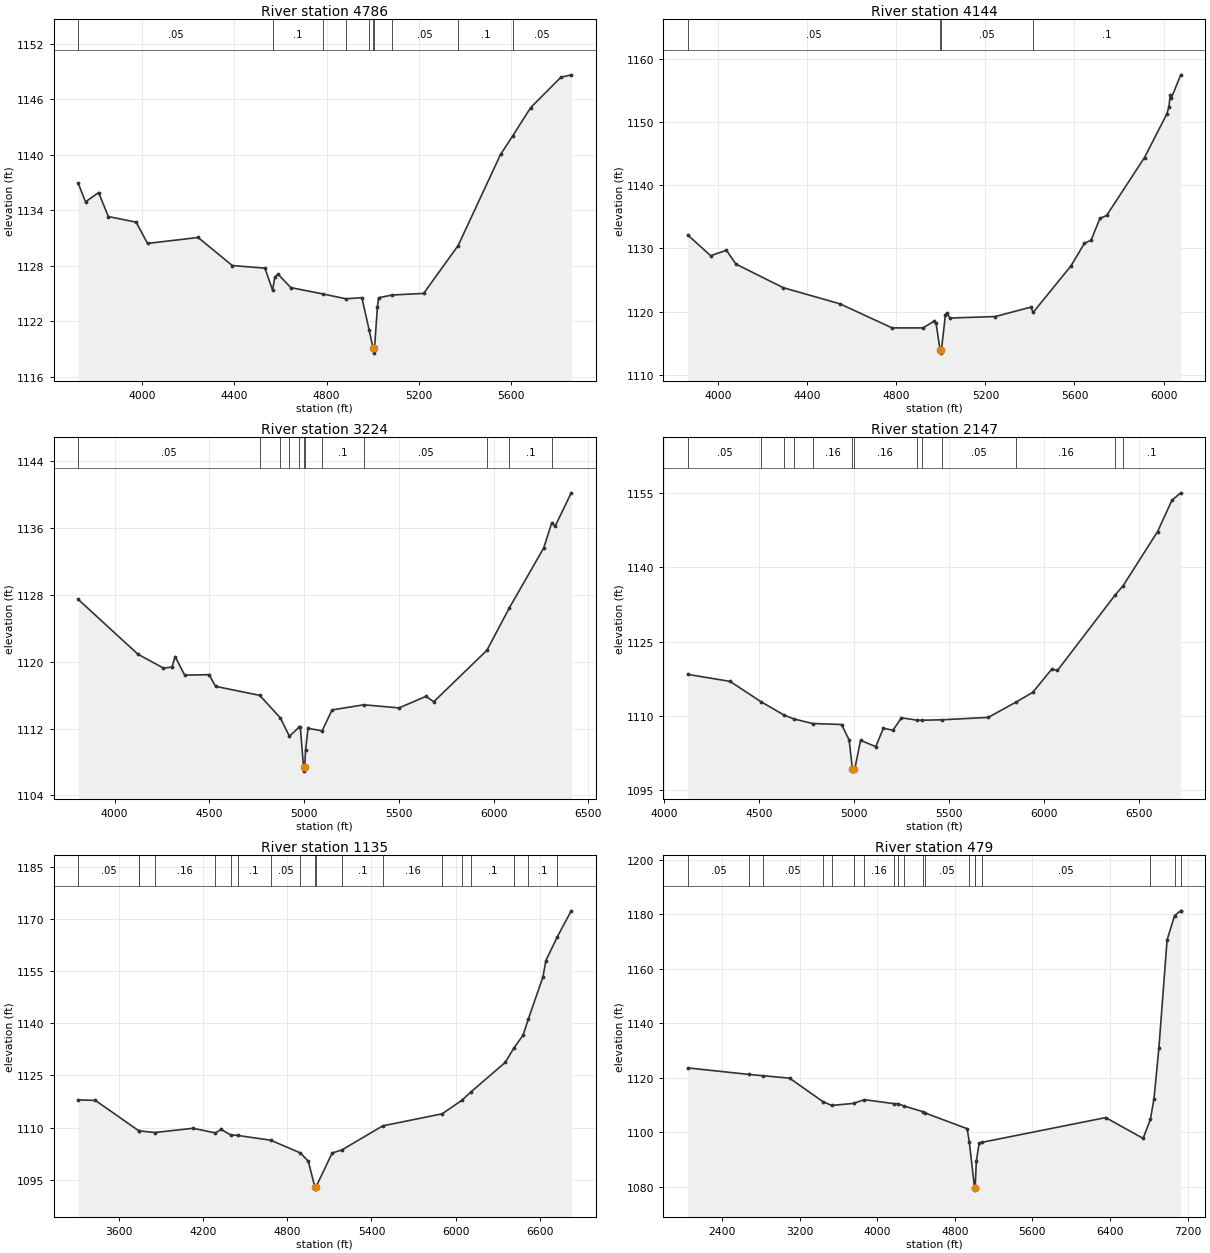
Type RM Length L Ch R = 1,4786,642,642,642
BEGIN DESCRIPTION:
UNT 1070 IN LATR 8.0
END DESCRIPTION:
XS GIS Cut Line= 4
      2912161.97     10072072.31      2912813.02     10071431.68
      2912974.48     10070765.01      2913021.34     10070228.69
#Sta/Elev= 30
  3722.9 1136.93  3754.8 1134.92  3811.4 1135.92  3853.8 1133.33  3974.0 1132.73
  4023.5 1130.43  4242.7 1131.07  4391.2 1128.04  4532.6 1127.76  4565.8 1125.37
  4575.0 1126.76  4589.1 1127.12  4644.5 1125.66  4784.1 1124.97  4884.2 1124.45
  4953.1 1124.57  4984.4 1121.08  5001.6 1119.08  5004.3 1118.58  5007.6 1119.08
  5020.3 1123.57  5025.4 1124.56  5084.6 1124.86  5220.7 1125.03  5370.3 1130.20
  5554.4 1140.05  5607.6 1142.07  5684.9 1145.10  5815.4 1148.37  5860.6 1148.64
#Mann=10,-1,0
  3722.9    0.05       0  4565.8     0.1       0  4784.1    0.05       0
  4884.2     0.1       0  4984.4    0.16       0  5001.6    0.07       0
  5007.6    0.16       0  5084.6    0.05       0  5370.3     0.1       0
  5607.6    0.05       0
Bank Sta=5001.6,5007.6
Exp/Cntr=0.3,0.1

Type RM Length L Ch R = 1,4144,920,920,920
BEGIN DESCRIPTION:
UNT 1070 IN LATR 7.0
END DESCRIPTION:
XS GIS Cut Line= 4
      2912672.41     10072353.54      2913286.98     10071712.93
      2913464.06     10071098.35      2913484.89     10070410.88
#Sta/Elev= 30
  3862.4 1132.13  3965.5 1128.85  4036.3 1129.71  4078.8 1127.53  4291.0 1123.80
  4545.5 1121.25  4780.5 1117.44  4919.5 1117.44  4967.8 1118.47  4978.2 1118.15
  4996.1 1113.95  4998.8 1113.45  5002.1 1113.95  5019.9 1119.42  5025.7 1119.77
  5040.7 1119.00  5243.4 1119.23  5404.3 1120.72  5414.1 1119.88  5584.4 1127.25
  5644.4 1130.80  5674.5 1131.30  5714.5 1134.75  5744.5 1135.21  5914.6 1144.37
  6014.6 1151.23  6024.6 1152.42  6030.0 1154.31  6035.0 1153.76  6077.5 1157.44
#Mann=4,-1,0
  3862.4    0.05       0  4996.1   0.035       0  5002.1    0.05       0
  5414.1     0.1       0
Bank Sta=4996.1,5002.1
Exp/Cntr=0.3,0.1

Type RM Length L Ch R = 1,3224,1077,1077,1077
BEGIN DESCRIPTION:
UNT 1070 IN LATR 6.0
END DESCRIPTION:
XS GIS Cut Line= 4
      2913078.64     10072447.31      2913953.64     10072015.01
      2914073.44     10071483.76      2913870.31     10070421.26
#Sta/Elev= 30
  3807.7 1127.47  4123.0 1120.91  4257.6 1119.25  4302.5 1119.36  4319.4 1120.63
  4369.8 1118.40  4498.9 1118.46  4532.5 1117.06  4766.0 1115.98  4874.9 1113.28
  4922.3 1111.09  4974.8 1112.19  4979.8 1112.23  4997.3 1107.41  5000.0 1106.91
  5003.3 1107.41  5007.8 1109.42  5020.8 1112.04  5095.2 1111.73  5147.7 1114.24
  5315.5 1114.85  5501.4 1114.48  5643.2 1115.86  5684.6 1115.22  5965.1 1121.38
  6083.1 1126.44  6265.0 1133.64  6306.1 1136.56  6326.0 1136.27  6410.0 1140.23
#Mann=12,-1,0
  3807.7    0.05       0  4766.0     0.1       0  4874.9    0.16       0
  4922.3     0.1       0  4974.8    0.16       0  4997.3    0.07       0
  5003.3    0.16       0  5095.2     0.1       0  5315.5    0.05       0
  5965.1    0.16       0  6083.1     0.1       0  6306.1    0.05       0
Bank Sta=4997.3,5003.3
Exp/Cntr=0.3,0.1

Type RM Length L Ch R = 1,2147,1012,1012,1012
BEGIN DESCRIPTION:
UNT 1070 IN LATR 4.0
END DESCRIPTION:
XS GIS Cut Line= 4
      2914250.49     10072061.91      2914854.69     10071676.47
      2914859.89     10071358.76      2914333.86     10069890.05
#Sta/Elev= 30
  4125.7 1118.42  4348.7 1117.00  4513.5 1112.84  4633.7 1110.18  4684.9 1109.42
  4782.9 1108.50  4935.1 1108.30  4975.1 1105.17  4992.1 1099.39  4994.9 1098.89
  4998.1 1099.39  5005.1 1099.40  5035.1 1105.11  5115.1 1103.83  5155.1 1107.53
  5205.7 1107.16  5250.4 1109.65  5330.0 1109.19  5356.2 1109.16  5462.3 1109.25
  5707.2 1109.73  5852.9 1112.82  5940.9 1114.78  6040.5 1119.43  6071.3 1119.21
  6375.9 1134.49  6417.1 1136.33  6598.4 1147.25  6673.8 1153.57  6720.2 1155.06
#Mann=13,-1,0
  4125.7    0.05       0  4513.5     0.1       0  4633.7    0.16       0
  4684.9     0.1       0  4782.9    0.16       0  4992.1    0.07       0
  4998.1    0.16       0  5330.0    0.05       0  5356.2     0.1       0
  5462.3    0.05       0  5852.9    0.16       0  6375.9    0.05       0
  6417.1     0.1       0
Bank Sta=4992.1,4998.1
Exp/Cntr=0.3,0.1

Type RM Length L Ch R = 1,1135,656,656,656
BEGIN DESCRIPTION:
UNT 1070 IN LATR 2.0
END DESCRIPTION:
XS GIS Cut Line= 4
      2914370.29     10072025.44      2915667.19     10071494.18
      2915688.02     10070858.76      2915303.33     10069429.17
#Sta/Elev= 30
  3307.6 1117.98  3430.4 1117.81  3739.9 1109.08  3744.3 1109.04  3852.8 1108.57
  4126.9 1109.79  4286.9 1108.46  4327.3 1109.46  4395.5 1107.89  4445.0 1107.73
  4680.1 1106.37  4893.5 1102.69  4949.7 1100.25  4996.7 1092.77  4999.4 1092.27
  5002.7 1092.77  5119.8 1102.68  5188.3 1103.54  5480.7 1110.49  5904.3 1113.96
  6044.9 1117.84  6112.4 1120.35  6354.6 1128.77  6417.0 1132.95  6481.2 1136.58
  6520.0 1141.32  6623.8 1153.40  6644.5 1158.11  6726.1 1164.93  6825.3 1172.42
#Mann=19,-1,0
  3307.6    0.05       0  3739.9    0.16       0  3744.3     0.1       0
  3852.8    0.16       0  4286.9     0.1       0  4395.5    0.16       0
  4445.0     0.1       0  4680.1    0.05       0  4893.5    0.16       0
  4996.7    0.07       0  5002.7    0.16       0  5188.3     0.1       0
  5480.7    0.16       0  5904.3     0.1       0  6044.9    0.16       0
  6112.4     0.1       0  6417.0    0.05       0  6520.0     0.1       0
  6726.1    0.16       0
Bank Sta=4996.7,5002.7
Exp/Cntr=0.3,0.1

Type RM Length L Ch R = 1,479,0,0,0
BEGIN DESCRIPTION:
UNT 1070 IN LATR 1.0
END DESCRIPTION:
XS GIS Cut Line= 4
      2913474.50     10072436.88      2916026.56     10071509.81
      2916234.89     10071171.26      2918000.53     10070296.26
#Sta/Elev= 30
  2046.5 1123.61  2678.2 1121.21  2827.2 1120.72  3097.1 1119.83  3441.5 1111.19
  3531.3 1109.81  3756.8 1110.58  3865.9 1111.93  4171.1 1110.48  4215.1 1110.43
  4277.7 1109.57  4472.9 1107.51  4491.0 1107.08  4927.5 1101.26  4949.1 1096.45
  5003.7 1079.55  5006.5 1079.05  5009.7 1079.55  5022.1 1089.36  5050.7 1095.87
  5079.9 1096.25  6355.2 1105.34  6741.9 1097.71  6816.3 1104.66  6854.0 1112.31
  6904.4 1130.94  6988.5 1170.59  7066.0 1179.61  7127.7 1181.35  7129.8 1181.35
#Mann=19,-1,0
  2046.5    0.05       0  2678.2     0.1       0  2827.2    0.05       0
  3441.5     0.1       0  3531.3    0.16       0  3756.8     0.1       0
  3865.9    0.16       0  4171.1    0.05       0  4215.1     0.1       0
  4277.7    0.05       0  4472.9     0.1       0  4491.0    0.05       0
  4949.1    0.16       0  5003.7    0.07       0  5009.7    0.16       0
  5079.9    0.05       0  6816.3    0.16       0  7066.0     0.1       0
  7127.7    0.05       0
Bank Sta=5003.7,5009.7
Exp/Cntr=0.3,0.1

Chan Stop Cuts=-1