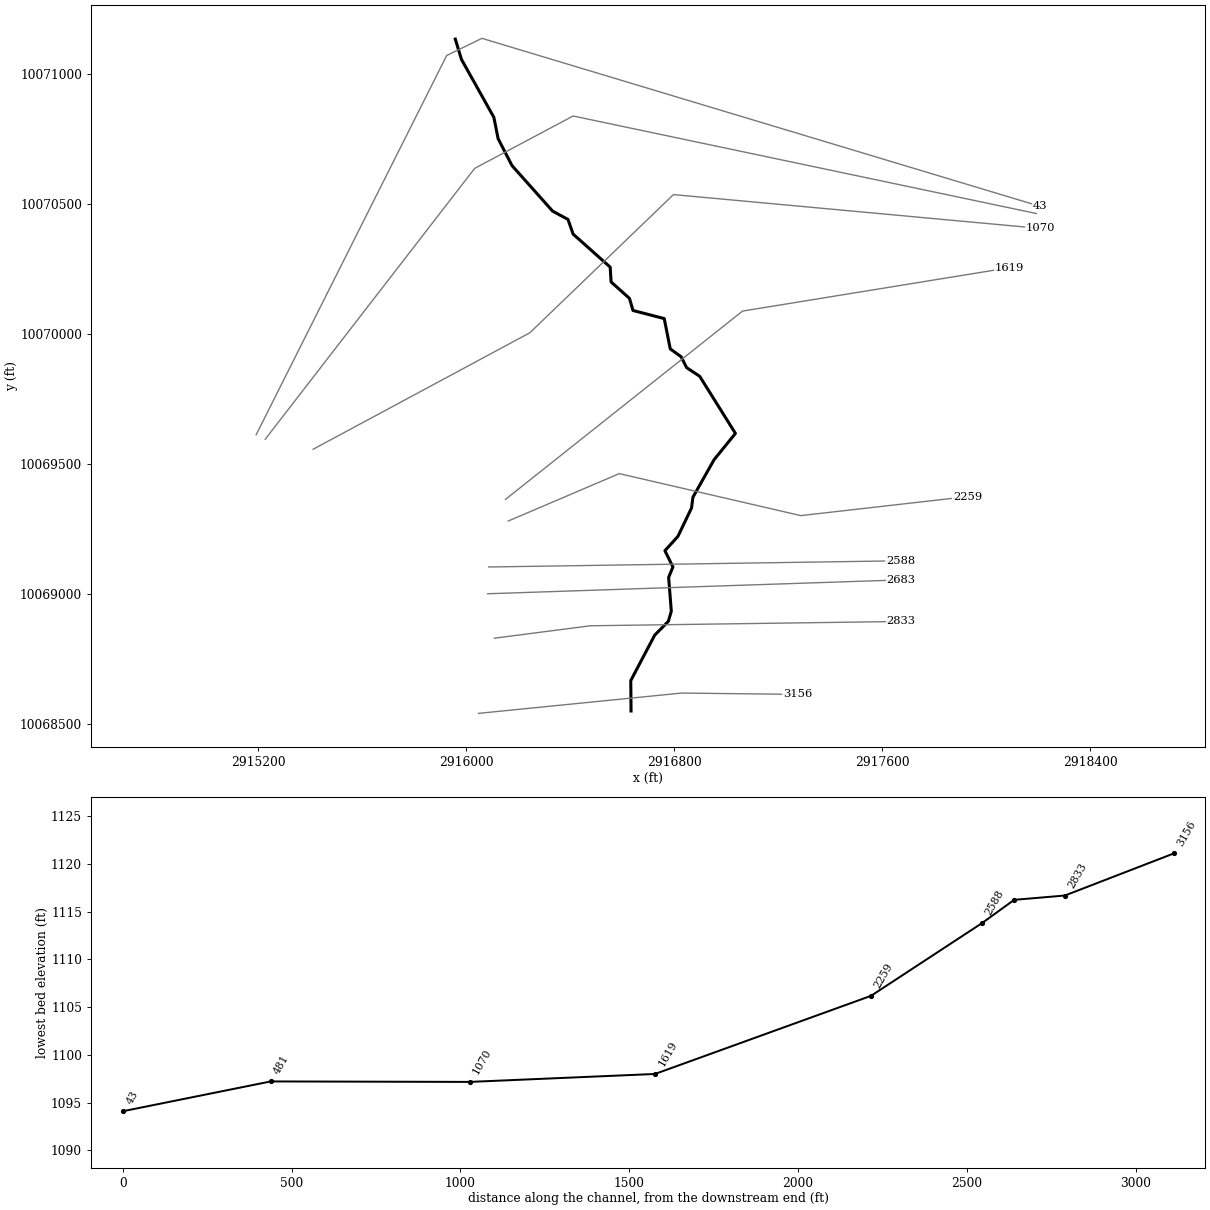
--- UNT 1071 IN LATR.prj (project) ---

Proj Title=UNT 1071 IN LATR Base Level Engineering
Current Plan=p01
Default Exp/Contr=0.3,0.1
English Units
Geom File=g01
Flow File=f01
Plan File=p01
Y Axis Title=Elevation
X Axis Title(PF)=Main Channel Distance
X Axis Title(XS)=Station
BEGIN DESCRIPTION:
UNT 1071 IN LATR
END DESCRIPTION:
DSS Export Rating Curves= 0
DSS Export Rating Curve Sorted= 0
DSS Export Volume Flow Curves= 0
DXF OffsetX= 0
DXF OffsetY= 0
DXF ScaleX= 1
DXF ScaleY= 10

--- UNT 1071 IN LATR.p01 (plan) ---

Plan Title=Multiple Run
Short Identifier=Multiple
Geom File=g01
Flow File=f01
Subcritical Flow
K Sum by GR= 0
Std Step Tol= 0.01
Critical Tol= 0.01
Num of Std Step Trials= 20
Max Error Tol= 0.3
Flow Tol Ratio= 0.001
Split Flow NTrial= 30
Split Flow Tol= 0.02
Split Flow Ratio= 0.02
Log Output Level= 0
Friction Slope Method= 1
Unsteady Friction Slope Method= 2
Unsteady Bridges Friction Slope Method= 1
Parabolic Critical Depth
Global Vel Dist=  1 , 1 , 1
Global Log Level= 0
CheckData=True
Encroach Param= -1, 0, 0, 0
BEGIN DESCRIPTION:
Multiple Run
END DESCRIPTION:

--- UNT 1071 IN LATR.f01 (steady flow) ---

Flow Title=Multiple
Program Version=4.10
Number of Profiles= 7
Profile Names=10-year,25-year,50-year,1pct_min,100-year,1pct_plu,500-year
River Rch & RM=UNT 1071 IN LATR,Reach-1         ,3156
     331     450     548     491     664     898     974
Boundary for River Rch & Prof#=UNT 1071 IN LATR,Reach-1         , 1
Up Type= 0
Dn Type= 3
Dn Slope=0.012
Boundary for River Rch & Prof#=UNT 1071 IN LATR,Reach-1         , 2
Up Type= 0
Dn Type= 3
Dn Slope=0.012
Boundary for River Rch & Prof#=UNT 1071 IN LATR,Reach-1         , 3
Up Type= 0
Dn Type= 3
Dn Slope=0.012
Boundary for River Rch & Prof#=UNT 1071 IN LATR,Reach-1         , 4
Up Type= 0
Dn Type= 3
Dn Slope=0.012
Boundary for River Rch & Prof#=UNT 1071 IN LATR,Reach-1         , 5
Up Type= 0
Dn Type= 3
Dn Slope=0.012
Boundary for River Rch & Prof#=UNT 1071 IN LATR,Reach-1         , 6
Up Type= 0
Dn Type= 3
Dn Slope=0.012
Boundary for River Rch & Prof#=UNT 1071 IN LATR,Reach-1         , 7
Up Type= 0
Dn Type= 3
Dn Slope=0.012
DSS Import GetInterval= 0
DSS Import GetPeak= 0
DSS Import FillOption= 0

--- UNT 1071 IN LATR.g01 (geometry) ---

Geom Title=Existing Conditions
Program Version=4.10

River Reach=UNT 1071 IN LATR,Reach-1
Reach XY= 30
      2916634.25     10068550.21      2916633.18     10068667.11
      2916725.27      10068841.9      2916777.75     10068894.97
      2916789.07       10068934.      2916778.77     10069063.85
      2916795.32     10069104.22      2916764.46     10069166.51
      2916814.37     10069221.47      2916866.85      10069330.8
      2916872.16      10069372.2      2916953.57     10069516.53
      2917035.63     10069617.57      2916898.14     10069837.28
      2916847.95     10069870.42      2916826.81     10069912.33
      2916785.02     10069942.54      2916761.83     10070059.05
       2916641.8     10070090.25      2916628.07     10070136.88
      2916557.57     10070199.96      2916554.09     10070256.86
      2916411.56     10070383.94      2916391.77      10070440.3
      2916332.69     10070472.21      2916176.49     10070647.38
       2916123.1     10070750.94      2916106.71     10070833.08
      2915982.34     10071055.34      2915958.47     10071133.73

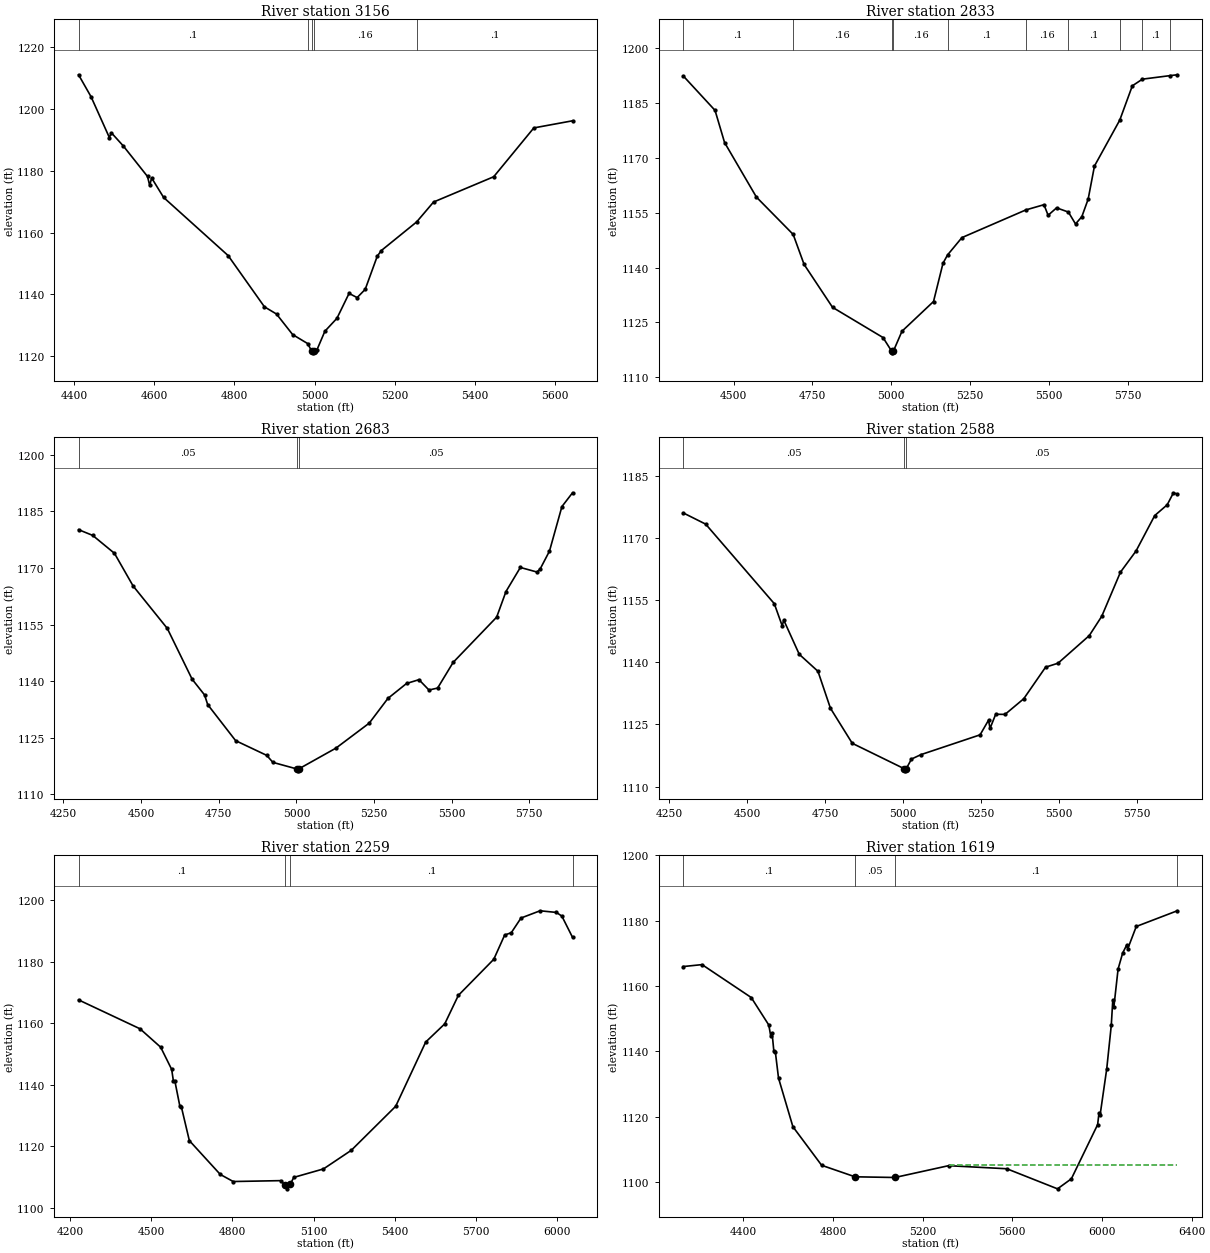
Type RM Length L Ch R = 1 ,3156    ,323,323,323
BEGIN DESCRIPTION:
UNT 1071 IN LATR 6.0
END DESCRIPTION:
XS GIS Cut Line= 3
      2916047.42     10068541.06      2916828.64     10068619.18
      2917274.99     10068613.99
#Sta/Elev= 30
  4411.6    1211  4442.8 1203.89  4488.4 1190.71  4493.4 1192.25  4523.2 1187.98
  4583.5 1178.12  4588.9 1175.25  4593.9 1177.62  4623.7 1171.33  4784.5 1152.54
    4875 1135.97  4905.1 1133.64  4945.3    1127    4983 1124.07  4992.9 1121.59
  4995.6 1121.09  4998.9 1121.59  5005.6 1121.96  5025.7 1128.07  5055.8 1132.26
    5086 1140.31  5106.1 1138.95  5126.2 1141.61  5156.3 1152.34  5166.4 1154.16
  5254.5 1163.42  5296.6 1169.85  5446.6 1178.03  5546.6 1193.82  5643.1 1196.12
#Mann= 5 ,-1 , 0
  4411.6      .1       0    4983     .16       0  4992.9     .07       0
  4998.9     .16       0  5254.5      .1       0
Bank Sta=4992.9,4998.9
XS Rating Curve= 0 ,0
Exp/Cntr=0.3,0.1

Type RM Length L Ch R = 1 ,2833    ,150,150,150
BEGIN DESCRIPTION:
Mapping XS 01cac372
END DESCRIPTION:
XS GIS Cut Line= 3
       2916108.7     10068830.11       2916478.1      10068877.9
      2917670.81     10068894.44
#Sta/Elev= 30
  4340.8 1192.41  4441.4    1183  4471.6  1174.2  4572.5 1159.28    4689 1149.07
  4723.6 1140.86  4813.7 1129.13  4973.7 1120.86  5000.7 1117.18  5003.4 1116.68
  5006.7 1117.18  5033.7 1122.58  5133.7 1130.72  5163.7 1141.17  5178.1 1143.45
  5223.7  1148.2  5426.2 1155.77  5483.7  1157.2  5496.8 1154.31  5523.7 1156.34
    5561 1155.19  5583.7 1151.93  5603.7 1153.93  5623.7 1158.71  5643.7 1167.78
  5723.9 1180.34  5763.7 1189.72  5795.6 1191.54  5883.3 1192.51  5906.1 1192.74
#Mann= 10 ,-1 , 0
  4340.8      .1       0    4689     .16       0  5000.7     .07       0
  5006.7     .16       0  5178.1      .1       0  5426.2     .16       0
    5561      .1       0  5723.9     .16       0  5795.6      .1       0
  5883.3     .16       0
Bank Sta=5000.7,5006.7
XS Rating Curve= 0 ,0
Exp/Cntr=0.3,0.1

Type RM Length L Ch R = 1 ,2683    ,95,95,95
BEGIN DESCRIPTION:
Mapping XS 5cbe6f8a
END DESCRIPTION:
XS GIS Cut Line= 2
      2916082.93     10069001.02      2917672.64     10069054.32
#Sta/Elev= 30
  4298.5 1180.15  4344.1 1178.62  4414.1 1173.88  4474.1 1165.23  4584.2 1153.98
  4664.2 1140.51  4704.3 1136.34  4714.3 1133.79  4804.3 1124.23  4904.4 1120.33
  4924.4 1118.47  5001.4 1116.73  5004.2 1116.23  5007.4 1116.73  5127.5 1122.26
  5234.6 1128.88  5294.6 1135.42  5354.6 1139.38  5394.6 1140.39  5426.8 1137.65
  5454.7 1138.17  5504.7 1144.97  5644.8 1156.96  5674.8 1163.75  5721.1 1170.13
  5774.9 1168.91  5784.9 1169.73  5814.9 1174.47  5854.9 1186.26  5889.1 1189.92
#Mann= 3 ,-1 , 0
  4298.5     .05       0  5001.4     .04       0  5007.4     .05       0
Bank Sta=5001.4,5007.4
XS Rating Curve= 0 ,0
Exp/Cntr=0.3,0.1

Type RM Length L Ch R = 1 ,2588    ,329,329,329
BEGIN DESCRIPTION:
UNT 1071 IN LATR 5.0
END DESCRIPTION:
XS GIS Cut Line= 2
      2916086.66     10069103.94      2917670.78     10069127.83
#Sta/Elev= 30
  4295.2 1175.98    4367 1173.28    4587 1154.11  4612.4 1148.77  4617.4 1150.14
  4667.1  1141.9  4727.1  1137.8  4767.1  1128.9  4837.1 1120.44  5004.1  1114.3
  5006.8  1113.8  5010.1  1114.3  5027.1 1116.64  5057.1  1117.7  5247.1 1122.48
  5274.1    1126  5279.1 1124.04  5297.1 1127.44  5327.1 1127.41  5387.1 1131.18
  5457.1 1138.79  5497.1 1139.75  5597.2  1146.4  5637.2 1151.05  5697.2 1161.69
  5747.2  1166.8  5807.2 1175.35  5847.2 1177.94  5867.2 1180.84  5879.5 1180.54
#Mann= 3 ,-1 , 0
  4295.2     .05       0  5004.1     .04       0  5010.1     .05       0
Bank Sta=5004.1,5010.1
XS Rating Curve= 0 ,0
Exp/Cntr=0.3,0.1

Type RM Length L Ch R = 1 ,2259    ,640,640,640
BEGIN DESCRIPTION:
Mapping XS cd36ff26
END DESCRIPTION:
XS GIS Cut Line= 4
      2916161.96     10069280.63      2916589.06     10069462.93
      2917286.98     10069301.47      2917927.62     10069374.39
#Sta/Elev= 30
  4231.3 1167.66  4458.5 1158.25  4534.8 1152.26  4575.4 1145.04    4582 1141.16
  4587.4 1141.17  4605.6 1133.11    4611 1132.94  4640.7 1121.88  4755.1 1110.86
  4802.9 1108.56  4978.9 1108.85  4992.7 1107.48  5002.7 1106.18  5013.3 1107.64
  5026.8 1109.91  5136.4 1112.66  5239.1 1118.71  5403.3 1133.04  5514.2 1153.94
  5584.6 1159.86  5634.9 1169.13  5765.8 1180.87    5806 1188.75  5830.6 1189.53
  5866.4 1194.29  5936.9 1196.65  5997.3 1196.11  6017.4 1194.91  6056.8 1188.01
#Mann= 4 ,-1 , 0
  4231.3      .1       0  4992.7     .05       0  5013.3      .1       0
  6056.8     .05       0
Bank Sta=4992.7,5013.3
XS Rating Curve= 0 ,0
Exp/Cntr=0.3,0.1

Type RM Length L Ch R = 1 ,1619    ,549,549,549
BEGIN DESCRIPTION:
UNT 1071 IN LATR 3.0
END DESCRIPTION:
XS GIS Cut Line= 3
      2916151.53     10069363.95      2917063.02     10070087.93
      2918089.05      10070254.6
#Sta/Elev= 30
  4132.1 1165.97  4215.7 1166.56  4435.1  1156.5  4513.6 1148.08  4521.7 1144.87
  4528.1 1145.67  4536.1 1140.06  4542.5 1139.97  4556.9 1131.86    4621    1117
  4749.2  1105.2  4898.1 1101.68    5076 1101.47 5315.34 1105.08  5575.2 1104.14
  5801.4    1098  5863.2 1101.07  5980.4 1117.64  5986.3 1121.17  5991.4 1120.58
  6020.9 1134.66  6041.2 1147.96  6047.9 1155.65    6053 1153.74  6071.6 1165.21
  6091.9 1170.07  6109.5 1172.49  6114.6 1171.38  6152.7 1178.22  6335.6 1183.02
#Mann= 4 ,-1 , 0
  4132.1      .1       0  4898.1     .05       0    5076      .1       0
  6335.6     .05       0
#XS Ineff= 2 , 0
                         5322.44         1105.38
Permanent Ineff=
       T       T
Bank Sta=4898.1,5076
XS Rating Curve= 0 ,0
Exp/Cntr=0.3,0.1

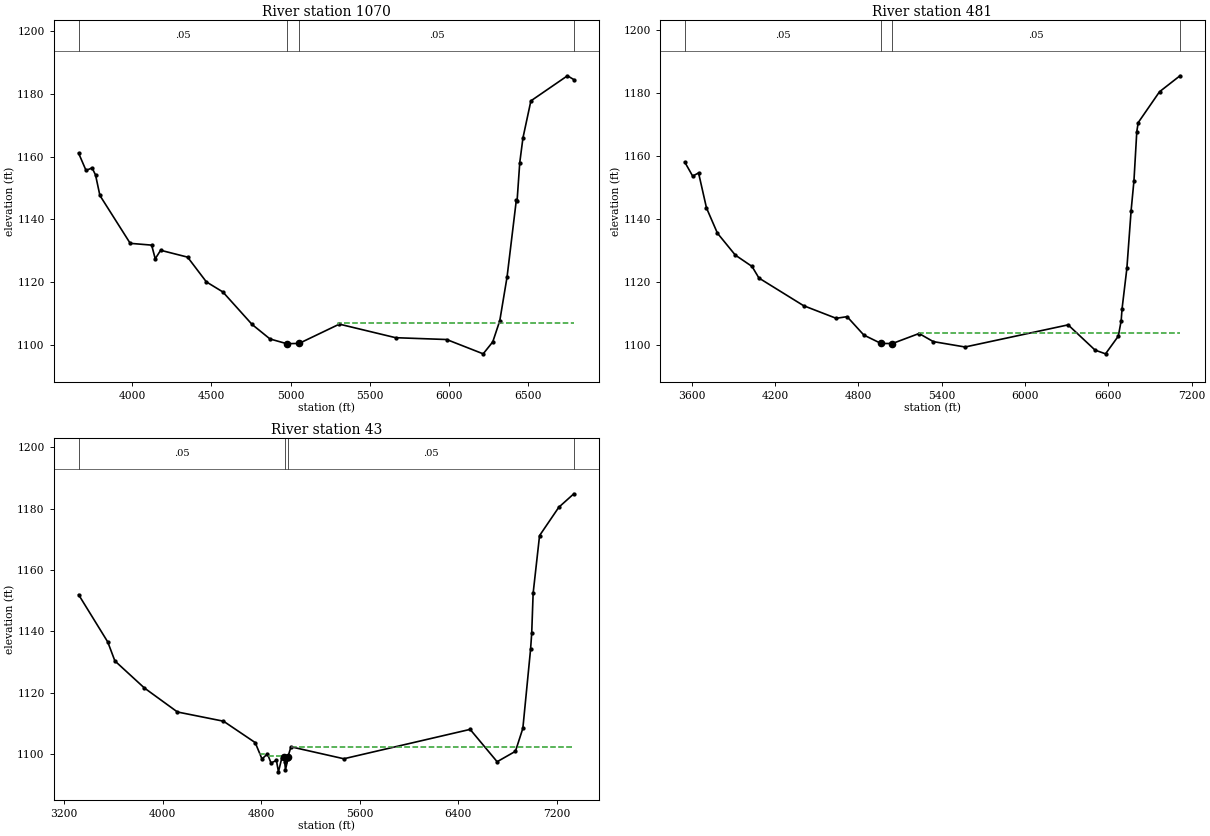
Type RM Length L Ch R = 1 ,1070    ,589,589,589
BEGIN DESCRIPTION:
UNT 1071 IN LATR 2.0
END DESCRIPTION:
XS GIS Cut Line= 4
      2915411.97     10069556.67      2916245.31      10070004.6
      2916797.39     10070535.85      2918208.83     10070405.64
#Sta/Elev= 30
  3660.4 1161.06  3707.3 1155.57  3745.4 1156.39  3767.3 1154.14  3794.9  1147.6
  3986.5 1132.36  4121.9 1131.79  4144.6 1127.44  4178.7 1130.15    4349 1127.97
  4467.8 1120.08  4571.7 1116.89  4756.6 1106.53  4869.8 1101.91  4975.8  1100.4
  5053.8 1100.49  5308.2 1106.63  5663.9 1102.31  5986.3 1101.73  6217.1 1097.17
  6277.6 1100.98  6321.9  1107.7    6368 1121.65  6426.5  1146.1  6431.5    1146
  6448.3  1158.1  6468.4 1165.93  6518.6 1177.73  6749.6 1185.72  6790.1  1184.5
#Mann= 4 ,-1 , 0
  3660.4     .05       0  4975.8     .35       0  5053.8     .05       0
  6790.1     .05       0
#XS Ineff= 2 , 0
                          5301.7         1107.03
Permanent Ineff=
       T       T
Bank Sta=4975.8,5053.8
XS Rating Curve= 0 ,0
Exp/Cntr=0.3,0.1

Type RM Length L Ch R = 1 ,481     ,438,438,438
BEGIN DESCRIPTION:
Mapping XS 28e4ebd6
END DESCRIPTION:
XS GIS Cut Line= 4
      2915227.53     10069595.02      2916033.06     10070636.65
      2916411.53     10070838.04       2918192.8     10070463.03
#Sta/Elev= 30
  3549.9 1158.04  3606.9  1153.6  3649.4 1154.59  3706.5 1143.48  3785.3 1135.48
  3913.9 1128.54  4034.3 1124.94  4084.1 1121.26  4405.6 1112.49  4640.1 1108.49
  4718.9 1109.01  4839.3 1103.18  4963.4 1100.51  5044.9 1100.49    5237 1103.67
  5339.4  1101.1  5568.2 1099.39  6310.2 1106.41  6504.4  1098.4  6579.6 1097.22
  6671.8 1102.84  6692.3 1107.75  6698.5 1111.47  6733.2  1124.3  6763.8 1142.66
  6784.3 1152.14  6804.7 1167.71  6814.9 1170.56  6968.2 1180.34  7115.7 1185.41
#Mann= 4 ,-1 , 0
  3549.9     .05       0  4963.4     .35       0  5044.9     .05       0
  7115.7     .05       0
#XS Ineff= 2 , 0
                         5234.09         1103.73
Permanent Ineff=
       T       T
Bank Sta=4963.4,5044.9
XS Rating Curve= 0 ,0
Exp/Cntr=0.3,0.1

Type RM Length L Ch R = 1 ,43      ,0,0,0
BEGIN DESCRIPTION:
UNT 1071 IN LATR 1.0
END DESCRIPTION:
XS GIS Cut Line= 4
       2915192.8     10069612.37      2915925.42     10071070.68
      2916060.84     10071136.65       2918205.1     10070491.29
#Sta/Elev= 30
  3317.4 1151.93  3553.9 1136.51    3612 1130.31    3852 1121.46    4120 1113.64
    4494 1110.63  4751.4 1103.65  4806.6  1098.3  4851.2 1099.96  4879.7 1096.99
  4923.8 1097.83  4940.3  1094.1  4968.6 1098.77  4985.6 1099.03  4991.2 1097.28
  4997.3  1094.8 5016.44 1098.18 5017.96 1099.08  5041.8 1102.27  5471.4 1098.37
  6496.9 1107.96  6716.2  1097.4    6865 1100.81  6925.1  1108.3  6987.7 1134.05
  6997.1 1139.42  7008.6 1152.41  7060.8 1171.23  7217.5  1180.5  7339.3 1184.88
#Mann= 4 ,-1 , 0
  3317.4     .05       0  4991.2    .035       0 5016.44     .05       0
  7339.3     .05       0
#XS Ineff= 3 ,-1
 4784.88 4851.17 1099.96 4855.89 4974.98 1099.13 5041.41  7339.3 1102.29
Permanent Ineff=
       T       T       T
Bank Sta=4985.6,5017.96
XS Rating Curve= 0 ,0
Exp/Cntr=0.3,0.1

Chan Stop Cuts=-1
Use User Specified Reach Order=0
Composite Channel Slope=5