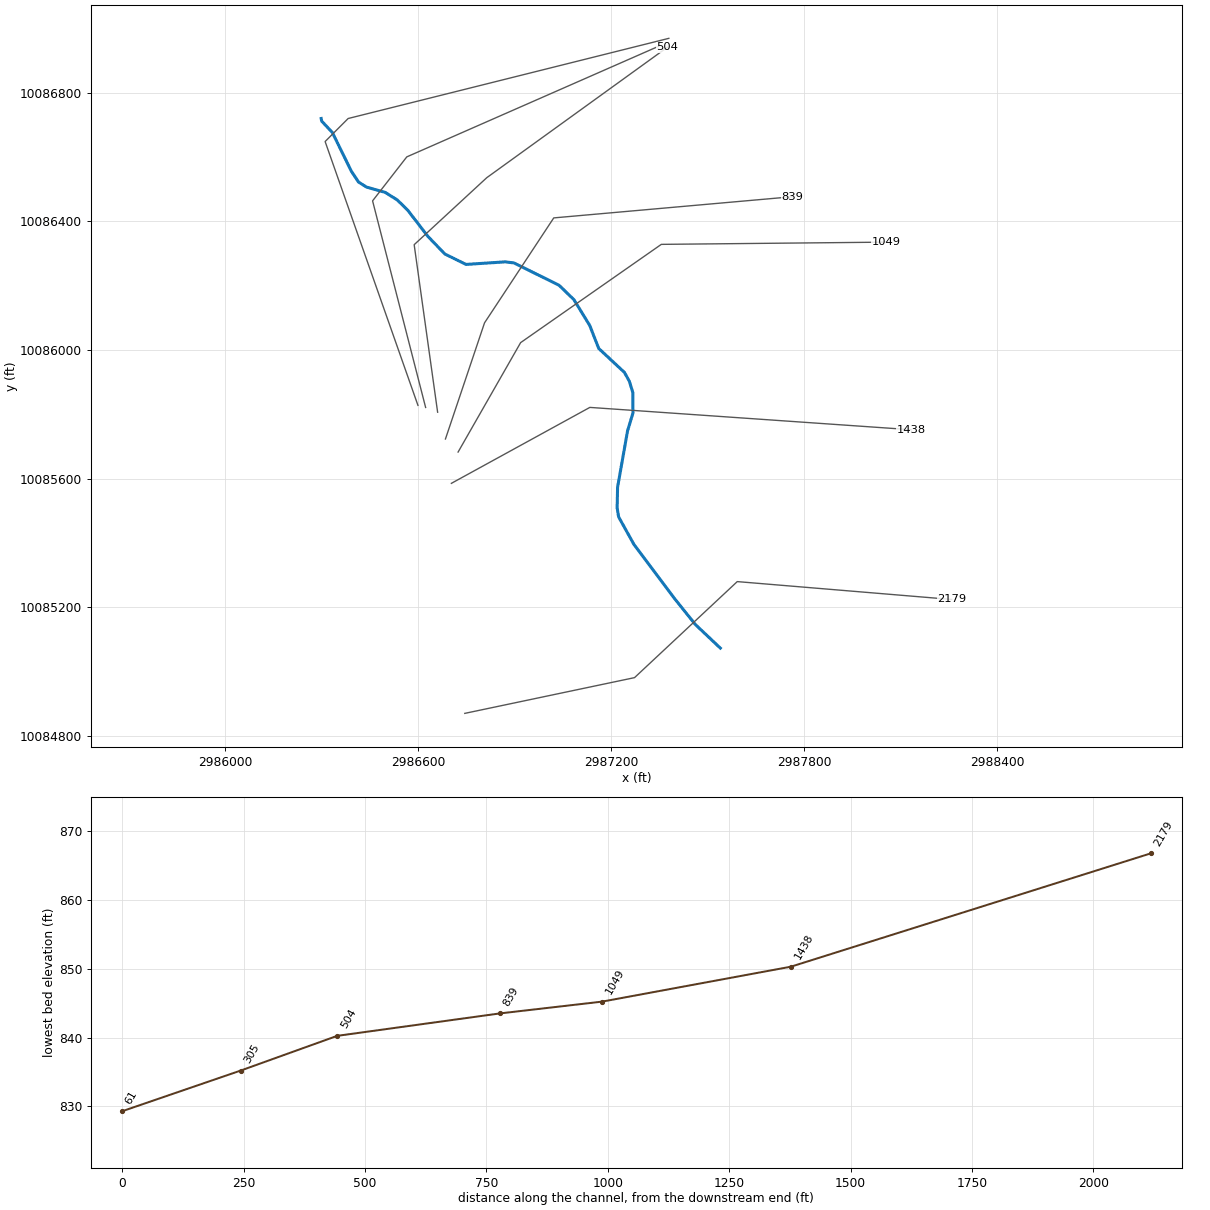
--- UNT 1073 IN LATR.prj (project) ---

Proj Title=UNT 1073 IN LATR Base Level Engineering
Current Plan=p01
Default Exp/Contr=0.3,0.1
English Units
Geom File=g01
Flow File=f01
Plan File=p01
Y Axis Title=Elevation
X Axis Title(PF)=Main Channel Distance
X Axis Title(XS)=Station
BEGIN DESCRIPTION:
UNT 1073 IN LATR
END DESCRIPTION:
DSS Export Rating Curves= 0
DSS Export Rating Curve Sorted= 0
DSS Export Volume Flow Curves= 0
DXF OffsetX= 0
DXF OffsetY= 0
DXF ScaleX= 1
DXF ScaleY= 10

--- UNT 1073 IN LATR.p01 (plan) ---

Plan Title=Multiple Run
Short Identifier=Multiple
Geom File=g01
Flow File=f01
Subcritical Flow
K Sum by GR= 0
Std Step Tol= 0.01
Critical Tol= 0.01
Num of Std Step Trials= 20
Max Error Tol= 0.3
Flow Tol Ratio= 0.001
Split Flow NTrial= 30
Split Flow Tol= 0.02
Split Flow Ratio= 0.02
Log Output Level= 0
Friction Slope Method= 1
Unsteady Friction Slope Method= 2
Unsteady Bridges Friction Slope Method= 1
Parabolic Critical Depth
Global Vel Dist=  1 , 1 , 1
Global Log Level= 0
CheckData=True
Encroach Param= -1, 0, 0, 0
BEGIN DESCRIPTION:
Multiple Run
END DESCRIPTION:

--- UNT 1073 IN LATR.f01 (steady flow) ---

Flow Title=Multiple
Program Version=4.10
Number of Profiles= 7
Profile Names=10-year,25-year,50-year,1pct_min,100-year,1pct_plu,500-year
River Rch & RM=UNT 1073 IN LATR,Reach-1         ,2179
     837    1221    1557    1457    1970    2664    3161
Boundary for River Rch & Prof#=UNT 1073 IN LATR,Reach-1         , 1
Up Type= 0
Dn Type= 3
Dn Slope=0.024
Boundary for River Rch & Prof#=UNT 1073 IN LATR,Reach-1         , 2
Up Type= 0
Dn Type= 3
Dn Slope=0.024
Boundary for River Rch & Prof#=UNT 1073 IN LATR,Reach-1         , 3
Up Type= 0
Dn Type= 3
Dn Slope=0.024
Boundary for River Rch & Prof#=UNT 1073 IN LATR,Reach-1         , 4
Up Type= 0
Dn Type= 3
Dn Slope=0.024
Boundary for River Rch & Prof#=UNT 1073 IN LATR,Reach-1         , 5
Up Type= 0
Dn Type= 3
Dn Slope=0.024
Boundary for River Rch & Prof#=UNT 1073 IN LATR,Reach-1         , 6
Up Type= 0
Dn Type= 3
Dn Slope=0.024
Boundary for River Rch & Prof#=UNT 1073 IN LATR,Reach-1         , 7
Up Type= 0
Dn Type= 3
Dn Slope=0.024
DSS Import GetInterval= 0
DSS Import GetPeak= 0
DSS Import FillOption= 0

--- UNT 1073 IN LATR.g01 (geometry) ---

Geom Title=Existing Conditions

River Reach=UNT 1073 IN LATR,Reach-1
Reach XY= 30
      2987539.07     10085073.04      2987461.69     10085146.07
      2987396.31     10085227.49      2987270.82     10085394.71
      2987222.87     10085480.87      2987218.27     10085508.73
      2987219.59     10085573.19      2987250.51     10085747.90
      2987267.47     10085804.27      2987266.95     10085868.01
      2987256.14     10085902.78      2987241.01     10085930.14
      2987160.96     10086004.70      2987133.04     10086076.19
      2987083.68     10086156.59      2987037.53     10086201.28
      2986897.20     10086270.74      2986869.79     10086273.96
      2986748.35     10086266.00      2986682.50     10086298.45
      2986629.70     10086353.30      2986567.86     10086433.63
      2986534.89     10086466.30      2986496.94     10086490.11
      2986439.35     10086506.35      2986414.23     10086521.97
      2986391.92     10086555.59      2986332.79     10086676.09
      2986299.51     10086711.65      2986297.92     10086719.66

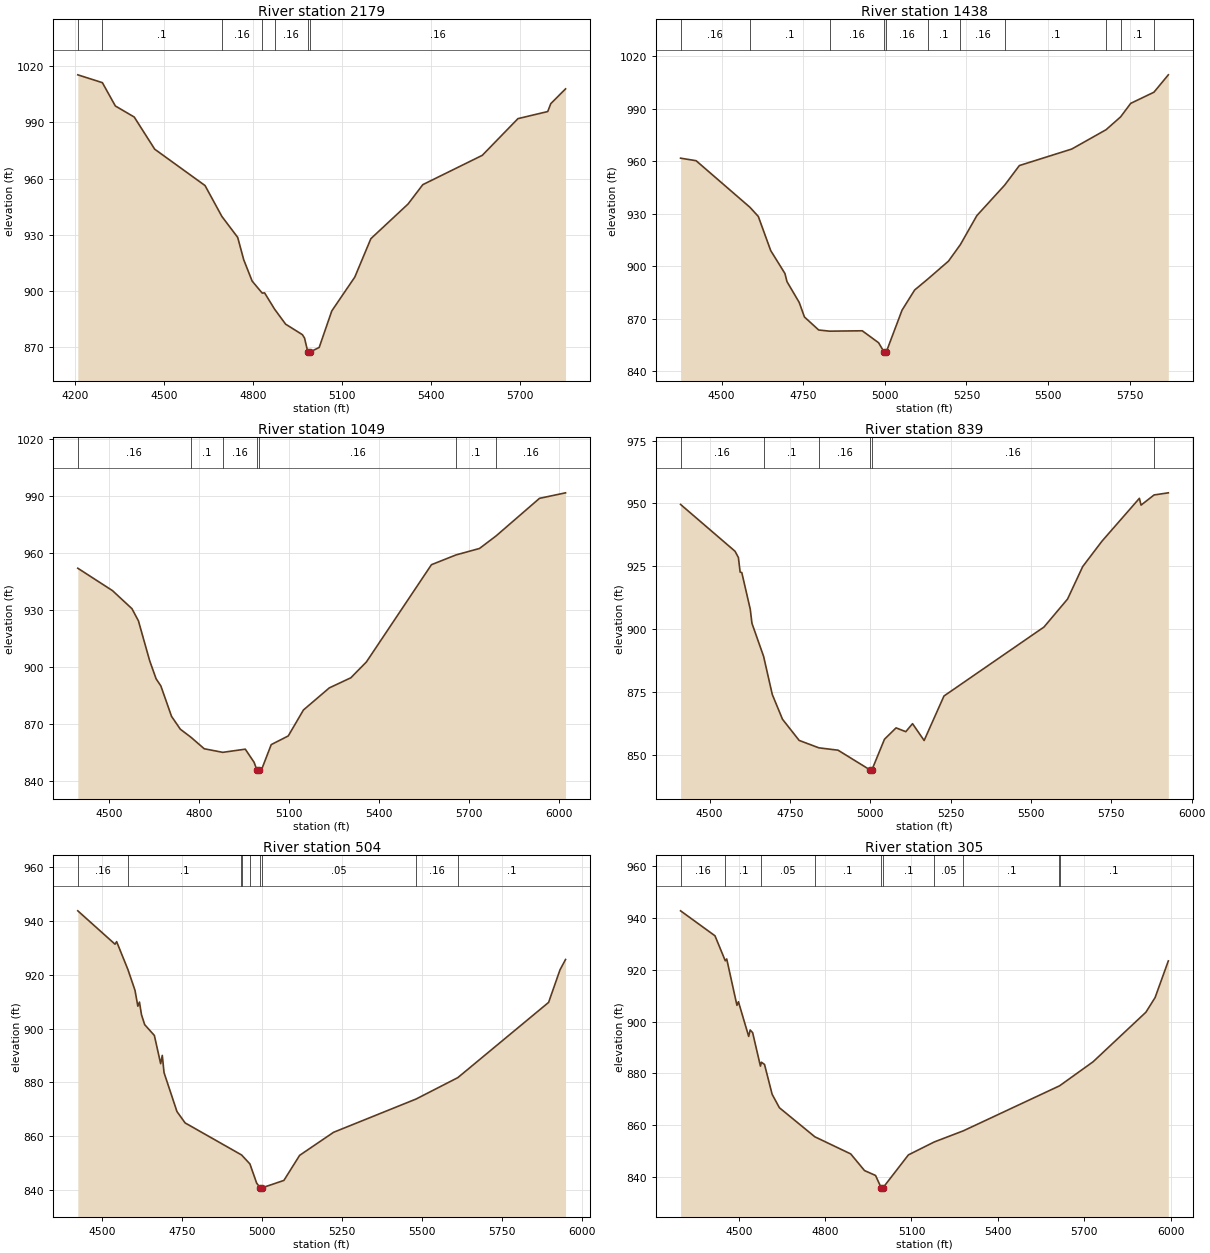
Type RM Length L Ch R = 1,2179,741,741,741
BEGIN DESCRIPTION:
UNT 1073 IN LATR 4.0
END DESCRIPTION:
XS GIS Cut Line= 4
      2986744.50     10084870.05      2987272.30     10084981.17
      2987591.74     10085279.78      2988258.39     10085224.23
#Sta/Elev= 30
  4209.0 1015.44  4291.9 1011.26  4335.7  998.80  4399.4  992.90  4468.5  975.72
  4638.3  956.30  4695.2  939.79  4748.4  928.63  4768.9  916.64  4797.2  905.28
  4831.1  898.86  4839.2  898.97  4872.9  890.29  4910.1  882.27  4966.7  876.66
  4974.0  874.84  4985.2  867.29  4988.0  866.79  4991.2  867.29  5023.4  869.82
  5065.9  889.33  5143.6  907.42  5197.8  927.93  5323.3  946.44  5373.0  956.78
  5573.7  972.44  5694.1  992.05  5794.5  995.83  5804.9 1000.08  5854.6 1007.94
#Mann=7,-1,0
  4209.0    0.16       0  4291.9     0.1       0  4695.2    0.16       0
  4831.1    0.05       0  4872.9    0.16       0  4985.2    0.07       0
  4991.2    0.16       0
Bank Sta=4985.2,4991.2
Exp/Cntr=0.3,0.1

Type RM Length L Ch R = 1,1438,389,389,389
BEGIN DESCRIPTION:
UNT 1073 IN LATR 3.0
END DESCRIPTION:
XS GIS Cut Line= 3
      2986702.83     10085585.32      2987133.41     10085821.45
      2988133.42     10085752.00
#Sta/Elev= 30
  4374.6  961.66  4422.1  960.22  4586.9  933.63  4612.6  928.38  4650.6  908.88
  4694.2  895.78  4700.4  891.16  4737.8  879.29  4753.9  870.96  4797.5  863.53
  4830.9  862.86  4930.9  863.08  4981.0  856.24  4998.1  850.82  5000.8  850.32
  5004.1  850.82  5052.7  874.85  5091.3  886.37  5132.0  892.69  5195.0  902.88
  5231.2  912.26  5281.7  928.84  5366.9  946.25  5412.0  957.45  5572.4  966.88
  5677.5  977.92  5721.9  985.23  5752.9  992.96  5824.0  999.33  5868.1 1009.26
#Mann=11,-1,0
  4374.6    0.16       0  4586.9     0.1       0  4830.9    0.16       0
  4998.1    0.07       0  5004.1    0.16       0  5132.0     0.1       0
  5231.2    0.16       0  5366.9     0.1       0  5677.5    0.16       0
  5721.9     0.1       0  5824.0    0.16       0
Bank Sta=4998.1,5004.1
Exp/Cntr=0.3,0.1

Type RM Length L Ch R = 1,1049,210,210,210
BEGIN DESCRIPTION:
UNT 1073 IN LATR 2.0
END DESCRIPTION:
XS GIS Cut Line= 4
      2986723.71     10085682.60      2986918.13     10086022.84
      2987355.63     10086328.39      2988055.29     10086335.32
#Sta/Elev= 30
  4396.7  951.95  4512.3  940.17  4577.1  930.68  4598.7  924.29  4636.1  903.34
  4657.7  893.78  4673.5  890.04  4709.0  874.06  4738.3  867.29  4773.4  863.10
  4817.9  857.01  4879.7  855.12  4954.8  856.79  4984.1  849.90  4993.7  845.74
  4996.5  845.24  4999.7  845.74  5011.5  847.05  5041.2  859.19  5097.9  863.74
  5148.5  877.39  5234.8  889.03  5306.4  894.32  5358.3  902.66  5575.1  953.82
  5657.3  958.97  5735.1  962.34  5790.1  968.90  5935.1  988.71  6021.9  991.61
#Mann=7,-1,0
  4396.7    0.16       0  4773.4     0.1       0  4879.7    0.16       0
  4993.7    0.07       0  4999.7    0.16       0  5657.3     0.1       0
  5790.1    0.16       0
Bank Sta=4993.7,4999.7
Exp/Cntr=0.3,0.1

Type RM Length L Ch R = 1,839,335,335,335
BEGIN DESCRIPTION:
Mapping XS 3c884cd3
END DESCRIPTION:
XS GIS Cut Line= 4
      2986684.35     10085723.20      2986805.87     10086084.29
      2987021.15     10086410.68      2987763.84     10086476.62
#Sta/Elev= 30
  4409.8  949.58  4579.2  930.97  4589.7  928.46  4595.1  922.68  4600.3  922.48
  4626.6  907.91  4631.9  902.30  4668.1  889.17  4695.2  873.98  4726.9  864.16
  4778.8  855.74  4840.2  852.79  4899.7  851.86  4999.1  844.03  5001.8  843.53
  5005.1  844.03  5044.2  856.21  5080.3  860.73  5110.5  859.22  5131.5  862.40
  5167.6  855.72  5229.3  873.40  5540.5  900.83  5613.9  911.97  5661.0  924.88
  5720.7  934.94  5837.4  952.02  5842.5  949.31  5883.1  953.36  5927.4  954.20
#Mann=6,-1,0
  4409.8    0.16       0  4668.1     0.1       0  4840.2    0.16       0
  4999.1    0.07       0  5005.1    0.16       0  5883.1     0.1       0
Bank Sta=4999.1,5005.1
Exp/Cntr=0.3,0.1

Type RM Length L Ch R = 1,504,199,199,199
BEGIN DESCRIPTION:
Mapping XS d63b2cae
END DESCRIPTION:
XS GIS Cut Line= 4
      2986660.04     10085806.50      2986587.12     10086327.35
      2986812.82     10086535.68      2987374.39     10086941.26
#Sta/Elev= 30
  4424.3  943.78  4540.7  931.37  4545.8  932.32  4581.2  921.91  4603.3  914.19
  4612.1  908.31  4617.2  909.84  4623.5  905.15  4633.6  901.44  4663.8  897.43
  4683.5  886.94  4688.6  890.01  4694.1  883.60  4734.5  869.12  4760.0  864.90
  4934.7  853.11  4937.2  852.91  4962.8  849.63  4983.9  842.48  4995.1  840.77
  4997.8  840.27  5001.1  840.77  5069.0  843.51  5118.3  852.84  5224.3  861.40
  5482.5  873.78  5613.1  881.74  5897.1  909.72  5932.7  921.82  5950.1  925.68
#Mann=9,-1,0
  4424.3    0.16       0  4581.2     0.1       0  4934.7    0.05       0
  4937.2     0.1       0  4962.8    0.05       0  4995.1   0.035       0
  5001.1    0.05       0  5482.5    0.16       0  5613.1     0.1       0
Bank Sta=4995.1,5001.1
Exp/Cntr=0.3,0.1

Type RM Length L Ch R = 1,305,244,244,244
BEGIN DESCRIPTION:
Mapping XS 67821337
END DESCRIPTION:
XS GIS Cut Line= 4
      2986622.74     10085821.25      2986457.80     10086463.65
      2986564.13     10086600.37      2987349.75     10086945.43
#Sta/Elev= 30
  4297.8  942.82  4417.3  933.17  4453.1  923.50  4458.1  924.21  4493.6  906.28
  4498.8  907.67  4534.4  894.28  4539.6  896.76  4548.2  895.70  4575.2  882.78
  4578.6  884.29  4589.4  883.43  4615.9  871.88  4641.1  866.69  4764.3  855.45
  4888.9  848.83  4936.8  842.40  4975.2  840.50  4994.8  835.72  4997.6  835.22
  5000.8  835.72  5089.2  848.45  5179.6  853.48  5280.3  857.77  5614.1  875.15
  5615.5  875.25  5730.6  884.43  5914.4  903.62  5946.3  909.28  5992.3  923.46
#Mann=10,-1,0
  4297.8    0.16       0  4453.1     0.1       0  4578.6    0.05       0
  4764.3     0.1       0  4994.8    0.07       0  5000.8     0.1       0
  5179.6    0.05       0  5280.3     0.1       0  5614.1    0.05       0
  5615.5     0.1       0
Bank Sta=4994.8,5000.8
Exp/Cntr=0.3,0.1

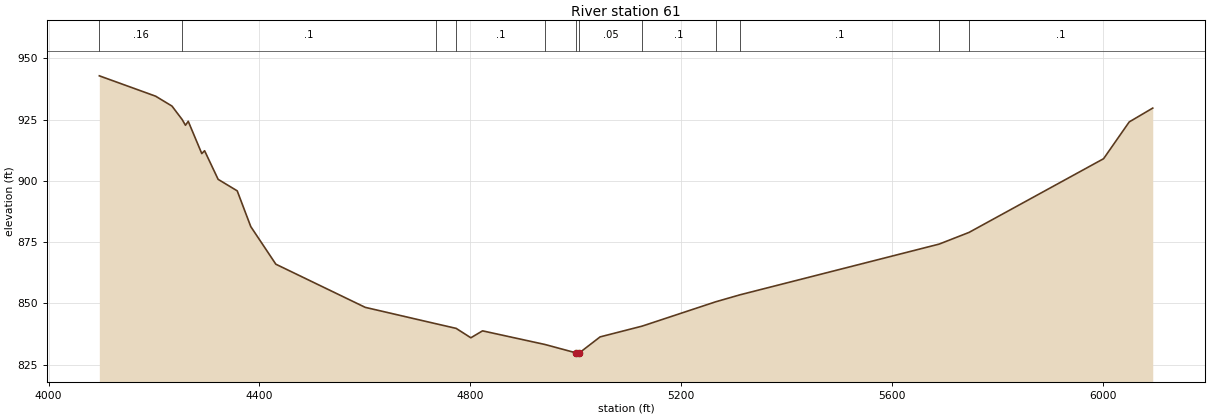
Type RM Length L Ch R = 1,61,0,0,0
BEGIN DESCRIPTION:
UNT 1073 IN LATR 1.0
END DESCRIPTION:
XS GIS Cut Line= 4
      2986598.85     10085827.81      2986310.23     10086648.11
      2986381.84     10086719.72      2987378.98     10086969.01
#Sta/Elev= 30
  4096.2  942.89  4203.0  934.58  4234.0  930.55  4253.4  925.04  4259.6  922.71
  4264.9  924.33  4290.6  911.15  4295.9  912.32  4321.6  900.64  4357.8  895.95
  4383.5  881.37  4431.1  866.01  4600.7  848.40  4734.3  841.74  4773.2  839.82
  4801.1  835.98  4823.3  838.81  4941.8  833.24  5000.9  829.81  5003.6  829.31
  5006.9  829.81  5046.3  836.34  5126.4  840.76  5265.7  850.67  5312.0  853.53
  5689.7  874.22  5746.3  878.98  6001.6  909.06  6050.3  924.08  6094.9  929.72
#Mann=12,-1,0
  4096.2    0.16       0  4253.4     0.1       0  4734.3    0.05       0
  4773.2     0.1       0  4941.8    0.05       0  5000.9   0.035       0
  5006.9    0.05       0  5126.4     0.1       0  5265.7    0.05       0
  5312.0     0.1       0  5689.7    0.05       0  5746.3     0.1       0
Bank Sta=5000.9,5006.9
Exp/Cntr=0.3,0.1

Chan Stop Cuts=-1