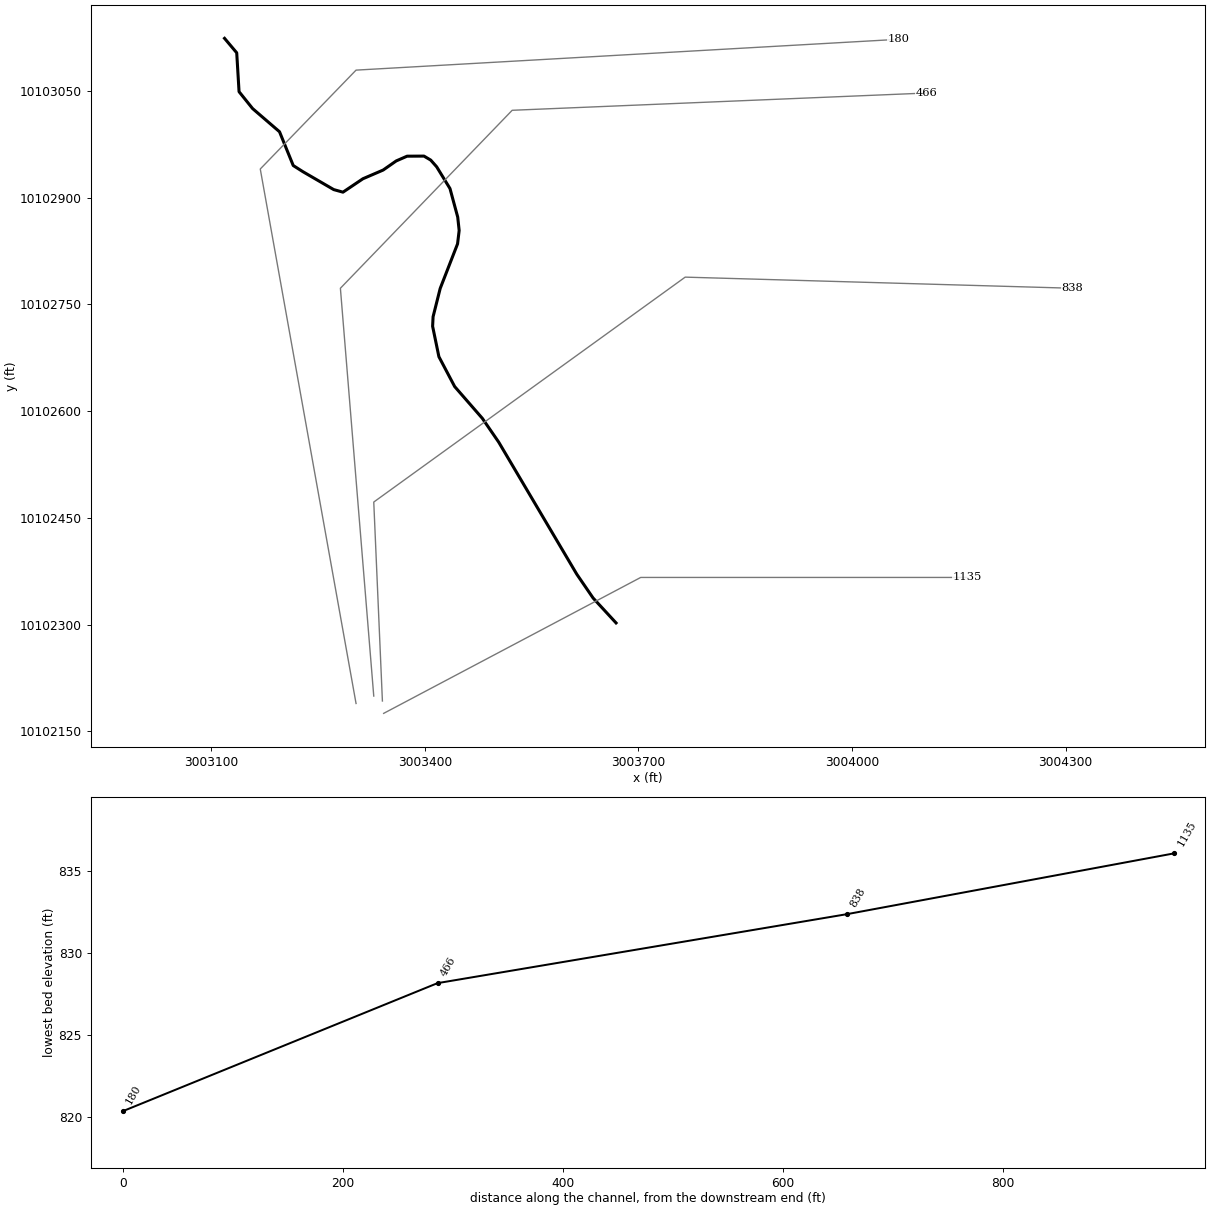
--- UNT 1074 IN LATR.prj (project) ---

Proj Title=UNT 1074 IN LATR Base Level Engineering
Current Plan=p01
Default Exp/Contr=0.3,0.1
English Units
Geom File=g01
Flow File=f01
Plan File=p01
Y Axis Title=Elevation
X Axis Title(PF)=Main Channel Distance
X Axis Title(XS)=Station
BEGIN DESCRIPTION:
UNT 1074 IN LATR
END DESCRIPTION:
DSS Export Rating Curves= 0
DSS Export Rating Curve Sorted= 0
DSS Export Volume Flow Curves= 0
DXF OffsetX= 0
DXF OffsetY= 0
DXF ScaleX= 1
DXF ScaleY= 10

--- UNT 1074 IN LATR.p01 (plan) ---

Plan Title=Multiple Run
Short Identifier=Multiple
Geom File=g01
Flow File=f01
Subcritical Flow
K Sum by GR= 0
Std Step Tol= 0.01
Critical Tol= 0.01
Num of Std Step Trials= 20
Max Error Tol= 0.3
Flow Tol Ratio= 0.001
Split Flow NTrial= 30
Split Flow Tol= 0.02
Split Flow Ratio= 0.02
Log Output Level= 0
Friction Slope Method= 1
Unsteady Friction Slope Method= 2
Unsteady Bridges Friction Slope Method= 1
Parabolic Critical Depth
Global Vel Dist=  1 , 1 , 1
Global Log Level= 0
CheckData=True
Encroach Param= -1, 0, 0, 0
BEGIN DESCRIPTION:
Multiple Run
END DESCRIPTION:

--- UNT 1074 IN LATR.f01 (steady flow) ---

Flow Title=Multiple
Program Version=4.10
Number of Profiles= 7
Profile Names=10-year,25-year,50-year,1pct_min,100-year,1pct_plu,500-year
River Rch & RM=UNT 1074 IN LATR,Reach-1         ,1135
     641     917    1155    1066    1442    1950    2256
Boundary for River Rch & Prof#=UNT 1074 IN LATR,Reach-1         , 1
Up Type= 0
Dn Type= 3
Dn Slope=0.027
Boundary for River Rch & Prof#=UNT 1074 IN LATR,Reach-1         , 2
Up Type= 0
Dn Type= 3
Dn Slope=0.027
Boundary for River Rch & Prof#=UNT 1074 IN LATR,Reach-1         , 3
Up Type= 0
Dn Type= 3
Dn Slope=0.027
Boundary for River Rch & Prof#=UNT 1074 IN LATR,Reach-1         , 4
Up Type= 0
Dn Type= 3
Dn Slope=0.027
Boundary for River Rch & Prof#=UNT 1074 IN LATR,Reach-1         , 5
Up Type= 0
Dn Type= 3
Dn Slope=0.027
Boundary for River Rch & Prof#=UNT 1074 IN LATR,Reach-1         , 6
Up Type= 0
Dn Type= 3
Dn Slope=0.027
Boundary for River Rch & Prof#=UNT 1074 IN LATR,Reach-1         , 7
Up Type= 0
Dn Type= 3
Dn Slope=0.027
DSS Import GetInterval= 0
DSS Import GetPeak= 0
DSS Import FillOption= 0

--- UNT 1074 IN LATR.g01 (geometry) ---

Geom Title=Existing Conditions
Program Version=4.10

River Reach=UNT 1074 IN LATR,Reach-1
Reach XY= 30
      3003668.47     10102302.51       3003636.2     10102337.51
      3003613.26       10102371.      3003503.63     10102556.45
      3003480.62     10102589.91      3003441.74     10102634.57
      3003419.61     10102676.49      3003410.78     10102719.21
      3003411.44     10102732.65      3003421.43     10102772.38
      3003445.82     10102835.02      3003448.07     10102853.78
      3003446.05     10102872.61      3003435.19     10102912.69
      3003416.43     10102943.32      3003408.14     10102952.66
      3003398.67      10102958.3      3003374.89     10102958.17
      3003359.59     10102951.48      3003341.29      10102938.7
      3003312.87     10102926.47      3003284.86     10102907.63
      3003271.88     10102911.23      3003228.63     10102936.36
      3003214.98     10102945.04      3003195.71      10102992.5
      3003157.91     10103025.05      3003138.87     10103048.77
      3003135.59     10103103.41      3003118.47     10103123.73

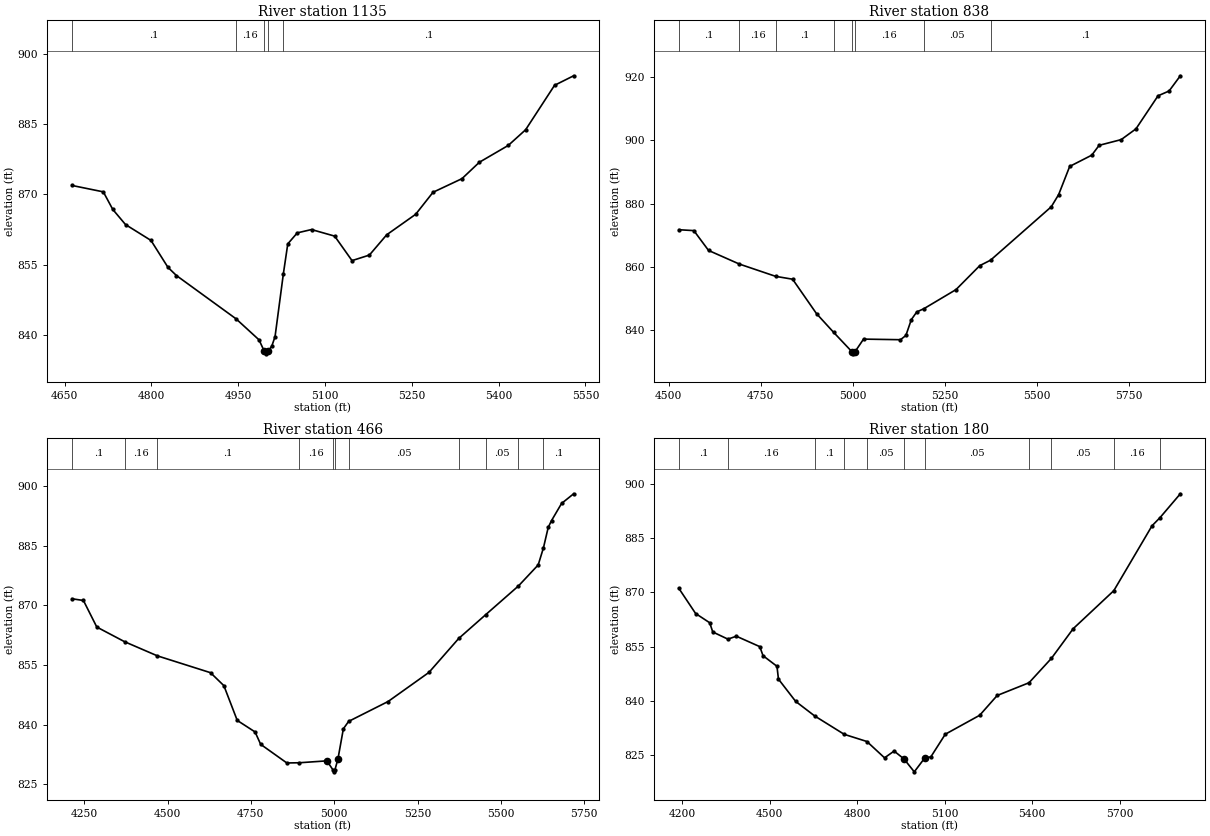
Type RM Length L Ch R = 1 ,1135    ,297,297,297
BEGIN DESCRIPTION:
UNT 1074 IN LATR 10.0
END DESCRIPTION:
XS GIS Cut Line= 3
      3003342.02     10102175.44       3003703.1      10102366.4
      3004161.43      10102366.4
#Sta/Elev= 30
  4662.9  871.91  4716.9  870.55  4733.3   866.8  4755.3  863.58  4799.3   860.2
  4828.6  854.47  4843.3  852.72  4946.3   843.5    4986  839.02  4995.3  836.54
    4998  836.04  5001.3  836.54    5008  837.66  5013.7  839.71  5028.1  853.12
  5035.7  859.47  5052.1  861.81  5076.7  862.52  5116.7  861.12  5146.7   855.9
  5176.7  857.08  5206.7  861.41  5256.7  865.77  5286.7  870.46  5336.7  873.36
  5366.7  876.85  5416.7  880.44  5446.7  883.78  5496.7  893.25  5529.7  895.28
#Mann= 5 ,-1 , 0
  4662.9      .1       0  4946.3     .16       0  4995.3     .07       0
  5001.3     .16       0  5028.1      .1       0
Bank Sta=4995.3,5001.3
XS Rating Curve= 0 ,0
Exp/Cntr=0.3,0.1

Type RM Length L Ch R = 1 ,838     ,372,372,372
BEGIN DESCRIPTION:
Mapping XS a71214bb
END DESCRIPTION:
XS GIS Cut Line= 4
      3003340.25     10102192.81       3003328.1      10102472.3
       3003765.6     10102788.27      3004309.05     10102772.65
#Sta/Elev= 30
  4527.6   871.7  4568.6  871.42  4608.6  865.13  4692.6   860.8  4790.9  856.92
    4837  856.01    4902  845.09  4948.6  839.15  4999.6  832.85  5002.4  832.35
  5005.6  832.85  5029.8  837.02  5130.2  836.83  5144.9  838.18  5159.6  843.19
  5174.4  845.63  5194.5  846.71  5281.1  852.72  5345.7  860.32  5374.9  862.04
    5540  878.98    5560  882.84    5590  891.77    5650  895.34    5670  898.46
    5730  900.27  5770.1  903.68  5830.1  914.16  5860.1  915.68  5890.7  920.51
#Mann= 8 ,-1 , 0
  4527.6      .1       0  4692.6     .16       0  4790.9      .1       0
  4948.6     .16       0  4999.6     .07       0  5005.6     .16       0
  5194.5     .05       0  5374.9      .1       0
Bank Sta=4999.6,5005.6
XS Rating Curve= 0 ,0
Exp/Cntr=0.3,0.1

Type RM Length L Ch R = 1 ,466     ,286,286,286
BEGIN DESCRIPTION:
Mapping XS 175d83b3
END DESCRIPTION:
XS GIS Cut Line= 4
       3003328.1     10102199.76      3003281.23     10102772.65
      3003522.55     10103022.65      3004104.67      10103046.9
#Sta/Elev= 30
  4213.5  871.64  4247.6  871.21  4287.7  864.54  4371.2  860.85  4469.5   857.3
  4628.9  853.07    4669  849.81  4709.1  841.08  4762.6  838.18  4779.4  835.07
  4857.9  830.39  4895.1  830.44  4978.1  830.92  4996.2  828.66  4998.9  828.16
  5002.2  828.66 5011.22  831.39  5027.5  838.98  5043.4  840.84  5161.7  845.83
  5284.4  853.15  5373.6  861.67  5454.2  867.62  5552.8  874.86  5612.1  880.15
  5627.9  884.47  5642.1  889.57  5652.1  891.29  5682.2  895.59  5718.4  898.02
#Mann= 11 ,-1 , 0
  4213.5      .1       0  4371.2     .16       0  4469.5      .1       0
  4895.1     .16       0  4996.2     .07       0  5002.2     .16       0
  5043.4     .05       0  5373.6      .1       0  5454.2     .05       0
  5552.8     .16       0  5627.9      .1       0
Bank Sta=4978.1,5011.22
XS Rating Curve= 0 ,0
Exp/Cntr=0.3,0.1

Type RM Length L Ch R = 1 ,180     ,0,0,0
BEGIN DESCRIPTION:
UNT 1074 IN LATR 1.0
END DESCRIPTION:
XS GIS Cut Line= 4
      3003303.22     10102189.33      3003168.67     10102940.18
      3003303.22     10103079.07       3004065.3     10103122.37
#Sta/Elev= 30
  4188.7  871.16  4246.5  864.17  4294.8  861.61  4305.3  859.06  4357.2  857.08
  4386.2  857.89  4466.6     855  4477.6   852.5  4525.4  849.57  4530.5  846.02
  4589.4  839.87  4654.6  835.84    4756  830.75  4833.7  828.77  4894.2  824.25
    4927  826.13  4960.9  823.94  4996.1  820.38  5031.6  824.17    5053  824.53
  5102.4  830.78  5220.3  836.02  5280.4   841.5  5389.5  845.02  5466.3  851.77
  5540.8  859.96  5680.2  870.49  5811.2  888.43  5838.7   890.7  5908.2  897.28
#Mann= 11 ,-1 , 0
  4188.7      .1       0  4357.2     .16       0  4654.6      .1       0
    4756     .05       0  4833.7     .05       0  4960.9     .03       0
  5031.6     .05       0  5389.5     .16       0  5466.3     .05       0
  5680.2     .16       0  5838.7      .1       0
Bank Sta=4960.9,5031.6
XS Rating Curve= 0 ,0
Exp/Cntr=0.3,0.1

Chan Stop Cuts=-1
Use User Specified Reach Order=0
Composite Channel Slope=5