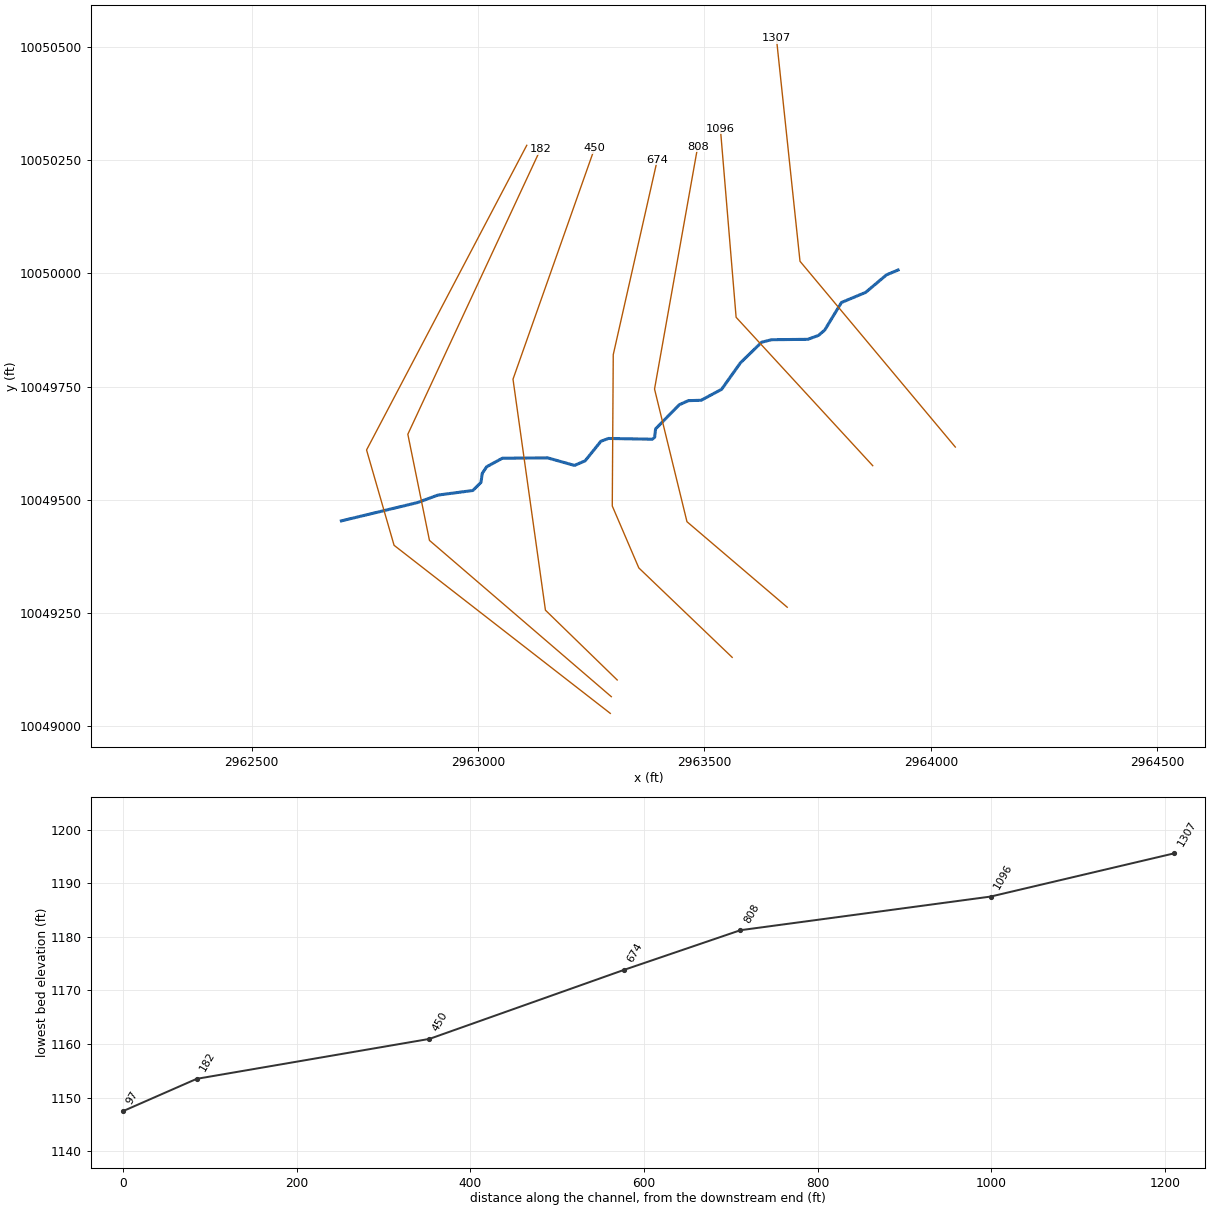
--- UNT 1076 IN LATR.prj (project) ---

Proj Title=UNT 1076 IN LATR Base Level Engineering
Current Plan=p01
Default Exp/Contr=0.3,0.1
English Units
Geom File=g01
Flow File=f01
Plan File=p01
Y Axis Title=Elevation
X Axis Title(PF)=Main Channel Distance
X Axis Title(XS)=Station
BEGIN DESCRIPTION:
UNT 1076 IN LATR
END DESCRIPTION:
DSS File=dss
DSS Export Rating Curves= 0
DSS Export Rating Curve Sorted= 0
DSS Export Volume Flow Curves= 0
DXF OffsetX= 0
DXF OffsetY= 0
DXF ScaleX= 1
DXF ScaleY= 10

--- UNT 1076 IN LATR.p01 (plan) ---

Plan Title=Multiple Run
Short Identifier=Multiple
Geom File=g01
Flow File=f01
Subcritical Flow
K Sum by GR= 0
Std Step Tol= 0.01
Critical Tol= 0.01
Num of Std Step Trials= 20
Max Error Tol= 0.3
Flow Tol Ratio= 0.001
Split Flow NTrial= 30
Split Flow Tol= 0.02
Split Flow Ratio= 0.02
Log Output Level= 0
Friction Slope Method= 1
Unsteady Friction Slope Method= 2
Unsteady Bridges Friction Slope Method= 1
Parabolic Critical Depth
Global Vel Dist=  1 , 1 , 1
Global Log Level= 0
CheckData=True
Encroach Param= -1, 0, 0, 0
BEGIN DESCRIPTION:
Multiple Run
END DESCRIPTION:

--- UNT 1076 IN LATR.f01 (steady flow) ---

Flow Title=Multiple
Program Version=4.10
Number of Profiles= 7
Profile Names=10-year,25-year,50-year,1pct_min,100-year,1pct_plu,500-year
River Rch & RM=UNT 1076 IN LATR,Reach-1         ,1307
     260     348     419     373     504     681     726
Boundary for River Rch & Prof#=UNT 1076 IN LATR,Reach-1         , 1
Up Type= 0
Dn Type= 3
Dn Slope=0.074
Boundary for River Rch & Prof#=UNT 1076 IN LATR,Reach-1         , 2
Up Type= 0
Dn Type= 3
Dn Slope=0.074
Boundary for River Rch & Prof#=UNT 1076 IN LATR,Reach-1         , 3
Up Type= 0
Dn Type= 3
Dn Slope=0.074
Boundary for River Rch & Prof#=UNT 1076 IN LATR,Reach-1         , 4
Up Type= 0
Dn Type= 3
Dn Slope=0.074
Boundary for River Rch & Prof#=UNT 1076 IN LATR,Reach-1         , 5
Up Type= 0
Dn Type= 3
Dn Slope=0.074
Boundary for River Rch & Prof#=UNT 1076 IN LATR,Reach-1         , 6
Up Type= 0
Dn Type= 3
Dn Slope=0.074
Boundary for River Rch & Prof#=UNT 1076 IN LATR,Reach-1         , 7
Up Type= 0
Dn Type= 3
Dn Slope=0.074
DSS Import GetInterval= 0
DSS Import GetPeak= 0
DSS Import FillOption= 0

--- UNT 1076 IN LATR.g01 (geometry) ---

Geom Title=Existing Conditions
Program Version=4.10

River Reach=UNT 1076 IN LATR,Reach-1
Reach XY= 30
      2963927.59      10050007.6        2963902.     10049996.93
      2963855.99     10049958.19      2963802.57      10049935.9
      2963765.71     10049875.14      2963751.86      10049863.2
      2963728.27     10049854.57      2963648.34     10049853.73
       2963626.2     10049848.13      2963579.24     10049802.31
      2963538.02     10049744.24      2963492.75     10049719.99
      2963464.66      10049719.2      2963444.54     10049710.16
      2963392.19     10049656.79       2963390.1     10049638.25
      2963384.94     10049634.02      2963288.04     10049635.69
      2963271.45     10049629.49      2963236.61     10049586.33
      2963213.13     10049576.13      2963153.82     10049592.83
      2963053.88     10049592.04      2963019.26     10049573.25
      2963009.54     10049558.81       2963006.6     10049538.55
      2962988.66     10049520.79      2962911.95     10049510.73
      2962866.06     10049494.02      2962698.47     10049453.73

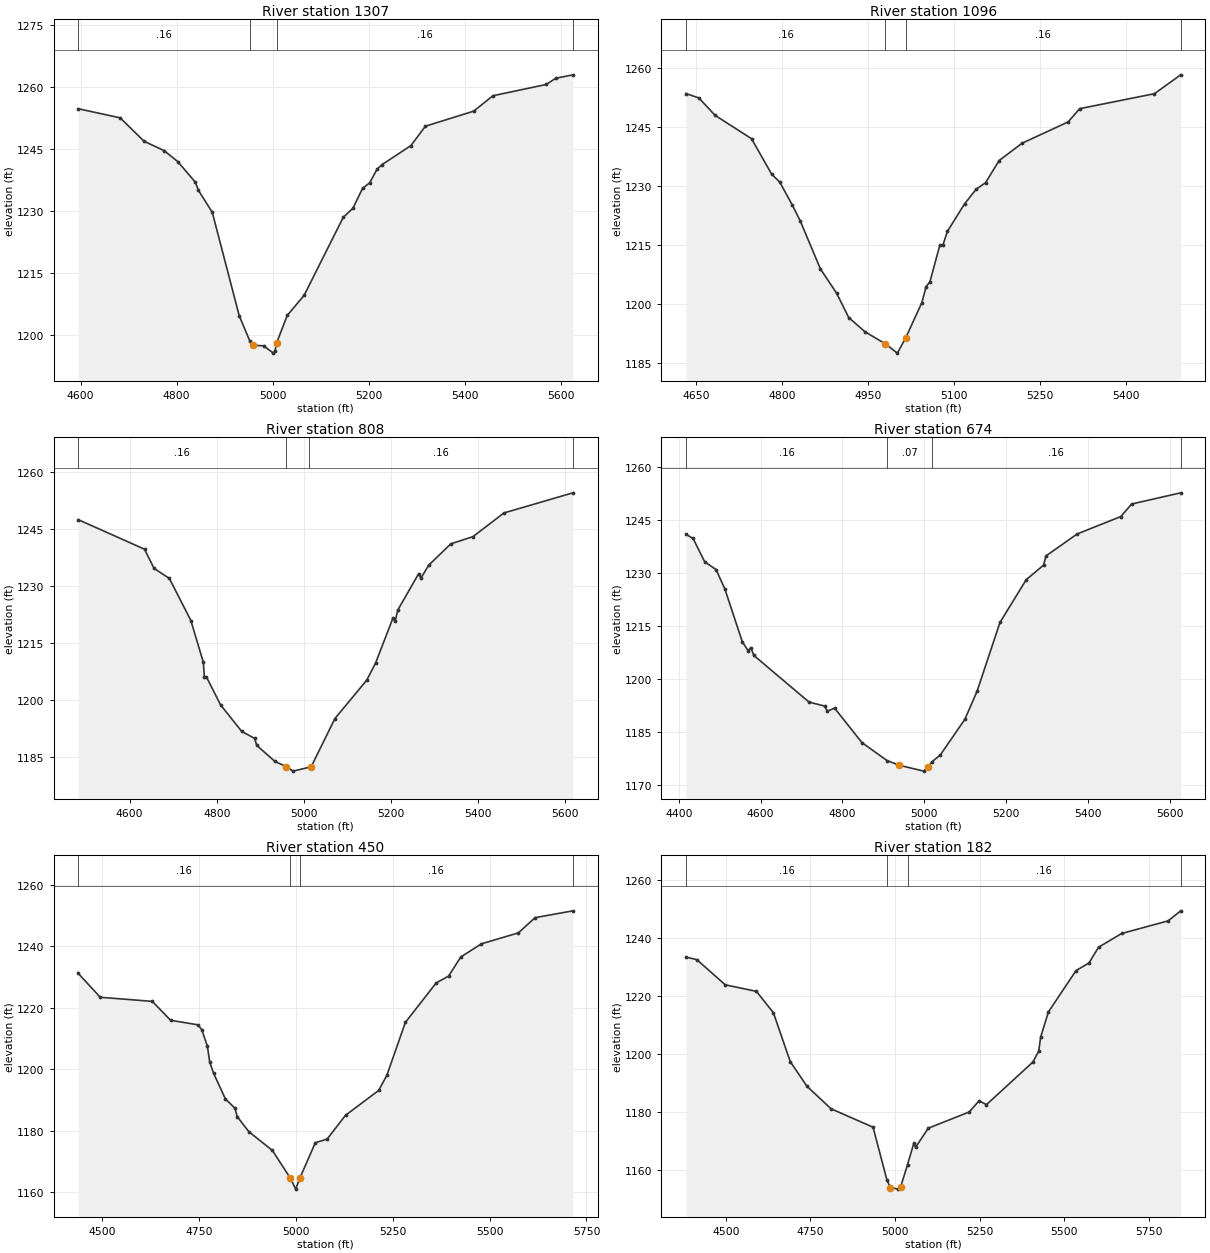
Type RM Length L Ch R = 1 ,1307    ,211,211,211
BEGIN DESCRIPTION:
UNT 1076 IN LATR 3.0
END DESCRIPTION:
XS GIS Cut Line= 3
      2964053.95     10049616.74      2963711.04     10050026.93
        2963659.     10050519.15
#Sta/Elev= 30
  4595.3 1254.74  4682.6 1252.53  4732.3 1246.86    4774 1244.59  4802.6 1241.92
    4839 1236.94  4845.5 1234.95  4874.2 1229.67  4930.3 1204.63  4952.2 1198.53
  4958.8 1197.44  4980.9 1197.33  5001.4 1195.55  5004.7 1196.05  5008.5 1198.12
  5030.3 1204.68  5065.5 1209.56  5146.8 1228.43  5166.9 1230.62  5187.1 1235.45
  5202.1 1236.83  5217.2 1240.09  5227.3 1241.18  5287.6  1245.8  5317.8  1250.5
  5418.3 1254.15  5458.6 1257.89  5569.2 1260.61  5589.3 1262.12  5624.9 1262.95
#Mann= 4 ,-1 , 0
  4595.3     .16       0  4952.2     .07       0  5008.5     .16       0
  5624.9      .1       0
Bank Sta=4958.8,5008.5
XS Rating Curve= 0 ,0
Exp/Cntr=0.3,0.1

Type RM Length L Ch R = 1 ,1096    ,288,288,288
BEGIN DESCRIPTION:
Mapping XS 36a81be0
END DESCRIPTION:
XS GIS Cut Line= 3
       2963871.6     10049575.57      2963569.98     10049903.23
       2963535.3     10050319.34
#Sta/Elev= 30
  4632.7 1253.53    4655 1252.42  4683.4 1247.99  4746.9 1242.05  4782.1 1233.02
  4796.2    1231  4817.8 1225.25    4832 1221.11  4867.1 1208.93  4895.5 1202.71
  4916.5 1196.55  4944.8 1192.94  4980.6 1189.85  5001.3  1187.5  5015.7 1191.33
  5044.1 1200.36  5051.4 1204.37  5058.2 1205.69  5075.5 1215.01  5080.8 1215.01
  5088.6 1218.47  5118.7  1225.5  5138.8 1229.19  5155.2 1230.86  5178.9  1236.5
    5219 1240.91  5299.3 1246.32  5319.4 1249.69  5449.8  1253.5  5495.6  1258.3
#Mann= 4 ,-1 , 0
  4632.7     .16       0  4980.6     .07       0  5015.7     .16       0
  5495.6      .1       0
Bank Sta=4980.6,5015.7
XS Rating Curve= 0 ,0
Exp/Cntr=0.3,0.1

Type RM Length L Ch R = 1 ,808     ,134,134,134
BEGIN DESCRIPTION:
Mapping XS f9cce75e
END DESCRIPTION:
XS GIS Cut Line= 4
       2963682.8     10049263.07      2963461.47     10049451.85
      2963389.86     10049744.81      2963485.16      10050279.8
#Sta/Elev= 30
    4482 1247.49  4634.1 1239.71  4656.1 1234.65  4691.2    1232  4740.6 1220.91
  4769.2  1209.9  4771.6 1206.05  4776.4 1206.05  4808.7  1198.7  4857.2 1191.71
  4886.9 1189.86    4892    1188  4933.7 1183.78  4960.1 1182.42  4975.1 1181.23
  5011.6 1182.22    5017 1182.42  5071.4 1195.09  5144.5 1205.21  5164.8 1209.72
  5204.7 1221.58  5209.8 1220.74  5215.6 1223.65  5263.7 1233.25  5268.8 1232.05
  5286.7 1235.48  5337.5 1241.12  5388.3 1243.01  5459.4 1249.25  5617.9 1254.56
#Mann= 4 ,-1 , 0
    4482     .16       0  4960.1     .07       0  5011.6     .16       0
  5617.9      .1       0
Bank Sta=4960.1,5017
XS Rating Curve= 0 ,0
Exp/Cntr=0.3,0.1

Type RM Length L Ch R = 1 ,674     ,224,224,224
BEGIN DESCRIPTION:
Mapping XS a8f46fcb
END DESCRIPTION:
XS GIS Cut Line= 5
      2963561.29     10049152.38      2963355.14     10049349.85
      2963296.54     10049486.57      2963298.71     10049820.77
      2963395.93     10050250.69
#Sta/Elev= 30
  4417.7 1240.85  4434.9 1239.68  4463.1 1233.12  4491.2 1230.86  4512.6 1225.38
  4555.1 1210.48  4569.2 1207.94  4576.1  1208.8  4583.4 1206.58  4718.3 1193.38
  4757.3 1192.22  4762.7  1190.8  4780.8 1191.66  4847.7  1181.9  4909.1 1176.81
  4939.1 1175.49  4998.8 1173.83  5009.1 1174.91  5019.1 1176.49  5039.1 1178.39
  5099.1 1188.46  5129.1 1196.42  5185.1 1215.92  5249.3 1228.01  5291.7 1232.14
  5297.6 1234.74  5373.7 1240.95  5480.5 1245.89    5507 1249.43  5626.9  1252.6
#Mann= 4 ,-1 , 0
  4417.7     .16       0  4909.1     .07       0  5019.1     .16       0
  5626.9      .1       0
Bank Sta=4939.1,5009.1
XS Rating Curve= 0 ,0
Exp/Cntr=0.3,0.1

Type RM Length L Ch R = 1 ,450     ,268,268,268
BEGIN DESCRIPTION:
Mapping XS 9fc31306
END DESCRIPTION:
XS GIS Cut Line= 4
      2963307.42     10049102.43      2963148.97     10049256.53
      2963077.36     10049766.52      2963257.49     10050276.53
#Sta/Elev= 30
    4438 1231.22  4494.7 1223.44  4629.2  1222.1  4676.4 1215.95  4747.1 1214.46
  4757.2  1212.8  4771.4 1207.46  4777.4 1202.28  4787.5 1198.66  4817.8 1190.34
  4842.7 1187.29  4848.1 1184.61  4878.4 1179.66  4938.9  1173.6  4985.3 1164.58
  4999.3 1160.96  5009.6 1164.44    5050 1176.08  5080.3 1177.24  5127.9 1185.01
  5213.5  1193.1  5234.7 1198.05  5282.4 1215.25    5362 1228.12  5393.8 1230.32
  5425.6 1236.57  5478.6 1240.84  5574.1 1244.41  5617.3 1249.37  5714.9 1251.59
#Mann= 4 ,-1 , 0
    4438     .16       0  4985.3     .07       0  5009.6     .16       0
  5714.9     .05       0
Bank Sta=4985.3,5009.6
XS Rating Curve= 0 ,0
Exp/Cntr=0.3,0.1

Type RM Length L Ch R = 1 ,182     ,85,85,85
BEGIN DESCRIPTION:
Mapping XS 6fd69115
END DESCRIPTION:
XS GIS Cut Line= 4
      2963294.37     10049065.56       2962892.9     10049410.61
      2962845.15     10049644.99      2963138.14     10050274.37
#Sta/Elev= 30
  4382.1  1233.4  4413.7 1232.55  4498.2 1223.85  4590.3 1221.61  4640.4 1214.25
  4690.2 1197.44  4739.6 1188.94  4810.9 1181.18  4935.1 1174.83  4975.9 1156.79
  4986.1 1154.06    5010 1153.51  5016.7 1154.29  5037.1 1161.97  5055.7  1169.3
  5060.8 1167.89  5098.4 1174.49  5219.4 1180.07  5248.6 1183.92  5270.6 1182.61
  5407.9 1197.28    5425 1201.01  5430.8 1205.89  5453.7 1214.52  5535.3 1228.75
  5573.6 1231.38    5602 1236.81  5670.6 1241.55  5807.9 1245.89  5844.9 1249.34
#Mann= 4 ,-1 , 0
  4382.1     .16       0  4975.9     .07       0  5037.1     .16       0
  5844.9      .1       0
Bank Sta=4986.1,5016.7
XS Rating Curve= 0 ,0
Exp/Cntr=0.3,0.1

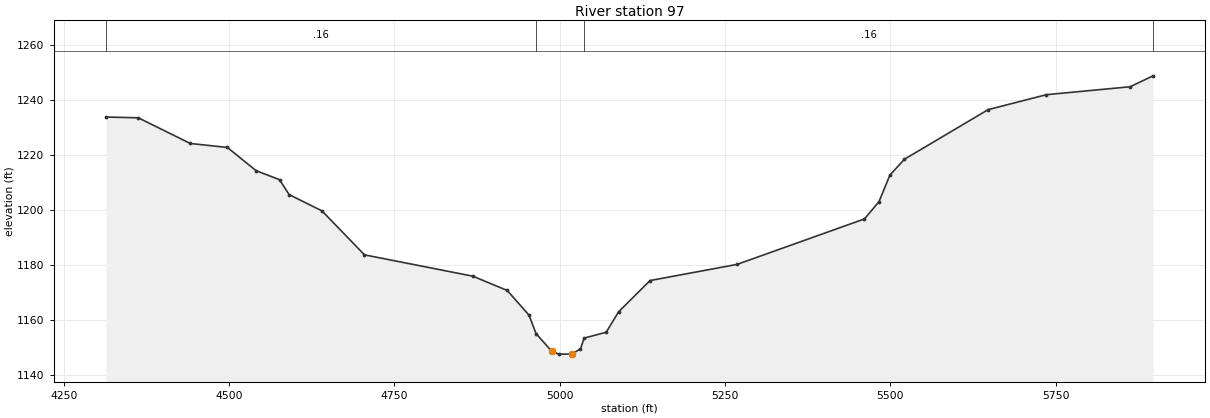
Type RM Length L Ch R = 1 ,97      ,0,0,0
BEGIN DESCRIPTION:
UNT 1076 IN LATR 1.0
END DESCRIPTION:
XS GIS Cut Line= 4
      2963292.18     10049028.68      2962814.77     10049399.76
      2962754.01     10049610.27      2963107.72     10050282.98
#Sta/Elev= 30
  4313.5 1233.83  4362.5 1233.54  4441.2 1224.19  4497.3 1222.74  4540.8 1214.26
  4576.1 1211.01  4590.6 1205.58  4640.3 1199.64  4704.6 1183.63  4868.4 1175.86
  4920.5 1170.66  4953.5 1161.66    4964 1154.98 4987.91 1148.47 4998.57 1147.47
 5018.41 1147.51  5031.3  1149.4  5036.8  1153.3  5070.2 1155.44  5088.8 1162.84
  5136.5 1174.27  5268.1 1180.15  5460.8 1196.71  5482.8    1203  5499.2 1212.65
  5521.3 1218.46  5647.9 1236.52    5736 1241.96  5862.6 1244.85  5897.3 1248.83
#Mann= 4 ,-1 , 0
  4313.5     .16       0    4964     .07       0  5036.8     .16       0
  5897.3      .1       0
Bank Sta=4987.91,5018.41
XS Rating Curve= 0 ,0
Exp/Cntr=0.3,0.1

Chan Stop Cuts=-1
Use User Specified Reach Order=0
Composite Channel Slope=5