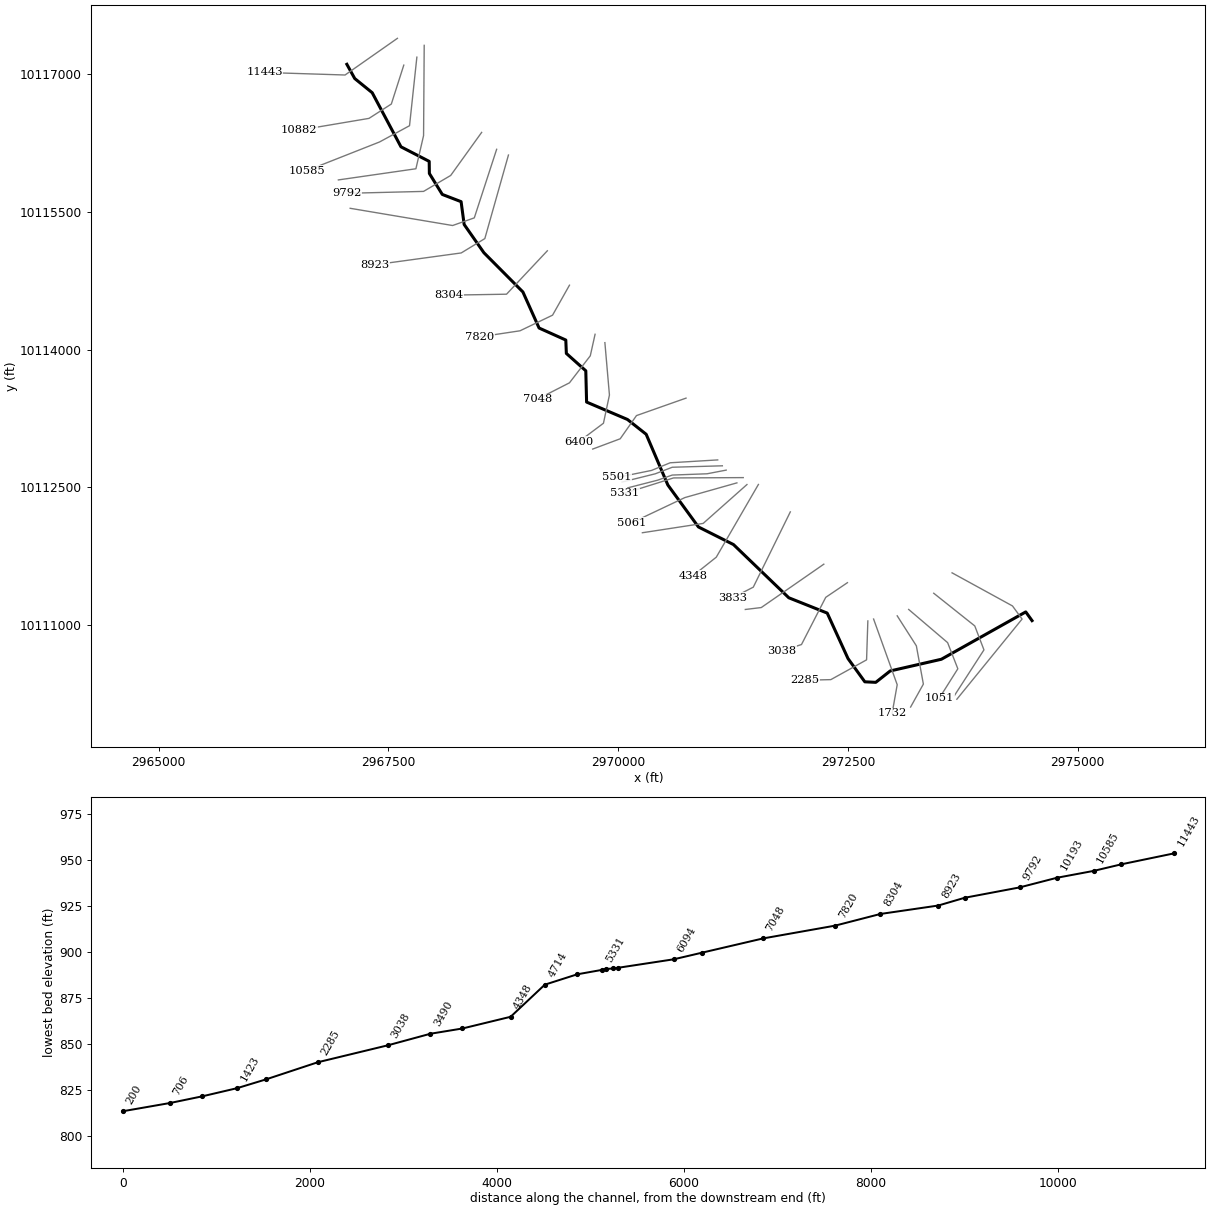
--- WALLACE BRANCH.prj (project) ---

Proj Title=WALLACE BRANCH Base Level Engineering
Current Plan=p01
Default Exp/Contr=0.3,0.1
English Units
Geom File=g01
Flow File=f01
Plan File=p01
Y Axis Title=Elevation
X Axis Title(PF)=Main Channel Distance
X Axis Title(XS)=Station
BEGIN DESCRIPTION:
WALLACE BRANCH
END DESCRIPTION:
DSS Export Rating Curves= 0
DSS Export Rating Curve Sorted= 0
DSS Export Volume Flow Curves= 0
DXF OffsetX= 0
DXF OffsetY= 0
DXF ScaleX= 1
DXF ScaleY= 10

--- WALLACE BRANCH.p01 (plan) ---

Plan Title=Multiple Run
Short Identifier=Multiple
Geom File=g01
Flow File=f01
Subcritical Flow
K Sum by GR= 0
Std Step Tol= 0.01
Critical Tol= 0.01
Num of Std Step Trials= 20
Max Error Tol= 0.3
Flow Tol Ratio= 0.001
Split Flow NTrial= 30
Split Flow Tol= 0.02
Split Flow Ratio= 0.02
Log Output Level= 0
Friction Slope Method= 1
Unsteady Friction Slope Method= 2
Unsteady Bridges Friction Slope Method= 1
Parabolic Critical Depth
Global Vel Dist=  1 , 1 , 1
Global Log Level= 0
CheckData=True
Encroach Param= -1, 0, 0, 0
BEGIN DESCRIPTION:
Multiple Run
END DESCRIPTION:

--- WALLACE BRANCH.f01 (steady flow) ---

Flow Title=Multiple
Program Version=4.10
Number of Profiles= 7
Profile Names=10-year,25-year,50-year,1pct_min,100-year,1pct_plu,500-year
River Rch & RM=WALLACE BRANCH,Reach-1         ,11443
    1339    2001    2594    2460    3327    4499    5496
River Rch & RM=WALLACE BRANCH,Reach-1         ,6094
    2416    3710    4897    4720    6384    8633   10898
River Rch & RM=WALLACE BRANCH,Reach-1         ,5501
    2416    3710    4897    4720    6384    8633   10898
Boundary for River Rch & Prof#=WALLACE BRANCH,Reach-1         , 1
Up Type= 0
Dn Type= 3
Dn Slope=0.005
Boundary for River Rch & Prof#=WALLACE BRANCH,Reach-1         , 2
Up Type= 0
Dn Type= 3
Dn Slope=0.005
Boundary for River Rch & Prof#=WALLACE BRANCH,Reach-1         , 3
Up Type= 0
Dn Type= 3
Dn Slope=0.005
Boundary for River Rch & Prof#=WALLACE BRANCH,Reach-1         , 4
Up Type= 0
Dn Type= 3
Dn Slope=0.005
Boundary for River Rch & Prof#=WALLACE BRANCH,Reach-1         , 5
Up Type= 0
Dn Type= 3
Dn Slope=0.005
Boundary for River Rch & Prof#=WALLACE BRANCH,Reach-1         , 6
Up Type= 0
Dn Type= 3
Dn Slope=0.005
Boundary for River Rch & Prof#=WALLACE BRANCH,Reach-1         , 7
Up Type= 0
Dn Type= 3
Dn Slope=0.005
DSS Import GetInterval= 0
DSS Import GetPeak= 0
DSS Import FillOption= 0

--- WALLACE BRANCH.g01 (geometry) ---

Geom Title=Existing Conditions
Program Version=4.10

River Reach=WALLACE BRANCH  ,Reach-1
Reach XY= 30
      2967047.63     10117105.74      2967133.21     10116950.83
      2967323.42     10116796.34      2967636.39     10116207.25
      2967943.63     10116048.63      2967945.44     10115916.92
      2968086.08     10115688.67      2968290.75     10115609.89
      2968324.06     10115361.26      2968538.94     10115053.82
      2968963.32     10114626.64      2969139.31     10114233.99
      2969430.05      10114103.3      2969436.11     10113957.45
      2969647.59     10113768.43      2969656.34     10113427.79
      2970100.98     10113238.37      2970304.71     10113077.09
      2970540.64     10112524.61       2970873.4      10112067.9
      2971254.78     10111876.28      2971856.67     10111296.86
      2972274.83     10111130.08      2972501.06     10110634.81
       2972683.8     10110381.84      2972802.99       10110376.
      2972960.01     10110499.99      2973516.93     10110627.44
      2974435.15     10111143.04      2974503.46     10111047.93

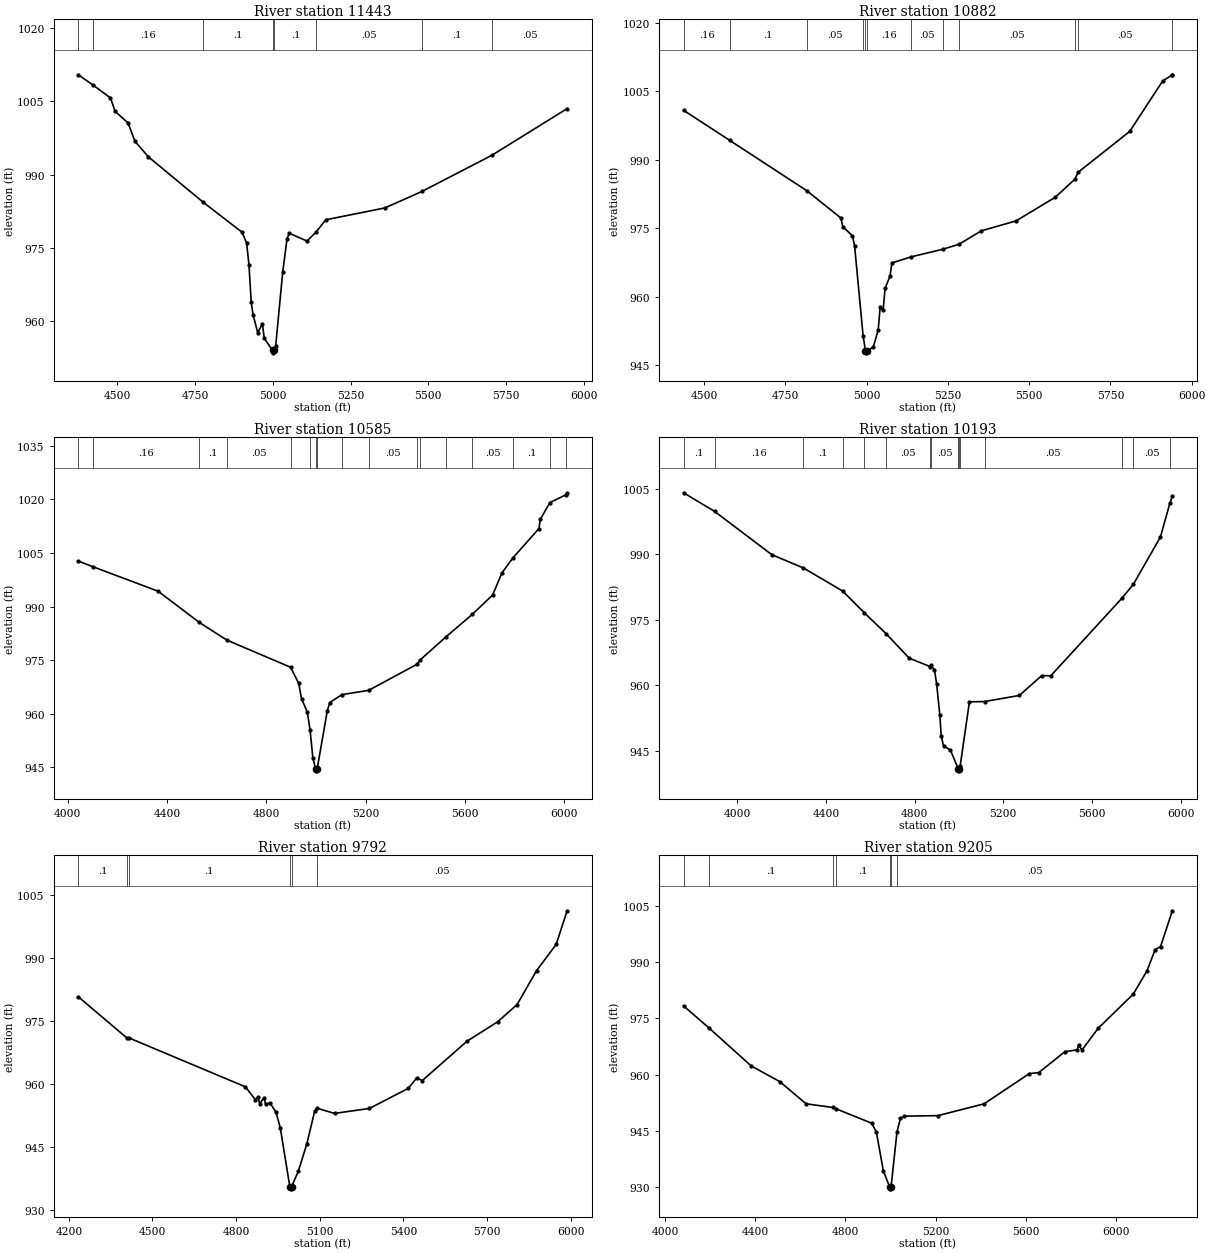
Type RM Length L Ch R = 1 ,11443   ,561,561,561
BEGIN DESCRIPTION:
WALLACE BRANCH 26.0
END DESCRIPTION:
XS GIS Cut Line= 3
      2967597.62      10117388.4      2967028.16     10116989.09
      2966153.31     10117016.86
#Sta/Elev= 30
  4375.2 1010.43  4421.3 1008.39  4478.6  1005.7  4493.4 1002.97  4535.2 1000.57
  4557.4  996.81  4600.6  993.64  4775.6  984.41  4901.3  978.23  4916.1  976.02
  4923.8  971.45  4930.9  963.87    4937   961.3  4951.9  957.65  4966.7  959.49
  4972.8  956.53  4999.4  954.06  5002.2  953.56  5005.4  954.06  5009.3  954.86
    5032  970.02  5045.9  976.85    5053  978.03  5110.4  976.42  5139.8  978.31
  5170.5  980.77  5360.6   983.2  5479.2  986.56  5704.4  993.97    5946 1003.51
#Mann= 8 ,-1 , 0
  4375.2      .1       0  4421.3     .16       0  4775.6      .1       0
  4999.4     .07       0  5005.4      .1       0  5139.8     .05       0
  5479.2      .1       0  5704.4     .05       0
Bank Sta=4999.4,5005.4
XS Rating Curve= 0 ,0
Exp/Cntr=0.3,0.1

Type RM Length L Ch R = 1 ,10882   ,297,297,297
BEGIN DESCRIPTION:
WALLACE BRANCH 25.0
END DESCRIPTION:
XS GIS Cut Line= 4
      2967667.04      10117096.7      2967531.64     10116673.12
      2967288.58     10116516.87      2966529.19     10116388.57
#Sta/Elev= 30
  4436.8 1000.84  4579.1  994.23  4815.5  983.23  4920.8  977.22  4926.7  975.33
  4956.6  973.29  4963.1  971.11  4989.2  951.44  4996.4  948.15  4999.1  947.65
  5002.4  948.15  5020.5  948.89  5035.7  952.68  5041.7  957.66  5050.9     957
  5056.8  961.76    5072  964.48    5078  967.37  5136.6  968.69  5235.2  970.38
  5284.7  971.47  5353.1  974.41  5459.5  976.57  5580.4  981.76  5640.4  985.71
    5651  987.26  5809.5   996.2  5910.9 1007.27  5939.6 1008.55  5940.6 1008.62
#Mann= 12 ,-1 , 0
  4436.8     .16       0  4579.1      .1       0  4815.5     .05       0
  4989.2     .16       0  4996.4     .07       0  5002.4     .16       0
  5136.6     .05       0  5235.2      .1       0  5284.7     .05       0
  5640.4      .1       0    5651     .05       0  5939.6      .1       0
Bank Sta=4996.4,5002.4
XS Rating Curve= 0 ,0
Exp/Cntr=0.3,0.1

Type RM Length L Ch R = 1 ,10585   ,392,392,392
BEGIN DESCRIPTION:
WALLACE BRANCH 24.0
END DESCRIPTION:
XS GIS Cut Line= 4
      2967809.41     10117183.52      2967729.55     10116437.01
      2967403.16     10116259.92      2966614.12     10115948.46
#Sta/Elev= 30
  4042.2 1002.76    4100  1001.2  4363.8  994.32  4529.4  985.61    4641  980.64
    4898  973.04  4930.6  968.55  4942.1  964.21  4964.9   960.6  4976.4  955.58
  4987.6  947.69  4998.9  944.56  5001.6  944.06  5004.9  944.56  5045.6  960.75
  5055.9  963.18  5105.4  965.39  5212.7  966.58  5406.9  973.86  5421.4  975.17
  5525.8  981.64  5630.1  987.83  5712.3  993.26  5749.9  999.45  5793.6 1003.61
    5899 1011.85  5904.4 1014.41  5943.2 1019.12  6006.7 1021.26  6012.6 1021.86
#Mann= 17 ,-1 , 0
  4042.2      .1       0    4100     .16       0  4529.4      .1       0
    4641     .05       0    4898      .1       0  4976.4     .16       0
  4998.9     .07       0  5004.9     .16       0  5105.4      .1       0
  5212.7     .05       0  5406.9      .1       0  5421.4     .05       0
  5525.8      .1       0  5630.1     .05       0  5793.6      .1       0
  5943.2     .16       0  6006.7      .1       0
Bank Sta=4998.9,5004.9
XS Rating Curve= 0 ,0
Exp/Cntr=0.3,0.1

Type RM Length L Ch R = 1 ,10193   ,401,401,401
BEGIN DESCRIPTION:
WALLACE BRANCH 23.0
END DESCRIPTION:
XS GIS Cut Line= 4
      2967889.28     10117312.01      2967882.33     10116329.37
        2967799.     10115968.26      2966955.28     10115846.73
#Sta/Elev= 30
  3757.1  1004.1  3897.1  999.84  4155.4  989.91  4297.7  986.87  4475.1  981.57
  4573.5  976.56  4671.8  971.76  4775.2  966.18    4869  964.26  4873.2  964.52
  4889.2  963.55  4899.5  960.16  4913.8  953.03    4920  948.25  4930.3  946.08
  4961.6  945.09  4996.3  940.84    4999  940.34  5002.3  940.84  5005.4  941.46
  5047.2  956.16  5115.8  956.23  5272.6  957.63  5373.6  962.19    5414  962.12
  5735.5  979.93  5787.5  983.16  5909.1  993.97  5951.8 1001.75  5962.8 1003.29
#Mann= 15 ,-1 , 0
  3757.1      .1       0  3897.1     .16       0  4297.7      .1       0
  4475.1     .05       0  4573.5      .1       0  4671.8     .05       0
    4869      .1       0  4873.2     .05       0  4996.3    .035       0
  5002.3     .05       0  5005.4      .1       0  5115.8     .05       0
  5735.5      .1       0  5787.5     .05       0  5951.8      .1       0
Bank Sta=4996.3,5002.3
XS Rating Curve= 0 ,0
Exp/Cntr=0.3,0.1

Type RM Length L Ch R = 1 ,9792    ,587,587,587
BEGIN DESCRIPTION:
WALLACE BRANCH 22.0
END DESCRIPTION:
XS GIS Cut Line= 4
      2968514.29     10116364.11      2968177.47     10115895.34
      2967882.33     10115721.73      2967049.04      10115700.9
#Sta/Elev= 30
  4233.9  980.83  4407.2  971.08  4414.7  971.06  4833.2  959.38  4868.7  956.35
  4878.6  956.96  4884.4  955.34    4900  956.81  4905.8  955.24  4921.5   955.5
    4943  953.37  4958.6  949.51  4992.6  935.58  4995.4  935.08  4998.6  935.58
    5023  939.25  5053.6  945.81  5081.6  953.57  5089.6  954.29  5152.9  953.05
    5278  954.23  5417.5  959.02  5447.5   961.5  5467.5  960.87  5627.6  970.23
  5737.6  974.86  5807.6  978.97  5877.6  987.08  5947.7  993.29  5987.1 1001.32
#Mann= 6 ,-1 , 0
  4233.9      .1       0  4407.2     .16       0  4414.7      .1       0
  4992.6     .07       0  4998.6      .1       0  5089.6     .05       0
Bank Sta=4992.6,4998.6
XS Rating Curve= 0 ,0
Exp/Cntr=0.3,0.1

Type RM Length L Ch R = 1 ,9205    ,282,282,282
BEGIN DESCRIPTION:
WALLACE BRANCH 21.0
END DESCRIPTION:
XS GIS Cut Line= 4
      2968677.48     10116180.09      2968434.41     10115433.53
       2968198.3      10115350.2      2967083.68     10115537.71
#Sta/Elev= 30
  4082.5  978.37  4197.2  972.36  4382.3  962.32  4509.9  958.09  4625.5  952.19
  4742.7  951.22  4758.6  950.84  4916.9  946.99  4937.2  944.56  4968.1   934.2
  4996.1  929.96  4998.8  929.46  5002.1  929.96  5028.2  944.66  5043.6  948.28
  5060.9  948.89  5209.1  949.02  5413.8  952.17  5614.7  960.27    5656  960.51
  5772.1  966.11  5827.6  966.63  5832.6  967.92    5848  966.57    5919  972.33
  6074.9   981.5  6135.4  987.67  6172.5  993.42    6196   994.2  6248.3 1003.78
#Mann= 7 ,-1 , 0
  4082.5     .16       0  4197.2      .1       0  4742.7     .05       0
  4758.6      .1       0  4996.1     .07       0  5002.1      .1       0
  5028.2     .05       0
Bank Sta=4996.1,5002.1
XS Rating Curve= 0 ,0
Exp/Cntr=0.3,0.1

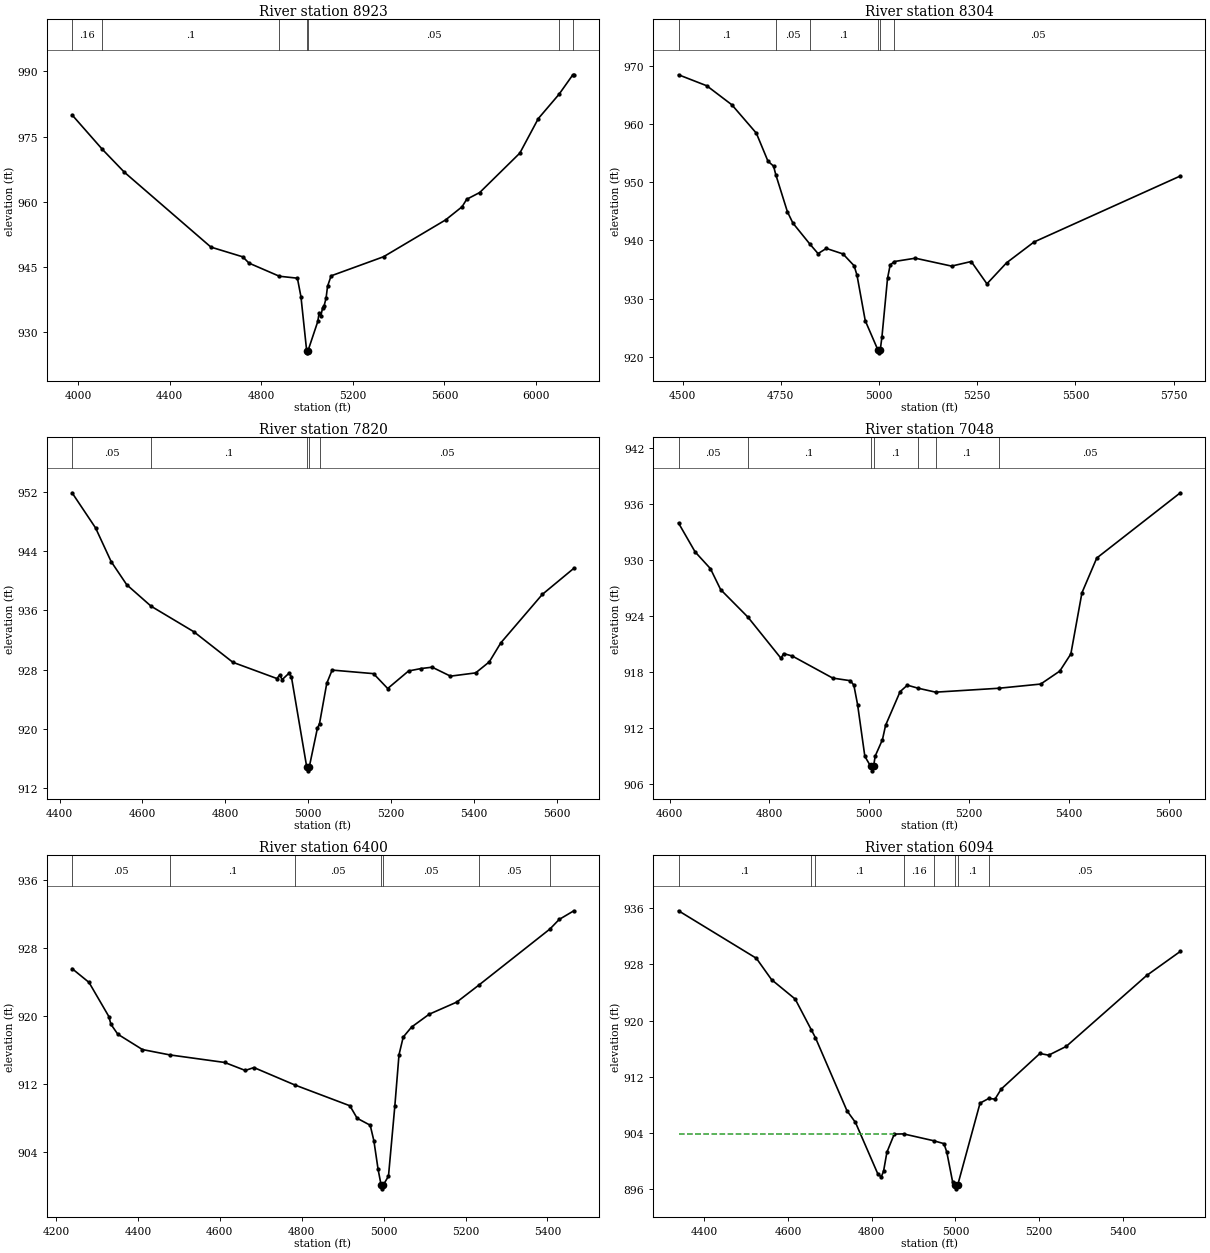
Type RM Length L Ch R = 1 ,8923    ,619,619,619
BEGIN DESCRIPTION:
WALLACE BRANCH 20.0
END DESCRIPTION:
XS GIS Cut Line= 4
      2968805.94     10116117.57        2968549.     10115207.84
      2968292.05     10115051.59      2967354.56     10114923.12
#Sta/Elev= 30
  3973.4  979.98  4105.3  972.08    4202  966.79  4580.1  949.57  4719.3  947.33
  4746.3  945.89    4879  942.87  4957.9  942.42  4973.4  938.16  4998.3  925.75
    5001  925.25  5004.3  925.75    5047  932.48  5052.8  934.44  5059.8  933.64
  5068.3  935.67  5074.2  935.99  5083.2  937.86  5089.6  940.56  5105.1  942.96
  5334.1  947.35  5605.2  955.82  5677.3  958.85  5697.5  960.57  5754.5  962.13
  5929.6  971.19  6010.4  979.14  6100.7  984.71    6161  989.19  6165.7  989.21
#Mann= 7 ,-1 , 0
  3973.4     .16       0  4105.3      .1       0    4879     .05       0
  4998.3    .035       0  5004.3     .05       0  6100.7     .16       0
    6161     .05       0
Bank Sta=4998.3,5004.3
XS Rating Curve= 0 ,0
Exp/Cntr=0.3,0.1

Type RM Length L Ch R = 1 ,8304    ,484,484,484
BEGIN DESCRIPTION:
WALLACE BRANCH 19.0
END DESCRIPTION:
XS GIS Cut Line= 3
      2969229.09     10115074.99      2968785.11     10114602.37
      2968156.25     10114591.96
#Sta/Elev= 30
  4489.7  968.47  4561.6  966.58  4625.6   963.3  4687.8  958.43  4717.4  953.61
  4731.6  952.77  4737.2  951.32  4766.8  944.93  4780.9  942.97    4824  939.37
  4844.9  937.73  4865.9  938.62  4908.4  937.67  4936.7  935.64    4944  934.02
    4965   926.2  4997.2  921.17    5000  920.67  5003.2  921.17  5007.5   923.4
  5021.7  933.46  5028.5  935.78  5039.3  936.37  5092.5  936.94  5184.8  935.58
  5234.8  936.37  5274.8  932.53  5324.8  936.15  5394.8  939.73  5767.1  951.07
#Mann= 6 ,-1 , 0
  4489.7      .1       0  4737.2     .05       0    4824      .1       0
  4997.2     .07       0  5003.2      .1       0  5039.3     .05       0
Bank Sta=4997.2,5003.2
XS Rating Curve= 0 ,0
Exp/Cntr=0.3,0.1

Type RM Length L Ch R = 1 ,7820    ,772,772,772
BEGIN DESCRIPTION:
WALLACE BRANCH 18.0
END DESCRIPTION:
XS GIS Cut Line= 4
      2969469.98     10114700.42      2969285.98     10114374.07
      2968931.81     10114203.93      2968494.32     10114137.96
#Sta/Elev= 30
  4430.3  951.89    4487  947.14  4524.5   942.6  4562.1  939.47  4620.8  936.57
  4723.9  933.12  4818.1  928.99  4924.2   926.8  4931.3  927.29  4936.8  926.65
  4953.9  927.54  4959.4  926.97  4996.2  914.83  4998.9  914.33  5002.2  914.83
  5021.8  920.07    5027  920.72  5044.5  926.16  5057.4  927.94  5157.2  927.46
  5191.4  925.45  5241.7  927.82    5272  928.15  5298.6  928.33  5342.8  927.12
  5403.5  927.56  5436.4  929.05  5464.2  931.62  5564.2  938.16  5640.3  941.69
#Mann= 5 ,-1 , 0
  4430.3     .05       0  4620.8      .1       0  4996.2     .07       0
  5002.2      .1       0    5027     .05       0
Bank Sta=4996.2,5002.2
XS Rating Curve= 0 ,0
Exp/Cntr=0.3,0.1

Type RM Length L Ch R = 1 ,7048    ,648,648,648
BEGIN DESCRIPTION:
WALLACE BRANCH 17.0
END DESCRIPTION:
XS GIS Cut Line= 4
      2969748.66     10114166.11      2969696.57     10113931.71
        2969470.     10113637.44      2969119.44     10113458.27
#Sta/Elev= 30
  4617.9  933.95  4651.1  930.86  4681.8  929.06  4702.3  926.81  4756.9  923.86
  4823.2  919.44  4828.3  919.95  4845.7  919.69  4926.8  917.32  4962.1  917.04
  4969.1  916.56  4976.6  914.47  4991.1  908.93  5002.6  907.87  5005.4  907.37
  5008.6  907.87  5011.9  908.96  5026.4  910.72  5032.7  912.26  5061.8  915.87
  5076.3  916.56  5097.4  916.24  5132.9  915.81  5259.5  916.23  5343.4  916.68
  5381.6  918.07  5403.8  919.91    5426  926.47  5455.7   930.2  5623.1   937.2
#Mann= 7 ,-1 , 0
  4617.9     .05       0  4756.9      .1       0  5002.6     .07       0
  5008.6      .1       0  5097.4     .05       0  5132.9      .1       0
  5259.5     .05       0
Bank Sta=5002.6,5008.6
XS Rating Curve= 0 ,0
Exp/Cntr=0.3,0.1

Type RM Length L Ch R = 1 ,6400    ,306,306,306
BEGIN DESCRIPTION:
WALLACE BRANCH 16.0
END DESCRIPTION:
XS GIS Cut Line= 4
      2969855.42     10114074.92       2969904.9     10113504.63
       2969839.8     10113197.34      2969568.95      10112994.2
#Sta/Elev= 30
  4239.4  925.62  4280.7     924  4329.2  919.98  4334.2  919.07    4351   917.9
  4411.2  916.09    4478  915.46    4612  914.57  4662.2  913.63  4683.4  913.97
  4783.3  911.92  4917.7  909.47  4935.4     908  4967.3  907.18  4976.3  905.34
  4986.5     902  4993.7  900.19  4996.5  899.69  4999.7  900.19  5011.9  901.18
  5027.4  909.43  5037.6  915.48  5047.9  917.56  5068.3  918.74  5111.3  920.25
  5178.7  921.68  5232.3  923.67    5406  930.28  5428.7  931.41  5464.5  932.43
#Mann= 7 ,-1 , 0
  4239.4     .05       0    4478      .1       0  4783.3     .05       0
  4993.7     .07       0  4999.7     .05       0  5232.3     .05       0
    5406      .1       0
Bank Sta=4993.7,4999.7
XS Rating Curve= 0 ,0
Exp/Cntr=0.3,0.1

Type RM Length L Ch R = 1 ,6094    ,593,593,593
BEGIN DESCRIPTION:
WALLACE BRANCH 15.0
END DESCRIPTION:
XS GIS Cut Line= 4
      2970738.26     10113470.78      2970199.17     10113280.67
      2970022.09     10113028.07      2969723.03     10112916.24
#Sta/Elev= 30
  4338.2  935.62  4524.2  928.86  4560.7  925.81    4617  923.06  4655.2  918.72
  4665.5  917.55  4740.9  907.15  4761.1   905.5  4815.1   898.1  4822.9  897.77
  4828.2  898.54  4836.3  901.27  4853.9  903.84    4876  903.87  4947.7   902.9
  4972.6  902.48  4979.4  901.28  4993.6  896.96  4999.3  896.55    5002  896.05
  5005.3  896.55  5058.9  908.25  5079.7  908.91  5094.7  908.82  5109.5  910.25
  5201.9  915.31  5222.9  915.07  5264.9  916.32  5457.1  926.41  5537.6  929.84
#Mann= 8 ,-1 , 0
  4338.2      .1       0  4655.2     .16       0  4665.5      .1       0
    4876     .16       0  4947.7      .1       0  4999.3     .07       0
  5005.3      .1       0  5079.7     .05       0
#XS Ineff= 2 , 0
         4853.07  903.83
Permanent Ineff=
       F       F
Bank Sta=4999.3,5005.3
XS Rating Curve= 0 ,0
Exp/Cntr=0.3,0.1

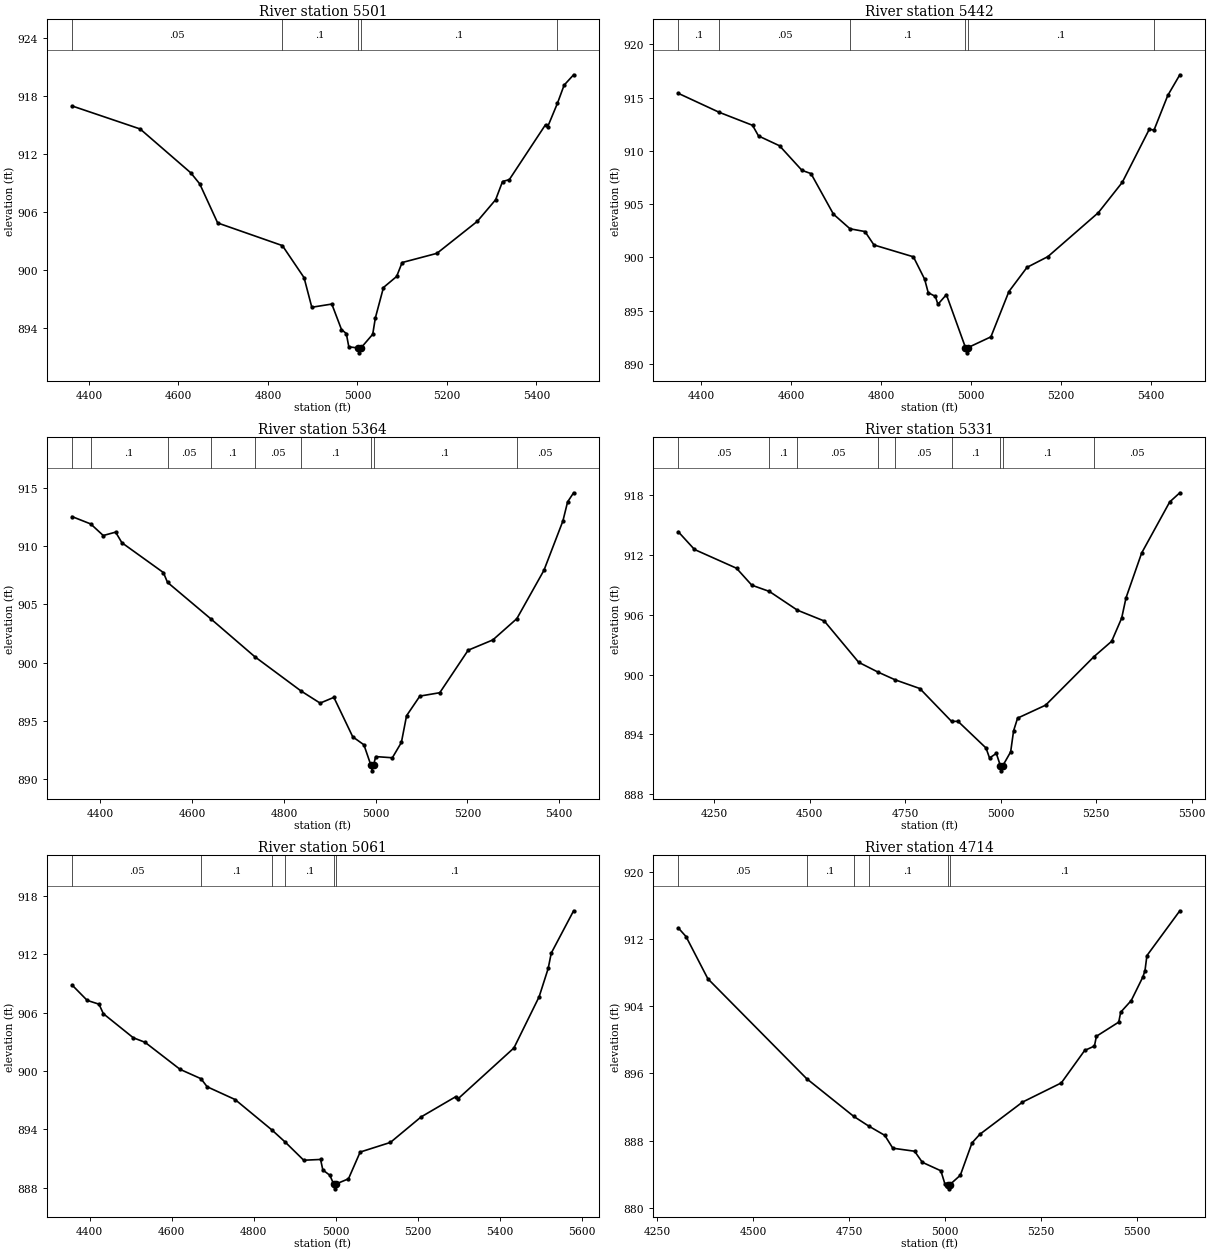
Type RM Length L Ch R = 1 ,5501    ,59,59,59
BEGIN DESCRIPTION:
WALLACE BRANCH 14.0
END DESCRIPTION:
XS GIS Cut Line= 4
      2971083.17     10112798.03      2970565.84     10112766.78
      2970362.71     10112683.45      2969987.74     10112607.06
#Sta/Elev= 30
  4362.5  916.97  4514.6  914.59  4627.7  910.06  4647.7  908.92  4687.8  904.88
  4832.4  902.54  4880.8  899.23  4898.1  896.17  4942.8   896.5  4964.4  893.87
  4975.2  893.45  4980.8  892.08  5001.8  891.96  5004.5  891.46  5007.8  891.96
  5034.2  893.38  5040.1  895.07  5058.2  898.21  5087.6  899.35  5099.9  900.79
  5177.6  901.74  5267.9  905.05  5308.8  907.28  5324.2  909.16  5339.4  909.36
  5420.2  915.03  5425.3  914.84    5447  917.26  5461.8  919.12    5483  920.19
#Mann= 5 ,-1 , 0
  4362.5     .05       0  4832.4      .1       0  5001.8     .07       0
  5007.8      .1       0    5447     .05       0
Bank Sta=5001.8,5007.8
XS Rating Curve= 0 ,0
Exp/Cntr=0.3,0.1

Type RM Length L Ch R = 1 ,5442    ,78,78,78
BEGIN DESCRIPTION:
WALLACE BRANCH 13.0
END DESCRIPTION:
XS GIS Cut Line= 4
      2971133.57      10112733.8      2970588.41     10112718.17
      2970404.38     10112646.99      2970042.52     10112556.96
#Sta/Elev= 30
  4348.9   915.4  4439.9  913.62  4514.1   912.4  4527.4   911.4  4574.1  910.48
  4624.1  908.17  4644.1  907.87  4694.1  904.06  4730.9  902.69  4764.2  902.43
  4784.2  901.17  4871.9  900.06  4896.9  897.96  4904.9  896.69  4920.7  896.35
  4926.4   895.6  4945.3  896.51  4987.7  891.55  4990.5  891.05  4993.7  891.55
  5044.3  892.55  5084.3   896.8  5124.6  899.07  5171.1  900.08  5283.2   904.2
  5336.4  907.04  5396.5  912.02  5407.2  911.96  5437.8  915.21  5464.5  917.14
#Mann= 6 ,-1 , 0
  4348.9      .1       0  4439.9     .05       0  4730.9      .1       0
  4987.7     .07       0  4993.7      .1       0  5407.2     .05       0
Bank Sta=4987.7,4993.7
XS Rating Curve= 0 ,0
Exp/Cntr=0.3,0.1

Type RM Length L Ch R = 1 ,5364    ,33,33,33
BEGIN DESCRIPTION:
WALLACE BRANCH 12.0
END DESCRIPTION:
XS GIS Cut Line= 5
      2971175.23     10112686.92      2970966.88     10112646.99
      2970588.41      10112633.1      2970430.42     10112577.54
      2970105.78     10112494.21
#Sta/Elev= 30
  4338.1  912.51  4378.8  911.88  4406.1  910.89  4433.1  911.18  4446.8  910.27
  4537.2  907.72  4546.2  906.88  4641.1  903.74  4736.6  900.51  4837.6  897.57
  4878.9  896.54  4908.9  897.03  4950.1  893.65  4974.4  892.97  4989.5  891.24
  4992.3  890.74  4995.5  891.24  5000.1  891.96  5036.4  891.86  5056.1  893.17
  5067.4  895.46  5096.4  897.14  5139.8  897.43  5201.7  901.07  5255.5  901.95
  5307.8  903.77  5366.9  907.91  5408.2  912.13  5418.5  913.77  5431.6  914.55
#Mann= 9 ,-1 , 0
  4338.1     .05       0  4378.8      .1       0  4546.2     .05       0
  4641.1      .1       0  4736.6     .05       0  4837.6      .1       0
  4989.5     .07       0  4995.5      .1       0  5307.8     .05       0
Bank Sta=4989.5,4995.5
XS Rating Curve= 0 ,0
Exp/Cntr=0.3,0.1

Type RM Length L Ch R = 1 ,5331    ,270,270,270
BEGIN DESCRIPTION:
WALLACE BRANCH 11.0
END DESCRIPTION:
XS GIS Cut Line= 4
      2971360.93     10112605.32       2970602.3     10112601.85
      2970454.73     10112554.98      2970073.14     10112435.29
#Sta/Elev= 30
  4155.7  914.33  4198.2  912.55  4308.2  910.67  4348.2  908.97  4394.3  908.34
  4467.7  906.46  4538.2  905.37  4628.2  901.23  4678.1  900.26  4723.8  899.47
  4788.2   898.6  4871.4   895.3  4888.2  895.31  4961.6  892.63  4970.8  891.63
  4988.6  892.09  4999.3  890.84  5002.1  890.34  5005.3  890.84  5026.1  892.24
  5033.8  894.36  5044.3  895.63  5117.7  896.93  5244.1  901.79  5290.6  903.34
  5316.8  905.66  5328.2   907.7  5369.2   912.2  5442.6  917.32  5469.1  918.24
#Mann= 9 ,-1 , 0
  4155.7     .05       0  4394.3      .1       0  4467.7     .05       0
  4678.1      .1       0  4723.8     .05       0  4871.4      .1       0
  4999.3     .07       0  5005.3      .1       0  5244.1     .05       0
Bank Sta=4999.3,5005.3
XS Rating Curve= 0 ,0
Exp/Cntr=0.3,0.1

Type RM Length L Ch R = 1 ,5061    ,347,347,347
BEGIN DESCRIPTION:
Mapping XS 93e98441
END DESCRIPTION:
XS GIS Cut Line= 3
      2971291.91     10112547.97      2970725.53     10112387.82
      2970152.42     10112116.21
#Sta/Elev= 30
    4357  908.84  4393.9  907.26  4422.7  906.87  4433.3  905.89  4506.2  903.42
    4535  902.95  4620.4  900.17  4671.3  899.21  4686.4  898.38  4754.4  897.07
  4844.3  893.94  4877.3  892.67  4921.8  890.83  4962.9  890.91  4968.4  889.83
  4985.6  889.28  4994.7  888.39  4997.4  887.89  5000.7  888.39  5030.9  888.92
  5059.4  891.67  5133.1  892.66  5207.9  895.28  5292.3  897.36  5297.9  897.14
  5434.3  902.37  5495.7  907.63  5517.8  910.54  5525.3  912.12  5579.8  916.47
#Mann= 6 ,-1 , 0
    4357     .05       0  4671.3      .1       0  4844.3     .05       0
  4877.3      .1       0  4994.7     .07       0  5000.7      .1       0
Bank Sta=4994.7,5000.7
XS Rating Curve= 0 ,0
Exp/Cntr=0.3,0.1

Type RM Length L Ch R = 1 ,4714    ,366,366,366
BEGIN DESCRIPTION:
Mapping XS ed689493
END DESCRIPTION:
XS GIS Cut Line= 3
       2971401.3     10112529.73      2970924.75     10112106.57
      2970263.41     10112005.02
#Sta/Elev= 30
  4305.3  913.34  4325.5  912.31  4382.4  907.28  4639.8  895.38  4762.1   890.9
  4800.9  889.75  4843.2  888.63  4864.1   887.1  4920.9  886.74    4941  885.42
  4989.3  884.41  4999.6  882.88  5006.7  882.76  5009.4  882.26  5012.7  882.76
    5040  883.88  5070.4  887.73  5090.6  888.75  5201.9  892.59  5303.1  894.88
  5363.8  898.74  5389.3  899.27  5394.4  900.43  5452.6  902.12  5457.7   903.3
  5485.2  904.69  5515.5   907.5    5521  908.26    5526  910.04  5611.7  915.38
#Mann= 6 ,-1 , 0
  4305.3     .05       0  4639.8      .1       0  4762.1     .05       0
  4800.9      .1       0  5006.7     .07       0  5012.7      .1       0
Bank Sta=5006.7,5012.7
XS Rating Curve= 0 ,0
Exp/Cntr=0.3,0.1

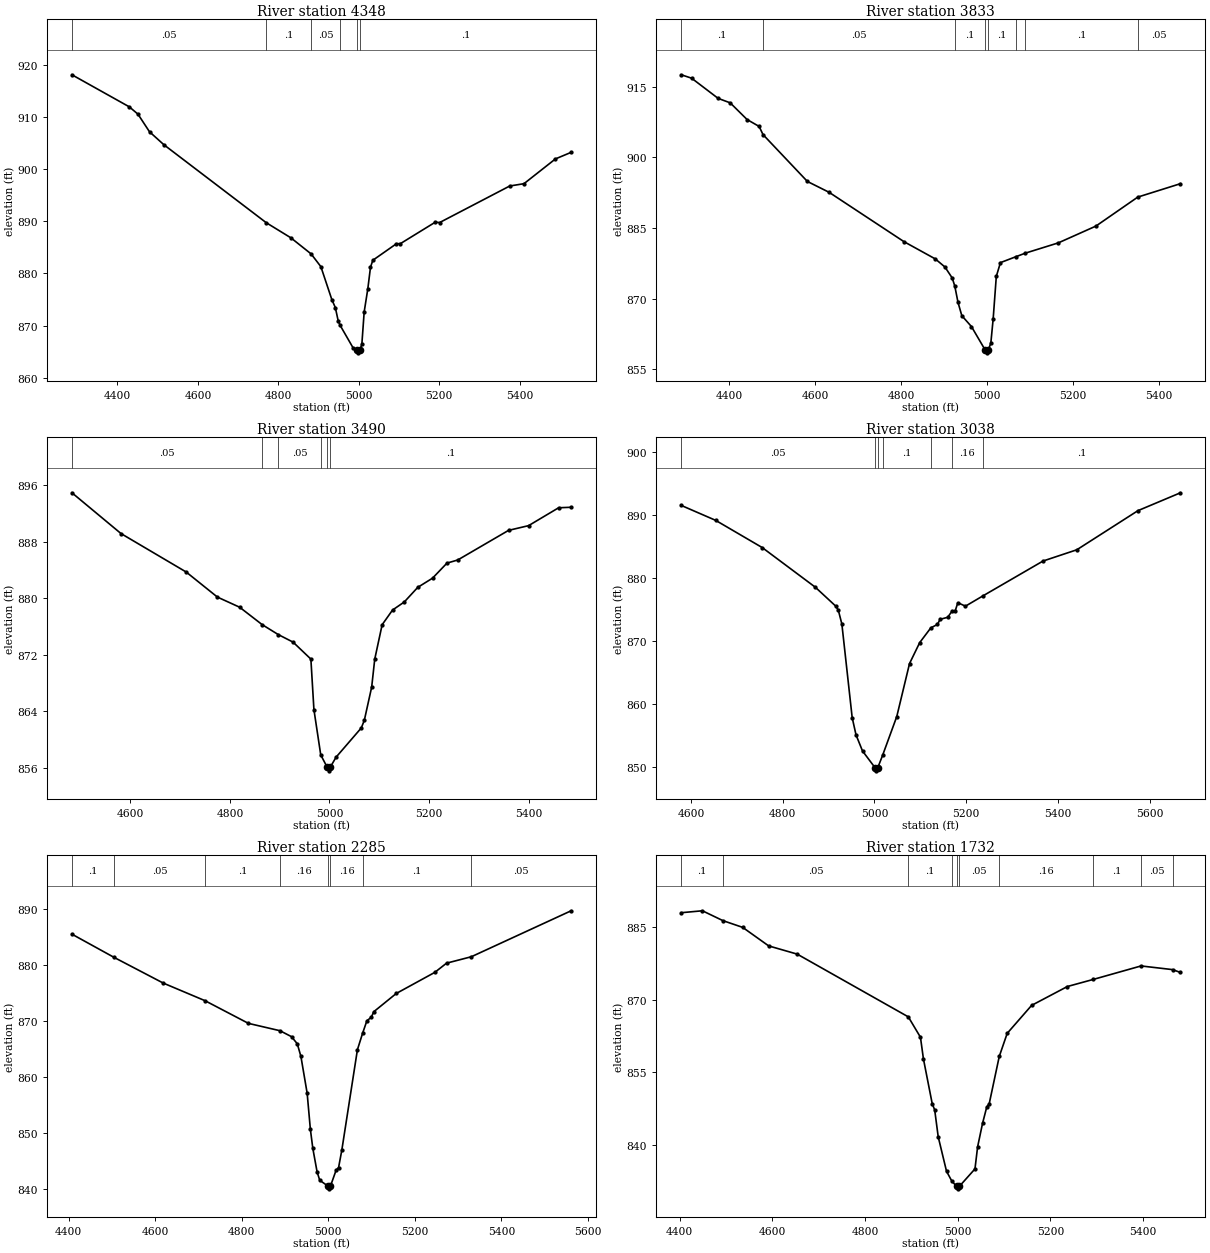
Type RM Length L Ch R = 1 ,4348    ,515,515,515
BEGIN DESCRIPTION:
WALLACE BRANCH 10.0
END DESCRIPTION:
XS GIS Cut Line= 3
      2971525.89     10112530.63      2971067.57       10111739.
      2970812.07     10111535.29
#Sta/Elev= 30
  4286.7  918.04  4429.4   911.9  4450.9   910.5  4479.6  907.13  4515.5  904.64
    4770  889.72  4831.2  886.83  4881.5  883.75  4905.8  881.31  4933.1     875
  4941.8  873.47  4948.8  870.96  4953.5   870.1  4986.1  865.74  4996.5  865.31
  4999.3  864.81  5002.5  865.31  5007.7  866.42  5013.5  872.63  5022.6  877.09
  5029.2  881.19    5035  882.53  5093.8   885.7  5103.5  885.71  5189.9   889.8
  5201.4  889.76  5375.6  896.75  5410.9  897.19  5489.3  901.94  5528.2  903.19
#Mann= 6 ,-1 , 0
  4286.7     .05       0    4770      .1       0  4881.5     .05       0
  4953.5      .1       0  4996.5     .07       0  5002.5      .1       0
Bank Sta=4996.5,5002.5
XS Rating Curve= 0 ,0
Exp/Cntr=0.3,0.1

Type RM Length L Ch R = 1 ,3833    ,343,343,343
BEGIN DESCRIPTION:
WALLACE BRANCH 9.0
END DESCRIPTION:
XS GIS Cut Line= 3
      2971873.14     10112232.07      2971470.35     10111412.61
      2971248.77     10111298.36
#Sta/Elev= 30
  4288.5  917.52  4312.5   916.8  4374.3  912.51  4402.4  911.56  4441.8  908.01
  4469.8  906.55  4478.8  904.82  4582.2  894.86  4632.7  892.56    4807  882.08
    4880  878.41  4902.5  876.69  4919.4  874.36  4925.4  872.65  4932.9  869.18
  4941.8  866.35  4964.3  864.03  4996.8  858.96  4999.5  858.46  5002.8  858.96
  5009.3  860.48  5014.8   865.7  5022.1   874.7  5031.7  877.62  5068.6  878.91
  5089.9  879.64  5166.6  881.82    5254  885.38  5351.5  891.54  5450.9  894.39
#Mann= 8 ,-1 , 0
  4288.5      .1       0  4478.8     .05       0  4925.4      .1       0
  4996.8     .07       0  5002.8      .1       0  5068.6     .05       0
  5089.9      .1       0  5351.5     .05       0
Bank Sta=4996.8,5002.8
XS Rating Curve= 0 ,0
Exp/Cntr=0.3,0.1

Type RM Length L Ch R = 1 ,3490    ,452,452,452
BEGIN DESCRIPTION:
WALLACE BRANCH 8.0
END DESCRIPTION:
XS GIS Cut Line= 3
      2972237.73     10111662.63      2971557.16     10111190.39
      2971383.57     10111169.56
#Sta/Elev= 30
  4482.4  894.94    4581  889.17    4712  883.73  4774.8  880.18  4819.4  878.75
  4864.6  876.29    4897  874.88  4926.8  873.81  4962.6  871.41  4968.7  864.27
  4982.4  857.86  4995.4   856.1  4998.1   855.6  5001.4   856.1  5013.2  857.53
  5063.9  861.67    5070  862.75  5084.8  867.46  5090.9  871.39  5105.8  876.27
  5126.7  878.35  5150.3  879.49  5177.4  881.56  5207.1  882.86  5236.1  884.99
  5257.7  885.43  5359.8  889.62  5400.1  890.29  5460.5  892.82  5485.6  892.89
#Mann= 6 ,-1 , 0
  4482.4     .05       0  4864.6      .1       0    4897     .05       0
  4982.4      .1       0  4995.4     .07       0  5001.4      .1       0
Bank Sta=4995.4,5001.4
XS Rating Curve= 0 ,0
Exp/Cntr=0.3,0.1

Type RM Length L Ch R = 1 ,3038    ,753,753,753
BEGIN DESCRIPTION:
WALLACE BRANCH 7.0
END DESCRIPTION:
XS GIS Cut Line= 4
      2972494.67     10111461.23      2972258.55      10111301.5
      2971994.66     10110787.61      2971780.29     10110718.46
#Sta/Elev= 30
    4579  891.54  4653.9  889.17  4755.5  884.84  4871.2  878.54  4915.6  875.54
  4921.2  874.92    4929   872.7  4951.5  857.82  4959.9  855.07    4974  852.52
  5001.3  849.86  5004.1  849.36  5007.3  849.86  5017.8  851.82  5048.7  857.99
  5076.5  866.41  5098.7  869.74    5123  872.09  5137.4  872.63  5143.1  873.44
  5159.6  873.76  5169.1  874.73  5176.2  874.82  5181.8  876.08  5198.4  875.53
  5235.9  877.14  5367.4   882.7  5441.1  884.49  5574.4  890.71    5667  893.55
#Mann= 7 ,-1 , 0
    4579     .05       0  5001.3    .035       0  5007.3     .05       0
  5017.8      .1       0    5123     .05       0  5169.1     .16       0
  5235.9      .1       0
Bank Sta=5001.3,5007.3
XS Rating Curve= 0 ,0
Exp/Cntr=0.3,0.1

Type RM Length L Ch R = 1 ,2285    ,553,553,553
BEGIN DESCRIPTION:
WALLACE BRANCH 5.0
END DESCRIPTION:
XS GIS Cut Line= 4
      2972716.88     10111044.57      2972702.99     10110620.95
       2972314.1     10110405.67      2972029.54     10110398.73
#Sta/Elev= 30
  4407.9   885.5  4505.5  881.35  4618.9  876.78  4715.1  873.65  4815.6   869.6
  4888.5  868.29  4915.1  867.23  4928.4  865.96  4936.8   863.7  4951.2  857.15
  4958.6  850.73  4964.3  847.31  4974.1  843.15  4980.3  841.63  4999.1  840.61
  5001.8  840.11  5005.1  840.61  5018.1  843.44  5023.8  843.91  5031.2  846.98
  5067.3  864.91  5079.3  867.85  5089.1  870.05  5099.4  870.71  5105.1  871.68
    5157  874.93    5246  878.69  5273.1  880.33  5330.5  881.48  5560.9  889.67
#Mann= 8 ,-1 , 0
  4407.9      .1       0  4505.5     .05       0  4715.1      .1       0
  4888.5     .16       0  4999.1     .07       0  5005.1     .16       0
  5079.3      .1       0  5330.5     .05       0
Bank Sta=4999.1,5005.1
XS Rating Curve= 0 ,0
Exp/Cntr=0.3,0.1

Type RM Length L Ch R = 1 ,1732    ,309,309,309
BEGIN DESCRIPTION:
WALLACE BRANCH 4.0
END DESCRIPTION:
XS GIS Cut Line= 3
      2972779.38     10111065.39      2973036.32     10110350.11
      2972980.86     10110038.13
#Sta/Elev= 30
  4403.5  888.03  4449.1  888.43  4493.3  886.39    4536  884.99  4592.1  881.15
  4653.6  879.45  4893.3  866.45  4919.5  862.23  4925.9  857.75  4944.9  848.45
  4950.2  847.18  4957.8   841.6  4975.7  834.47  4986.6  832.52  4997.3  831.32
    5000  830.82  5003.3  831.32  5037.1  834.95  5042.8  839.52  5053.4  844.37
  5062.5  847.77  5067.8  848.44  5089.5  858.25  5106.6  863.03  5159.3  868.83
  5236.5  872.74  5292.4  874.21  5395.4     877  5463.4  876.24  5480.4  875.65
#Mann= 10 ,-1 , 0
  4403.5      .1       0  4493.3     .05       0  4893.3      .1       0
  4986.6     .05       0  4997.3    .035       0  5003.3     .05       0
  5089.5     .16       0  5292.4      .1       0  5395.4     .05       0
  5463.4      .1       0
Bank Sta=4997.3,5003.3
XS Rating Curve= 0 ,0
Exp/Cntr=0.3,0.1

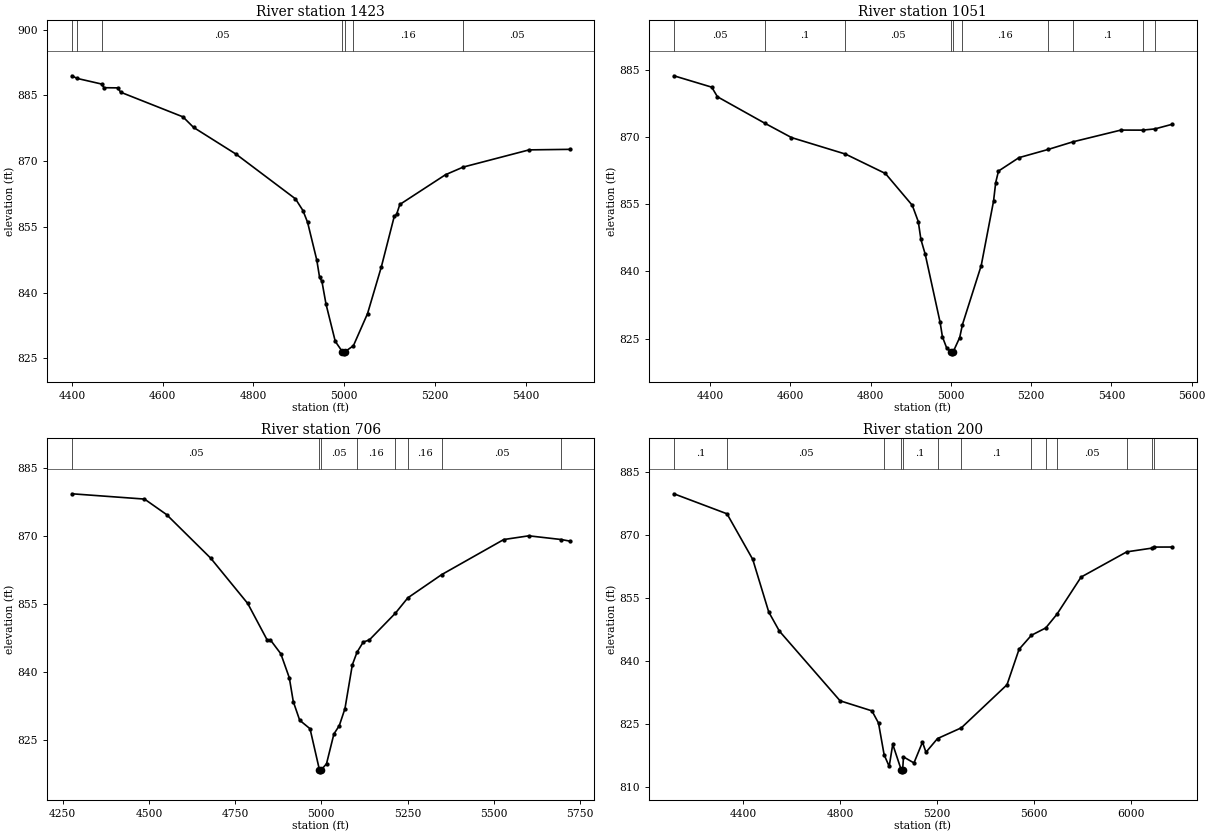
Type RM Length L Ch R = 1 ,1423    ,372,372,372
BEGIN DESCRIPTION:
WALLACE BRANCH 3.0
END DESCRIPTION:
XS GIS Cut Line= 4
      2973036.33     10111100.11      2973244.66     10110773.73
      2973321.05     10110357.06      2973182.16     10110107.06
#Sta/Elev= 30
  4400.1  889.47  4411.7  888.87  4465.4  887.59    4471  886.75  4501.5  886.71
  4507.4  885.73  4644.9   880.1  4668.2   877.7  4762.1  871.58  4892.8   861.4
  4909.3  858.73  4919.5  856.05  4939.8  847.44    4946  843.47  4951.1  842.59
  4960.1   837.4  4980.5   828.9  4996.1  826.55  4998.9  826.05  5002.1  826.55
  5020.5   827.9  5051.6  835.22  5082.1   845.9  5110.5   857.4  5115.6  857.86
  5122.8  860.12  5223.5  866.91  5262.5  868.65  5407.7  872.57  5496.9  872.69
#Mann= 7 ,-1 , 0
  4400.1     .05       0  4411.7      .1       0  4465.4     .05       0
  4996.1    .035       0  5002.1     .05       0  5020.5     .16       0
  5262.5     .05       0
Bank Sta=4996.1,5002.1
XS Rating Curve= 0 ,0
Exp/Cntr=0.3,0.1

Type RM Length L Ch R = 1 ,1051    ,345,345,345
BEGIN DESCRIPTION:
WALLACE BRANCH 2.0
END DESCRIPTION:
XS GIS Cut Line= 4
      2973161.34     10111169.55      2973584.93     10110808.45
      2973696.05     10110523.73      2973494.65     10110204.27
#Sta/Elev= 30
  4310.2  883.63  4404.5  881.09  4418.7  878.95  4537.5  873.01  4603.2  869.85
  4737.6  866.17  4837.1  861.84  4904.1  854.74    4919  851.12  4925.6  847.12
  4936.3  843.83  4973.3  828.69  4979.2  825.41    4990  822.87  5000.2  822.12
  5002.9  821.62  5006.2  822.12  5022.2  825.26  5029.1  828.16  5075.8  841.31
  5106.5  855.67  5111.9  859.82  5118.8  862.38  5169.8  865.37  5242.5   867.2
  5304.2   868.9  5423.8  871.52  5477.6  871.51  5508.4  871.78  5550.1  872.78
#Mann= 10 ,-1 , 0
  4310.2     .05       0  4537.5      .1       0  4737.6     .05       0
  5000.2    .035       0  5006.2     .05       0  5029.1     .16       0
  5242.5     .05       0  5304.2      .1       0  5477.6     .05       0
  5508.4      .1       0
Bank Sta=5000.2,5006.2
XS Rating Curve= 0 ,0
Exp/Cntr=0.3,0.1

Type RM Length L Ch R = 1 ,706     ,506,506,506
BEGIN DESCRIPTION:
Mapping XS 3fe7c49d
END DESCRIPTION:
XS GIS Cut Line= 4
      2973433.85     10111346.17      2973880.49     10110990.21
      2973980.25      10110729.5      2973658.33     10110230.75
#Sta/Elev= 30
  4276.3  879.37    4487   878.2    4551  874.78  4679.2  865.14  4786.5  855.15
  4842.9  847.09  4852.4  847.09  4882.4  844.06  4907.1  838.75  4918.6   833.5
  4937.2  829.38  4967.2   827.5  4994.3  818.49  4997.1  817.99  5000.3  818.49
    5015  819.77  5036.4  826.34  5052.1   828.2  5068.5  831.94  5089.9  841.61
  5103.6  844.41  5121.6  846.64  5139.2   847.1  5214.9  853.02  5250.9   856.4
  5349.2  861.53  5529.2  869.27  5601.8  870.09  5696.1  869.27  5720.2  868.93
#Mann= 8 ,-1 , 0
  4276.3     .05       0  4994.3    .035       0  5000.3     .05       0
  5103.6     .16       0  5214.9      .1       0  5250.9     .16       0
  5349.2     .05       0  5696.1      .1       0
Bank Sta=4994.3,5000.3
XS Rating Curve= 0 ,0
Exp/Cntr=0.3,0.1

Type RM Length L Ch R = 1 ,200     ,0,0,0
BEGIN DESCRIPTION:
WALLACE BRANCH 1.0
END DESCRIPTION:
XS GIS Cut Line= 4
      2973633.38     10111568.32      2974290.84     10111207.85
      2974395.12     10111065.03      2973685.53     10110192.21
#Sta/Elev= 30
  4115.8  879.77  4334.7     875  4440.9  864.13  4506.9  851.58  4550.5  847.06
  4800.8  830.44  4932.1  828.04  4959.2  825.14  4982.4  817.57  5003.2  814.81
  5017.9  820.06  5052.7  814.01  5055.5  813.51  5058.7  814.01  5062.2  817.07
  5105.3  815.63  5140.5  820.59  5154.8  818.18  5202.4  821.44  5300.7     824
  5488.8  834.26  5538.4   842.7  5589.3  846.05  5648.5   847.8  5694.4  851.05
  5794.1  859.92  5982.3  865.93  6085.9  866.82  6094.6  867.07  6167.3  867.08
#Mann= 13 ,-1 , 0
  4115.8      .1       0  4334.7     .05       0  4982.4      .1       0
  5052.7     .07       0  5058.7      .1       0  5202.4     .16       0
  5300.7      .1       0  5589.3     .05       0  5648.5      .1       0
  5694.4     .05       0  5982.3      .1       0  6085.9     .05       0
  6094.6      .1       0
Bank Sta=5052.7,5058.7
XS Rating Curve= 0 ,0
Exp/Cntr=0.3,0.1

Chan Stop Cuts=-1
Use User Specified Reach Order=0
Composite Channel Slope=5