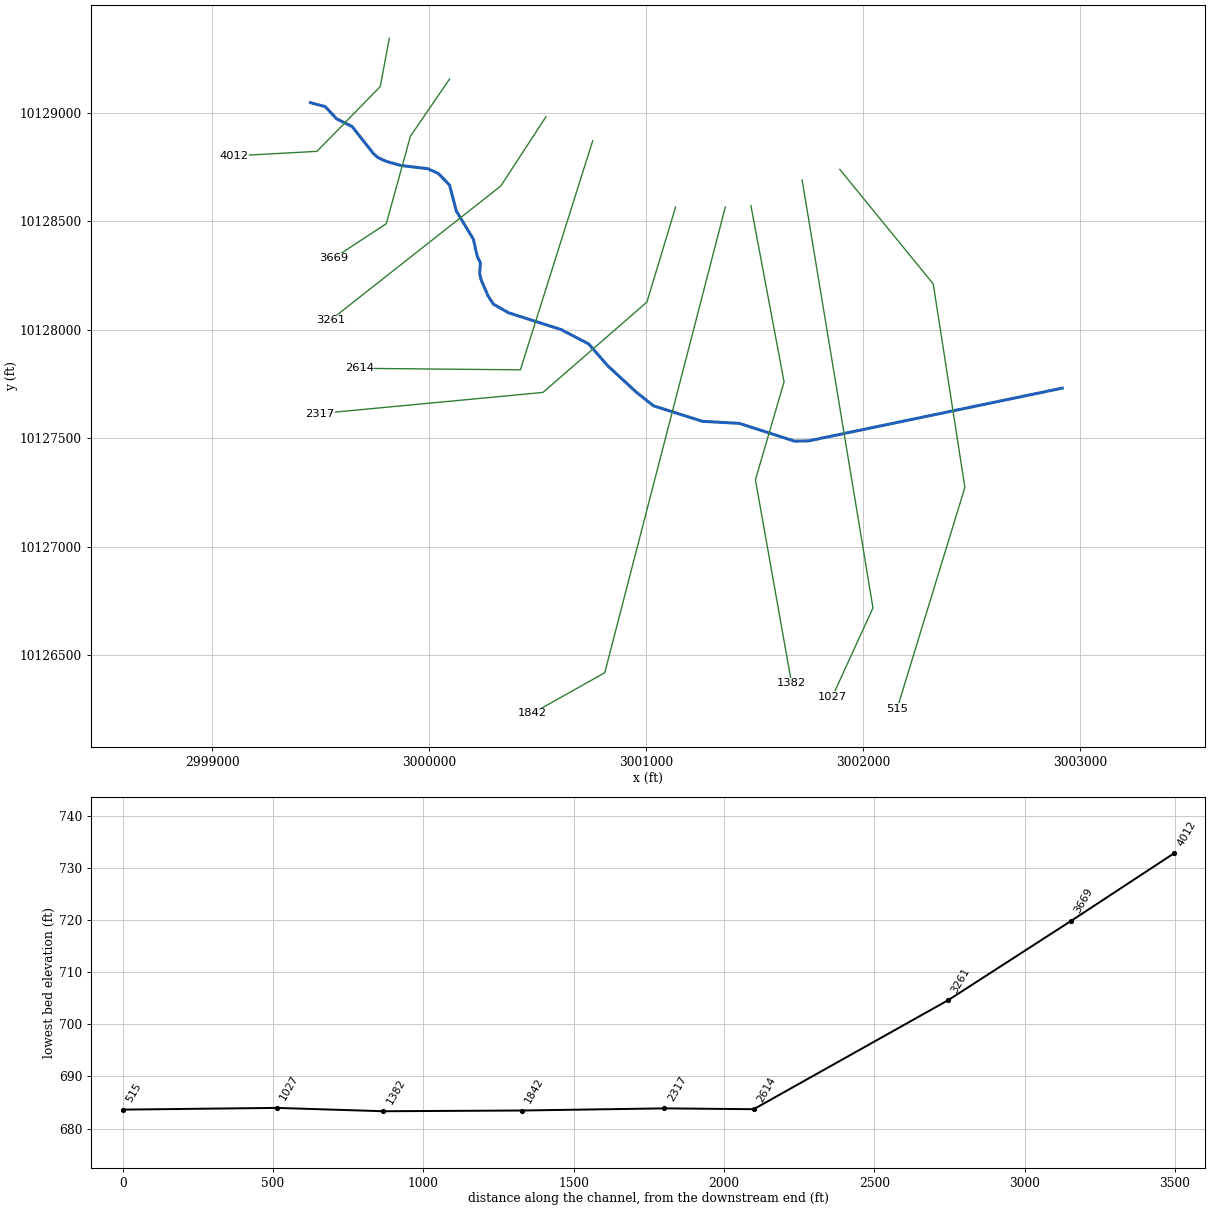
--- WILSON HOLLOW.prj (project) ---

Proj Title=WILSON HOLLOW Base Level Engineering
Current Plan=p01
Default Exp/Contr=0.3,0.1
English Units
Geom File=g01
Flow File=f01
Plan File=p01
BEGIN DESCRIPTION:
WILSON HOLLOW
END DESCRIPTION:

--- WILSON HOLLOW.p01 (plan) ---

Plan Title=Multiple Run
Short Identifier=Multiple
Geom File=g01
Flow File=f01
Subcritical Flow
K Sum by GR= 0
Std Step Tol= 0.01
Critical Tol= 0.01
Num of Std Step Trials= 20
Max Error Tol= 0.3
Flow Tol Ratio= 0.001
Split Flow NTrial= 30
Split Flow Tol= 0.02
Split Flow Ratio= 0.02
Log Output Level= 0
Friction Slope Method= 1
Unsteady Friction Slope Method= 2
Unsteady Bridges Friction Slope Method= 1
Parabolic Critical Depth
Global Vel Dist=  1 , 1 , 1
Global Log Level= 0
CheckData=True
Encroach Param= -1, 0, 0, 0
BEGIN DESCRIPTION:
Multiple Run
END DESCRIPTION:

--- WILSON HOLLOW.f01 (steady flow) ---

Flow Title=Multiple
Number of Profiles=7
Profile Names=10-year,25-year,50-year,1pct_min,100-year,1pct_plu,500-year
River Rch & RM= WILSON HOLLOW,Reach-1,4012
     891    1306    1671    1567    2119    2866    3420
Boundary for River Rch & Prof#=WILSON HOLLOW,Reach-1,1
Up Type=0
Dn Type=3
Dn Slope=0.005
Boundary for River Rch & Prof#=WILSON HOLLOW,Reach-1,2
Up Type=0
Dn Type=3
Dn Slope=0.005
Boundary for River Rch & Prof#=WILSON HOLLOW,Reach-1,3
Up Type=0
Dn Type=3
Dn Slope=0.005
Boundary for River Rch & Prof#=WILSON HOLLOW,Reach-1,4
Up Type=0
Dn Type=3
Dn Slope=0.005
Boundary for River Rch & Prof#=WILSON HOLLOW,Reach-1,5
Up Type=0
Dn Type=3
Dn Slope=0.005
Boundary for River Rch & Prof#=WILSON HOLLOW,Reach-1,6
Up Type=0
Dn Type=3
Dn Slope=0.005
Boundary for River Rch & Prof#=WILSON HOLLOW,Reach-1,7
Up Type=0
Dn Type=3
Dn Slope=0.005

--- WILSON HOLLOW.g01 (geometry) ---

Geom Title=Existing Conditions

River Reach=WILSON HOLLOW,Reach-1
Reach XY= 30
      2999452.82     10129046.23      2999520.91     10129028.11
      2999572.96     10128972.28      2999644.82     10128936.16
      2999743.41     10128811.08      2999763.43     10128793.78
      2999799.59     10128776.62      2999869.70     10128756.71
      2999992.83     10128742.15      3000041.92     10128720.30
      3000093.68     10128666.85      3000125.02     10128547.01
      3000203.84     10128416.60      3000220.96     10128339.70
      3000235.92     10128307.64      3000232.52     10128257.28
      3000239.51     10128229.24      3000271.64     10128154.94
      3000296.08     10128117.63      3000365.49     10128078.03
      3000608.18     10128000.55      3000735.10     10127934.23
      3000823.23     10127833.32      3000956.18     10127710.60
      3001034.31     10127648.97      3001259.13     10127577.79
      3001429.27     10127568.24      3001682.74     10127486.65
      3001747.85     10127487.51      3002917.93     10127730.75

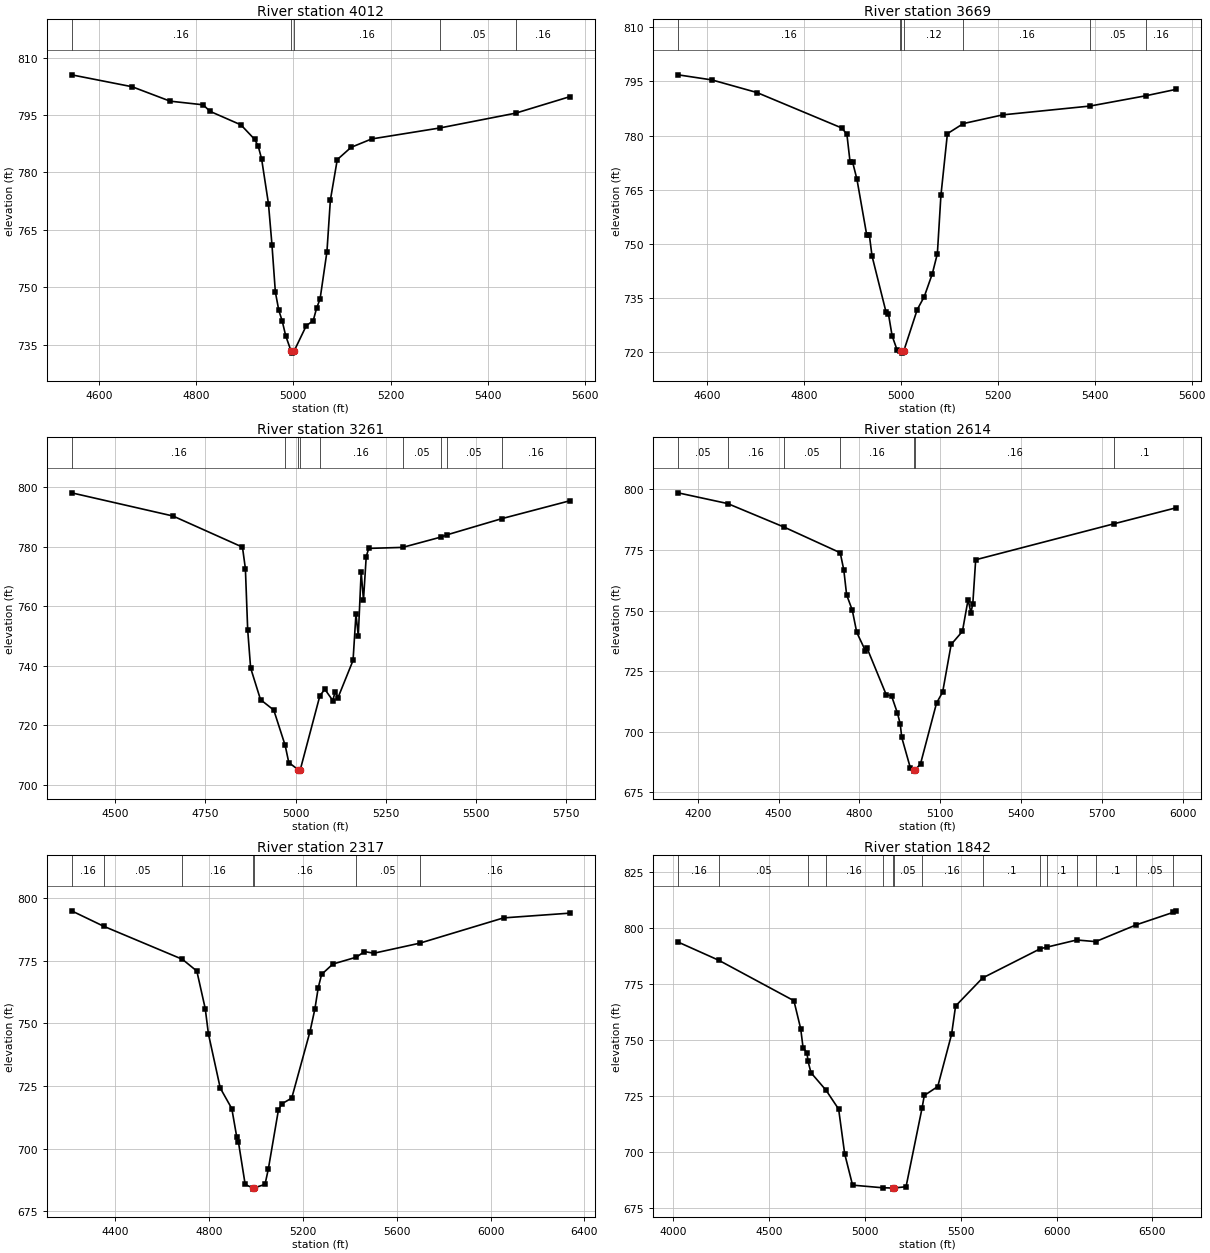
Type RM Length L Ch R = 1,4012,343,343,343
BEGIN DESCRIPTION:
WILSON HOLLOW 9.0
END DESCRIPTION:
XS GIS Cut Line= 4
      2999816.05     10129342.85      2999774.38     10129120.60
      2999482.71     10128821.99      2999102.12     10128801.23
#Sta/Elev= 30
  4544.0  805.51  4668.4  802.40  4746.6  798.63  4814.5  797.68  4828.7  795.97
  4892.2  792.44  4920.5  788.65  4927.7  786.90  4934.7  783.57  4948.8  771.87
  4956.0  761.15  4963.0  748.79  4970.1  743.98  4977.1  741.20  4984.3  737.34
  4995.4  733.31  4998.2  732.81  5001.4  733.31  5026.7  740.00  5040.8  741.27
  5047.8  744.55  5055.0  746.98  5069.1  759.34  5076.1  772.76  5090.3  783.36
  5118.6  786.56  5161.0  788.76  5300.9  791.62  5457.2  795.50  5568.7  799.81
#Mann=5,-1,0
  4544.0    0.16       0  4995.4    0.07       0  5001.4    0.16       0
  5300.9    0.05       0  5457.2    0.16       0
Bank Sta=4995.4,5001.4
Exp/Cntr=0.3,0.1

Type RM Length L Ch R = 1,3669,408,408,408
BEGIN DESCRIPTION:
WILSON HOLLOW 8.0
END DESCRIPTION:
XS GIS Cut Line= 4
      3000093.82     10129155.32      2999913.26     10128891.43
      2999802.15     10128488.66      2999559.10     10128328.93
#Sta/Elev= 30
  4540.1  796.78  4610.1  795.37  4702.8  791.89  4878.2  782.07  4888.6  780.32
  4895.2  772.59  4900.4  772.62  4909.3  767.91  4929.6  752.42  4934.8  752.61
  4940.4  746.71  4969.1  731.31  4974.3  730.68  4981.9  724.61  4992.3  720.65
  4997.6  720.41  4999.7  720.32  5002.4  719.82  5005.7  720.32  5033.8  731.88
  5048.2  735.43  5064.9  741.79  5075.3  747.33  5082.6  763.42  5096.0  780.51
  5128.9  783.30  5210.2  785.71  5390.5  788.15  5505.4  790.99  5568.5  792.78
#Mann=7,-1,0
  4540.1    0.16       0  4997.6    0.12       0  4999.7    0.07       0
  5005.7    0.12       0  5128.9    0.16       0  5390.5    0.05       0
  5505.4    0.16       0
Bank Sta=4999.7,5005.7
Exp/Cntr=0.3,0.1

Type RM Length L Ch R = 1,3261,647,647,647
BEGIN DESCRIPTION:
WILSON HOLLOW 7.0
END DESCRIPTION:
XS GIS Cut Line= 3
      3000538.28     10128981.74      3000329.93     10128662.27
      2999545.21     10128044.21
#Sta/Elev= 30
  4379.5  798.03  4660.3  790.25  4852.8  779.81  4860.9  772.62  4867.3  752.04
  4875.4  739.27  4902.8  728.63  4939.5  725.13  4971.1  713.27  4981.1  707.52
  5007.0  705.14  5009.8  704.64  5013.0  705.14  5067.3  729.97  5081.0  732.10
  5103.1  728.31  5109.4  731.35  5117.5  729.31  5159.1  741.79  5167.2  757.40
  5173.6  749.98  5181.6  771.51  5188.0  762.09  5195.6  776.62  5202.5  779.38
  5296.4  779.72  5403.1  783.20  5418.0  783.89  5570.9  789.36  5759.8  795.37
#Mann=9,-1,0
  4379.5    0.16       0  4971.1    0.12       0  5007.0    0.07       0
  5013.0    0.12       0  5067.3    0.16       0  5296.4    0.05       0
  5403.1    0.16       0  5418.0    0.05       0  5570.9    0.16       0
Bank Sta=5007,5013
Exp/Cntr=0.3,0.1

Type RM Length L Ch R = 1,2614,297,297,297
BEGIN DESCRIPTION:
WILSON HOLLOW 6.0
END DESCRIPTION:
XS GIS Cut Line= 3
      3000753.53     10128870.55      3000420.21     10127815.04
      2999677.13     10127821.99
#Sta/Elev= 30
  4127.0  798.56  4311.2  794.13  4520.1  784.45  4729.1  773.83  4742.4  766.74
  4752.9  756.45  4773.8  750.18  4790.5  740.97  4822.8  733.36  4828.1  734.65
  4899.7  715.31  4919.8  714.70  4941.6  707.65  4952.1  703.09  4957.4  697.68
  4989.7  684.96  5001.6  684.22  5004.3  683.72  5007.6  684.22  5027.3  686.76
  5086.7  711.80  5109.4  716.36  5140.9  735.98  5182.8  741.41  5203.8  754.50
  5214.3  749.08  5221.3  752.79  5232.0  770.94  5744.6  785.76  5977.0  792.41
#Mann=7,-1,0
  4127.0    0.05       0  4311.2    0.16       0  4520.1    0.05       0
  4729.1    0.16       0  5001.6    0.07       0  5007.6    0.16       0
  5744.6     0.1       0
Bank Sta=5001.6,5007.6
Exp/Cntr=0.3,0.1

Type RM Length L Ch R = 1,2317,475,475,475
BEGIN DESCRIPTION:
WILSON HOLLOW 5.0
END DESCRIPTION:
XS GIS Cut Line= 4
      3001135.48     10128565.03      3001003.54     10128127.54
      3000524.38     10127710.88      2999496.60     10127613.66
#Sta/Elev= 30
  4213.7  794.82  4350.5  788.67  4686.0  775.50  4747.6  770.81  4783.4  755.86
  4797.0  745.78  4847.4  724.18  4896.7  715.97  4917.6  704.76  4925.2  702.53
  4953.7  685.73  4985.8  684.38  4988.6  683.88  4991.8  684.38  5038.2  685.76
  5052.4  691.87  5095.2  715.32  5109.4  717.85  5152.2  720.18  5230.0  746.69
  5250.9  755.72  5265.1  764.15  5279.4  769.48  5327.5  773.60  5427.7  776.35
  5462.2  778.57  5502.4  777.92  5697.3  781.91  6054.9  792.00  6338.0  793.90
#Mann=7,-1,0
  4213.7    0.16       0  4350.5    0.05       0  4686.0    0.16       0
  4985.8    0.07       0  4991.8    0.16       0  5427.7    0.05       0
  5697.3    0.16       0
Bank Sta=4985.8,4991.8
Exp/Cntr=0.3,0.1

Type RM Length L Ch R = 1,1842,460,460,460
BEGIN DESCRIPTION:
WILSON HOLLOW 4.0
END DESCRIPTION:
XS GIS Cut Line= 3
      3001364.64     10128565.01      3000809.10     10126419.21
      3000475.76     10126231.71
#Sta/Elev= 30
  4025.6  793.80  4238.5  785.64  4630.0  767.59  4665.4  755.05  4677.7  746.61
  4698.3  744.31  4703.3  740.68  4719.0  735.45  4797.9  727.59  4863.3  719.18
  4894.6  699.30  4935.9  685.25  5092.7  684.08  5144.6  683.97  5147.3  683.47
  5150.6  683.97  5214.8  684.54  5298.0  719.54  5310.0  725.30  5380.1  729.27
  5452.4  752.65  5473.1  765.22  5614.0  777.75  5914.1  790.77  5948.3  791.50
  6104.8  794.71  6203.8  793.98  6416.6  801.52  6606.9  807.01  6624.6  807.73
#Mann=15,-1,0
  4025.6    0.16       0  4238.5    0.05       0  4703.3     0.1       0
  4797.9    0.16       0  5092.7    0.05       0  5144.6    0.07       0
  5150.6    0.05       0  5298.0    0.16       0  5614.0     0.1       0
  5914.1    0.05       0  5948.3     0.1       0  6104.8    0.05       0
  6203.8     0.1       0  6416.6    0.05       0  6606.9     0.1       0
Bank Sta=5144.6,5150.6
Exp/Cntr=0.3,0.1

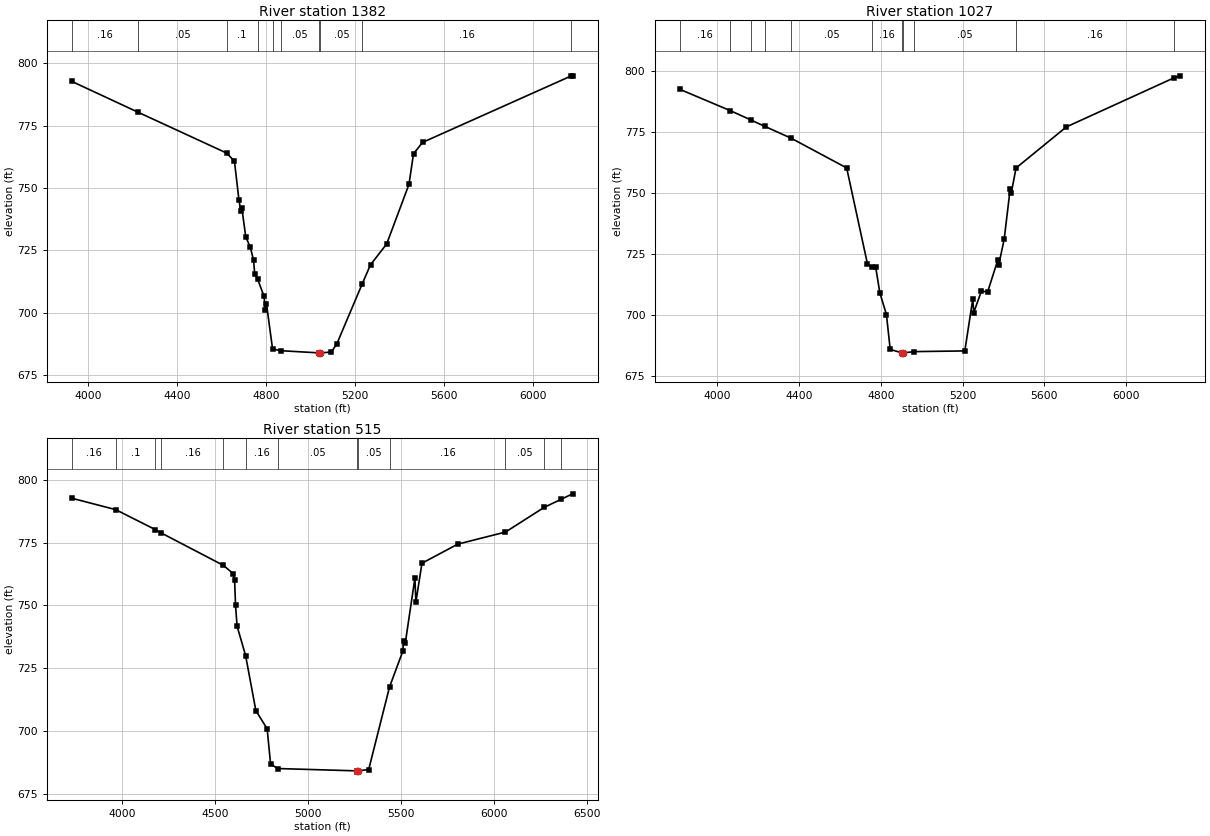
Type RM Length L Ch R = 1,1382,355,355,355
BEGIN DESCRIPTION:
WILSON HOLLOW 3.0
END DESCRIPTION:
XS GIS Cut Line= 4
      3001482.70     10128572.02      3001635.49     10127759.49
      3001503.54     10127308.10      3001670.22     10126370.55
#Sta/Elev= 30
  3927.9  792.77  4225.1  780.42  4624.3  763.98  4658.8  760.71  4679.1  745.10
  4686.9  740.95  4692.0  741.94  4709.7  730.35  4730.0  726.21  4744.5  721.11
  4750.0  715.35  4763.3  713.33  4791.9  706.49  4797.3  700.90  4802.5  703.58
  4830.0  685.43  4867.0  684.70  5038.9  683.83  5041.6  683.33  5044.9  683.83
  5094.1  684.16  5119.2  687.57  5233.2  711.64  5270.0  719.20  5342.5  727.53
  5442.7  751.46  5463.0  763.73  5503.6  768.28  6171.3  794.95  6177.2  794.99
#Mann=10,-1,0
  3927.9    0.16       0  4225.1    0.05       0  4624.3     0.1       0
  4763.3    0.16       0  4830.0     0.1       0  4867.0    0.05       0
  5038.9   0.033       0  5044.9    0.05       0  5233.2    0.16       0
  6171.3    0.05       0
Bank Sta=5038.9,5044.9
Exp/Cntr=0.3,0.1

Type RM Length L Ch R = 1,1027,512,512,512
BEGIN DESCRIPTION:
WILSON HOLLOW 2.0
END DESCRIPTION:
XS GIS Cut Line= 3
      3001718.81     10128690.08      3002045.21     10126717.82
      3001857.86     10126308.44
#Sta/Elev= 30
  3815.7  792.36  4064.4  783.57  4163.4  779.82  4231.5  777.20  4361.3  772.32
  4633.0  760.15  4734.4  720.97  4757.1  719.43  4774.9  719.56  4795.2  709.08
  4827.4  700.17  4845.9  685.90  4903.7  684.47  4906.4  683.97  4909.7  684.47
  4964.0  685.00  5210.8  685.28  5249.6  706.46  5254.6  701.00  5291.9  709.80
  5322.3  709.37  5371.6  722.37  5376.7  720.51  5403.4  731.02  5432.7  751.62
  5437.7  749.84  5461.4  760.13  5707.4  776.94  6235.5  797.08  6265.0  797.84
#Mann=11,-1,0
  3815.7    0.16       0  4064.4     0.1       0  4163.4    0.05       0
  4231.5     0.1       0  4361.3    0.05       0  4757.1    0.16       0
  4903.7   0.033       0  4909.7    0.16       0  4964.0    0.05       0
  5461.4    0.16       0  6235.5    0.05       0
Bank Sta=4903.7,4909.7
Exp/Cntr=0.3,0.1

Type RM Length L Ch R = 1,515,0,0,0
BEGIN DESCRIPTION:
WILSON HOLLOW 1.0
END DESCRIPTION:
XS GIS Cut Line= 4
      3001892.46     10128738.62      3002322.99     10128210.88
      3002468.82     10127273.38      3002156.33     10126252.59
#Sta/Elev= 30
  3727.0  792.70  3964.1  788.14  4176.9  780.22  4209.4  778.85  4544.5  765.94
  4597.5  762.60  4604.4  759.98  4609.5  749.98  4617.7  741.76  4663.6  730.06
  4718.9  708.11  4779.6  700.91  4798.2  686.83  4837.6  685.07  5262.4  684.14
  5265.2  683.64  5268.4  684.14  5326.6  684.68  5438.8  717.55  5510.0  731.71
  5515.2  735.80  5523.8  735.10  5575.5  760.91  5580.7  751.34  5613.5  766.81
  5806.2  774.41  6063.3  779.22  6271.6  789.04  6361.4  792.21  6424.4  794.44
#Mann=13,-1,0
  3727.0    0.16       0  3964.1     0.1       0  4176.9    0.05       0
  4209.4    0.16       0  4544.5    0.05       0  4663.6    0.16       0
  4837.6    0.05       0  5262.4   0.033       0  5268.4    0.05       0
  5438.8    0.16       0  6063.3    0.05       0  6271.6    0.16       0
  6361.4    0.05       0
Bank Sta=5262.4,5268.4
Exp/Cntr=0.3,0.1

Chan Stop Cuts=-1