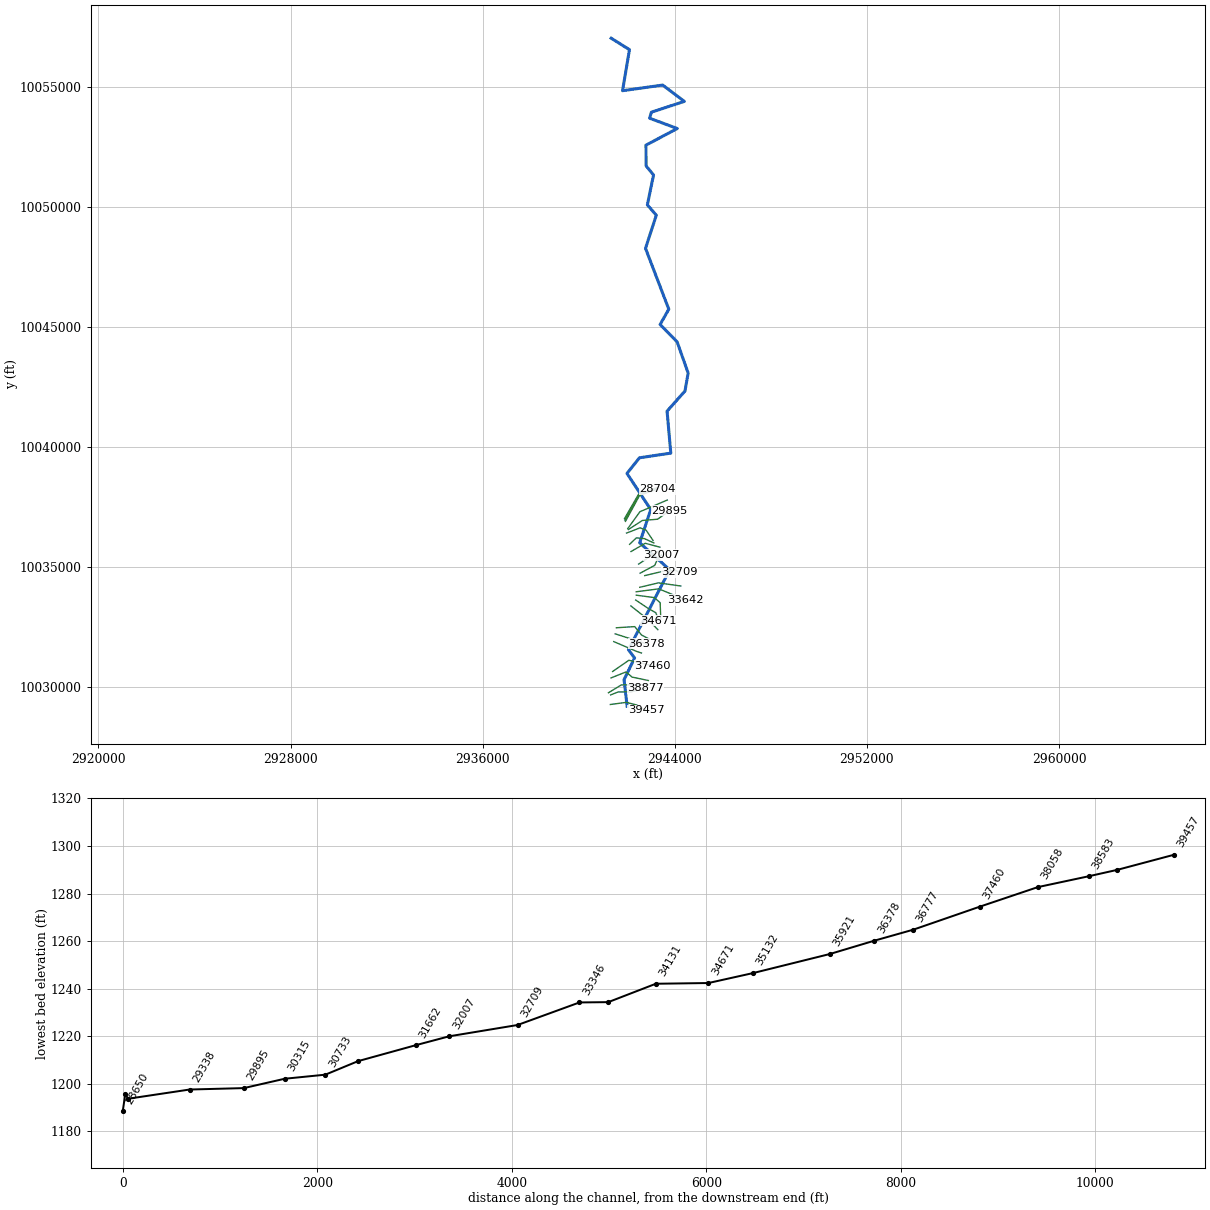
--- YEAGER CREEK.prj (project) ---

Proj Title=YEAGER CREEK Base Level Engineering
Current Plan=p01
Default Exp/Contr=0.3,0.1
English Units
Geom File=g01
Flow File=f01
Plan File=p01
Y Axis Title=Elevation
X Axis Title(PF)=Main Channel Distance
X Axis Title(XS)=Station
BEGIN DESCRIPTION:
YEAGER CREEK
END DESCRIPTION:
DSS Export Rating Curves= 0
DSS Export Rating Curve Sorted= 0
DSS Export Volume Flow Curves= 0
DXF OffsetX= 0
DXF OffsetY= 0
DXF ScaleX= 1
DXF ScaleY= 10

--- YEAGER CREEK.p01 (plan) ---

Plan Title=Multiple Run
Program Version=4.10
Short Identifier=Multiple
Geom File=g01
Flow File=f01
Subcritical Flow
K Sum by GR= 0
Std Step Tol= 0.01
Critical Tol= 0.01
Num of Std Step Trials= 20
Max Error Tol= 0.3
Flow Tol Ratio= 0.001
Split Flow NTrial= 30
Split Flow Tol= 0.02
Split Flow Ratio= 0.02
Log Output Level= 0
Friction Slope Method= 1
Unsteady Friction Slope Method= 2
Unsteady Bridges Friction Slope Method= 1
Parabolic Critical Depth
Global Vel Dist= 1 , 1 , 1
Global Log Level= 0
CheckData=True
Encroach Param=-1 ,0,0, 0
BEGIN DESCRIPTION:
Multiple Run
END DESCRIPTION:
Computation Interval=1HOUR
Output Interval=1HOUR
Run HTab= 0
Run UNet= 0
Run PostProcess= 0
Run WQNet= 0
UNET Theta= 1
UNET Theta Warmup= 1
UNET ZTol= 0.02
UNET ZSATol= 0.05
UNET MxIter= 20
UNET MaxInSteps= 0
UNET DtIC= 0
UNET DtMin= 0
UNET MaxCRTS= 20
UNET WFStab= 2
UNET SFStab= 1
UNET WFX= 1
UNET SFX= 1
UNET DSS MLevel= 4
UNET DZMax Abort= 100
UNET Convert EG Bridges= 0
UNET Use Existing IB Tables=-1
UNET Froude Reduction=False
UNET Froude Limit= 1
UNET Froude Power= 10
UNET Time Slicing=0,0, 5
UNET Junction Losses=0
Instantaneous Interval=1HOUR
Write IC File= 0
Write IC File at Sim End=0
Echo Input=False
Echo Parameters=False
Echo Output=False
Write Detailed= 0
WQ AD Non Conservative
WQ ULTIMATE=-1
WQ Max Comp Step=1HOUR
WQ Output Interval=15MIN
WQ Output Selected Increments= 0
WQ Output face flow=0
WQ Output face velocity=0
WQ Output face area=0
WQ Output face dispersion=0
WQ Output cell volume=0
WQ Output cell surface area=0
WQ Output cell continuity=0
WQ Output cumulative cell continuity=0
WQ Output face conc=0
WQ Output face dconc_dx=0
WQ Output face courant=0
WQ Output face peclet=0
WQ Output face adv mass=0
WQ Output face disp mass=0
WQ Output cell mass=0
WQ Output cell source sink temp=0
WQ Output cell source sink nsm=0
WQ Output MaxMinRange=-1
WQ Daily Max Min Mean=-1
WQ Daily Range=0
WQ Daily Time=0
WQ Create Restart=0
WQ Fixed Restart=0
WQ System Summary=0
WQ Use Fixed Temperature=0
Sorting and Armoring Iterations= 10
XS Update Threshold= 0.02
Hydraulics Update Threshold= 0.02
Energy Slope Method= 1
Volume Change Method= 0
XS Weighting Method= 0
Number of US Weighted Cross Sections= 1
Number of DS Weighted Cross Sections= 1
Upstream XS Weight=0.25
Main XS Weight=0.5
Downstream XS Weight=0.25
Number of DS XS's Weighted with US Boundary= 1
Upstream Boundary Weight= 1
Weight of XSs Associated with US Boundary= 0
Number of US XS's Weighted with DS Boundary= 1
Downstream Boundary Weight= 0.5
Weight of XSs Associated with DS Boundary= 0.5
Sediment Output Level= 4
Mass or Volume Output= 0
Output Increment Type= 1
Profile and TS Output Increment= 10
XS Output Flag= 0
XS Output Increment= 10
Disregard all LS=0
Disregard all Conn=0
Disregard all Breaches=0
Disregard all Pumps=0

--- YEAGER CREEK.f01 (steady flow) ---

Flow Title=Multiple
Program Version=4.10
Number of Profiles= 7
Profile Names=10-year,25-year,50-year,1pct_min,100-year,1pct_plu,500-year
River Rch & RM=YEAGER CREEK,Reach-1         ,39457
     982    1439    1840    1725    2332    3154    3758
River Rch & RM=YEAGER CREEK,Reach-1         ,38877
    1424    2119    2738    2589    3501    4734    5743
River Rch & RM=YEAGER CREEK,Reach-1         ,33346
    1753    2631    3420    3249    4394    5942    7280
River Rch & RM=YEAGER CREEK,Reach-1         ,29895
    2525    3850    5057    4849    6558    8869   11073
River Rch & RM=YEAGER CREEK,Reach-1         ,26644
    2764    4221    5548    5320    7195    9730   12152
River Rch & RM=YEAGER CREEK,Reach-1         ,21465
    4002    6198    8226    7956   10760   14551   18486
River Rch & RM=YEAGER CREEK,Reach-1         ,17585
    4222    6543    8689    8406   11369   15375   19545
River Rch & RM=YEAGER CREEK,Reach-1         ,14808
    4337    6717    8914    8617   11654   15760   20001
River Rch & RM=YEAGER CREEK,Reach-1         ,10003
    4358    6725    8903    8582   11606   15696   19810
River Rch & RM=YEAGER CREEK,Reach-1         ,745
    4681    7242    9604    9273   12540   16959   21472
Boundary for River Rch & Prof#=YEAGER CREEK,Reach-1         , 1
Up Type= 0
Dn Type= 3
Dn Slope=0.005
Boundary for River Rch & Prof#=YEAGER CREEK,Reach-1         , 2
Up Type= 0
Dn Type= 3
Dn Slope=0.005
Boundary for River Rch & Prof#=YEAGER CREEK,Reach-1         , 3
Up Type= 0
Dn Type= 3
Dn Slope=0.005
Boundary for River Rch & Prof#=YEAGER CREEK,Reach-1         , 4
Up Type= 0
Dn Type= 3
Dn Slope=0.005
Boundary for River Rch & Prof#=YEAGER CREEK,Reach-1         , 5
Up Type= 0
Dn Type= 3
Dn Slope=0.005
Boundary for River Rch & Prof#=YEAGER CREEK,Reach-1         , 6
Up Type= 0
Dn Type= 3
Dn Slope=0.005
Boundary for River Rch & Prof#=YEAGER CREEK,Reach-1         , 7
Up Type= 0
Dn Type= 3
Dn Slope=0.005
DSS Import GetInterval= 0
DSS Import GetPeak= 0
DSS Import FillOption= 0

--- YEAGER CREEK.g01 (geometry) ---

Geom Title=Existing Conditions
Program Version=4.10

River Reach=YEAGER CREEK    ,Reach-1
Reach XY= 30
      2942018.47     10029193.73      2941889.65     10030303.18
      2942328.87     10031208.74      2942071.16     10031552.41
      2943788.76     10034883.58      2942539.53     10036009.17
      2943000.54     10037395.76      2942010.43     10038898.11
      2942530.59     10039549.82      2943836.04     10039744.65
      2943681.16     10041492.54      2944426.86     10042332.62
      2944558.37     10043082.83      2944098.47     10044383.73
      2943390.48     10045104.79      2943752.86     10045741.62
       2942782.1     10048279.91      2943233.49     10049658.38
      2942860.24     10050089.42      2943117.36     10051335.82
      2942809.25      10051711.6      2942800.52     10052577.89
      2944105.81     10053272.03      2942951.83     10053701.29
      2943028.31     10053952.63      2944399.18     10054401.98
      2943498.32     10055082.57      2941826.23     10054847.56
      2942115.15     10056557.94      2941352.17     10057036.09

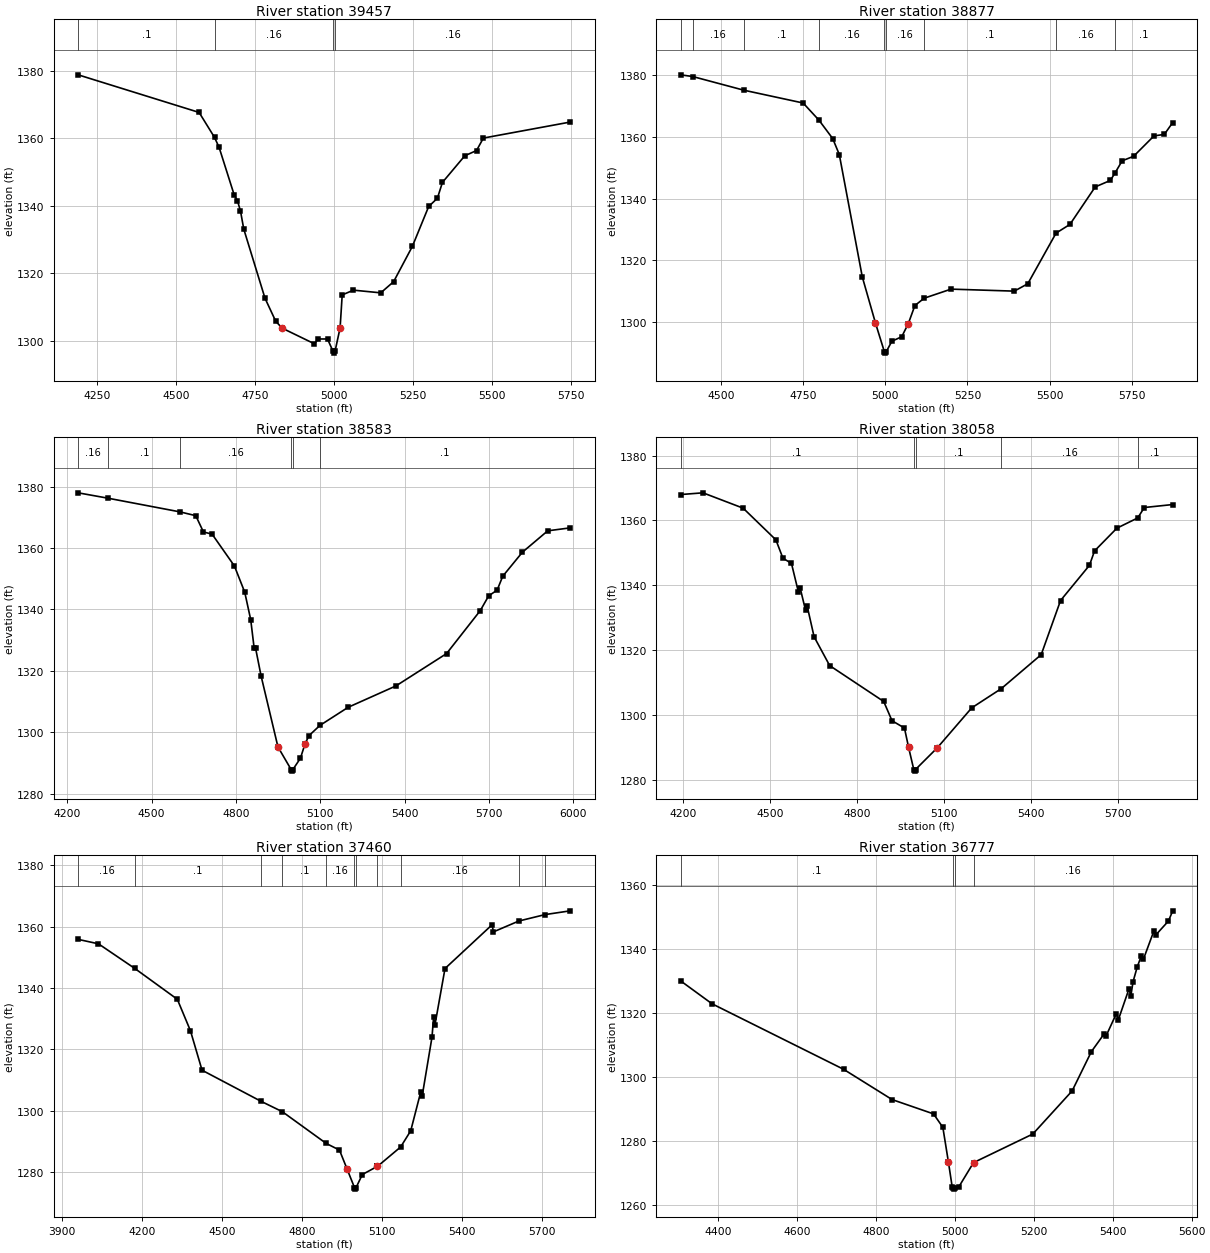
Type RM Length L Ch R = 1 ,39457   ,580,580,580
BEGIN DESCRIPTION:
YEAGER CREEK 77.0
END DESCRIPTION:
XS GIS Cut Line= 4
       2941319.1     10029269.17      2941985.73     10029359.45
      2942416.29     10029248.34      2942798.21      10029029.6
#Sta/Elev= 30
  4189.7 1378.89  4572.5 1367.73  4621.2 1360.33  4635.8 1357.35  4683.5 1343.25
  4693.6 1341.58  4703.4 1338.49  4713.8 1333.12    4781 1312.59  4814.7 1305.81
  4834.9 1303.73  4937.5 1299.06  4949.2  1300.5  4978.8  1300.5  4996.5  1296.8
  4999.2  1296.3  5002.5  1296.8 5018.64 1303.78  5025.3 1313.57  5060.8 1314.99
  5147.3 1314.19    5188  1317.5  5247.4 1327.99    5299 1339.82  5326.6 1342.27
  5342.5 1346.97  5413.3 1354.87  5450.4 1356.42    5472 1360.12  5747.2 1364.88
#Mann= 4 ,-1 , 0
  4189.7      .1       0  4621.2     .16       0  4996.5     .07       0
  5002.5     .16       0
Bank Sta=4834.9,5018.64
XS Rating Curve= 0 ,0
Exp/Cntr=0.3,0.1

Type RM Length L Ch R = 1 ,38877   ,294,294,294
BEGIN DESCRIPTION:
YEAGER CREEK 76.0
END DESCRIPTION:
XS GIS Cut Line= 4
      2941329.45     10029668.46      2941645.46     10029793.48
      2942180.18     10029793.48      2942783.92     10029946.14
#Sta/Elev= 30
  4377.4 1380.04  4414.2 1379.49  4569.7 1375.07  4750.2 1370.92  4798.6 1365.34
  4840.2 1359.41  4860.2 1354.26  4930.2 1314.64  4970.2 1299.75  4997.2 1290.49
    5000 1289.99  5003.2 1290.49  5020.2 1293.84  5050.2  1295.3  5070.2 1299.55
  5090.2 1305.39  5118.4 1307.76  5200.2  1310.7  5392.6 1310.05  5433.6 1312.43
  5519.7 1328.83  5561.9 1331.64  5638.8 1343.77  5684.9 1345.87  5698.5 1348.19
  5720.8 1352.22  5755.6 1353.68  5817.5 1360.27    5849 1360.77  5874.7 1364.61
#Mann= 9 ,-1 , 0
  4377.4      .1       0  4414.2     .16       0  4569.7      .1       0
  4798.6     .16       0  4997.2     .07       0  5003.2     .16       0
  5118.4      .1       0  5519.7     .16       0  5698.5      .1       0
Bank Sta=4970.2,5070.2
XS Rating Curve= 0 ,0
Exp/Cntr=0.3,0.1

Type RM Length L Ch R = 1 ,38583   ,525,525,525
BEGIN DESCRIPTION:
YEAGER CREEK 75.0
END DESCRIPTION:
XS GIS Cut Line= 3
      2941239.24     10029758.77      2941773.93     10030085.14
      2942898.88     10030092.09
#Sta/Elev= 30
  4238.6 1377.97  4346.5 1376.19  4601.6 1371.75  4657.2 1370.52  4684.4 1365.22
  4715.3  1364.5  4794.7 1354.13  4831.4 1345.59  4852.7 1336.62  4864.8 1327.44
  4869.8 1327.44  4889.6  1318.3  4949.6 1295.18  4996.6 1287.79  4999.3 1287.29
  5002.6 1287.79  5029.6  1291.5 5045.45 1296.02  5059.6 1298.82  5098.9 1302.18
  5199.6  1308.1  5369.6 1315.06  5549.6 1325.59  5669.6  1339.6  5699.6 1344.41
  5729.6 1346.27  5749.6  1350.8  5819.6 1358.63  5909.6 1365.59    5990 1366.56
#Mann= 6 ,-1 , 0
  4238.6     .16       0  4346.5      .1       0  4601.6     .16       0
  4996.6     .07       0  5002.6     .16       0  5098.9      .1       0
Bank Sta=4949.6,5045.45
XS Rating Curve= 0 ,0
Exp/Cntr=0.3,0.1

Type RM Length L Ch R = 1 ,38058   ,598,598,598
BEGIN DESCRIPTION:
YEAGER CREEK 74.0
END DESCRIPTION:
XS GIS Cut Line= 4
      2941346.85     10030376.81      2941968.37     10030626.81
      2942225.32     10030411.53      2942902.38     10030269.17
#Sta/Elev= 30
  4191.5 1367.98  4268.7 1368.51  4407.2 1363.78  4520.1 1354.01  4544.3 1348.36
  4573.8 1346.75    4598 1337.82  4603.4 1339.31  4622.2 1332.34  4627.6 1333.72
  4651.8 1324.14  4705.5 1315.25  4891.9 1304.18  4920.5 1298.25  4963.4 1295.99
  4977.7 1290.01  4995.5 1283.21  4998.3 1282.71  5001.5 1283.21  5076.6  1289.9
  5195.4 1302.22  5297.1 1308.13  5434.9 1318.62  5501.6 1335.31  5601.3 1346.17
  5618.8  1350.6  5695.8 1357.61  5767.7 1360.77  5790.4 1363.98  5888.5  1364.9
#Mann= 5 ,-1 , 0
  4191.5      .1       0  4995.5     .07       0  5001.5      .1       0
  5297.1     .16       0  5767.7      .1       0
Bank Sta=4977.7,5076.6
XS Rating Curve= 0 ,0
Exp/Cntr=0.3,0.1

Type RM Length L Ch R = 1 ,37460   ,683,683,683
BEGIN DESCRIPTION:
YEAGER CREEK 73.0
END DESCRIPTION:
XS GIS Cut Line= 3
      2941412.79     10030644.15       2942089.9     10031112.92
      2943082.96     10030883.75
#Sta/Elev= 30
  3962.1 1355.84  4038.2 1354.39  4173.8 1346.39  4333.4 1336.32  4382.5 1326.08
    4426 1313.21  4646.9 1303.08  4726.7 1299.69  4890.8 1289.36  4940.5 1287.19
  4968.9 1281.03  4996.7 1274.97  4999.4 1274.47  5002.7 1274.97    5026 1279.22
  5081.8 1281.86  5082.8 1281.87  5169.6 1288.21  5207.3 1293.48  5244.9 1306.18
  5250.1 1304.77    5287 1324.03  5292.8 1330.44    5298 1327.98  5335.6 1346.34
  5511.8 1360.59  5516.9 1358.28    5612 1361.82  5710.6 1363.92  5804.8 1365.14
#Mann= 11 ,-1 , 0
  3962.1     .16       0  4173.8      .1       0  4646.9     .16       0
  4726.7      .1       0  4890.8     .16       0  4996.7     .07       0
  5002.7     .16       0  5082.8      .1       0  5169.6     .16       0
    5612      .1       0  5710.6     .16       0
Bank Sta=4968.9,5081.8
XS Rating Curve= 0 ,0
Exp/Cntr=0.3,0.1

Type RM Length L Ch R = 1 ,36777   ,399,399,399
BEGIN DESCRIPTION:
YEAGER CREEK 72.0
END DESCRIPTION:
XS GIS Cut Line= 3
      2941461.39     10031890.71      2942405.87     10031484.45
      2942613.87     10031415.11
#Sta/Elev= 30
  4304.7 1329.98  4384.4  1322.8  4717.6 1302.32  4840.8 1292.83  4945.8 1288.35
  4969.4 1284.14 4983.52 1273.27  4992.9 1265.63  4995.3 1265.31  4998.1 1264.81
  5001.3 1265.31  5009.1 1265.36  5047.1  1273.1  5197.5 1282.06  5297.1 1295.55
  5345.9 1307.85  5377.5 1313.27  5382.8 1312.67  5409.1 1319.72  5414.4 1317.88
  5440.8 1327.34    5446 1325.39  5451.5 1329.72  5462.1 1334.36  5472.4 1337.77
  5477.7 1336.73    5504 1345.51  5509.3 1344.37  5540.9 1348.66  5552.1 1351.89
#Mann= 4 ,-1 , 0
  4304.7      .1       0  4995.3     .07       0  5001.3      .1       0
  5047.1     .16       0
Bank Sta=4983.52,5047.1
XS Rating Curve= 0 ,0
Exp/Cntr=0.3,0.1

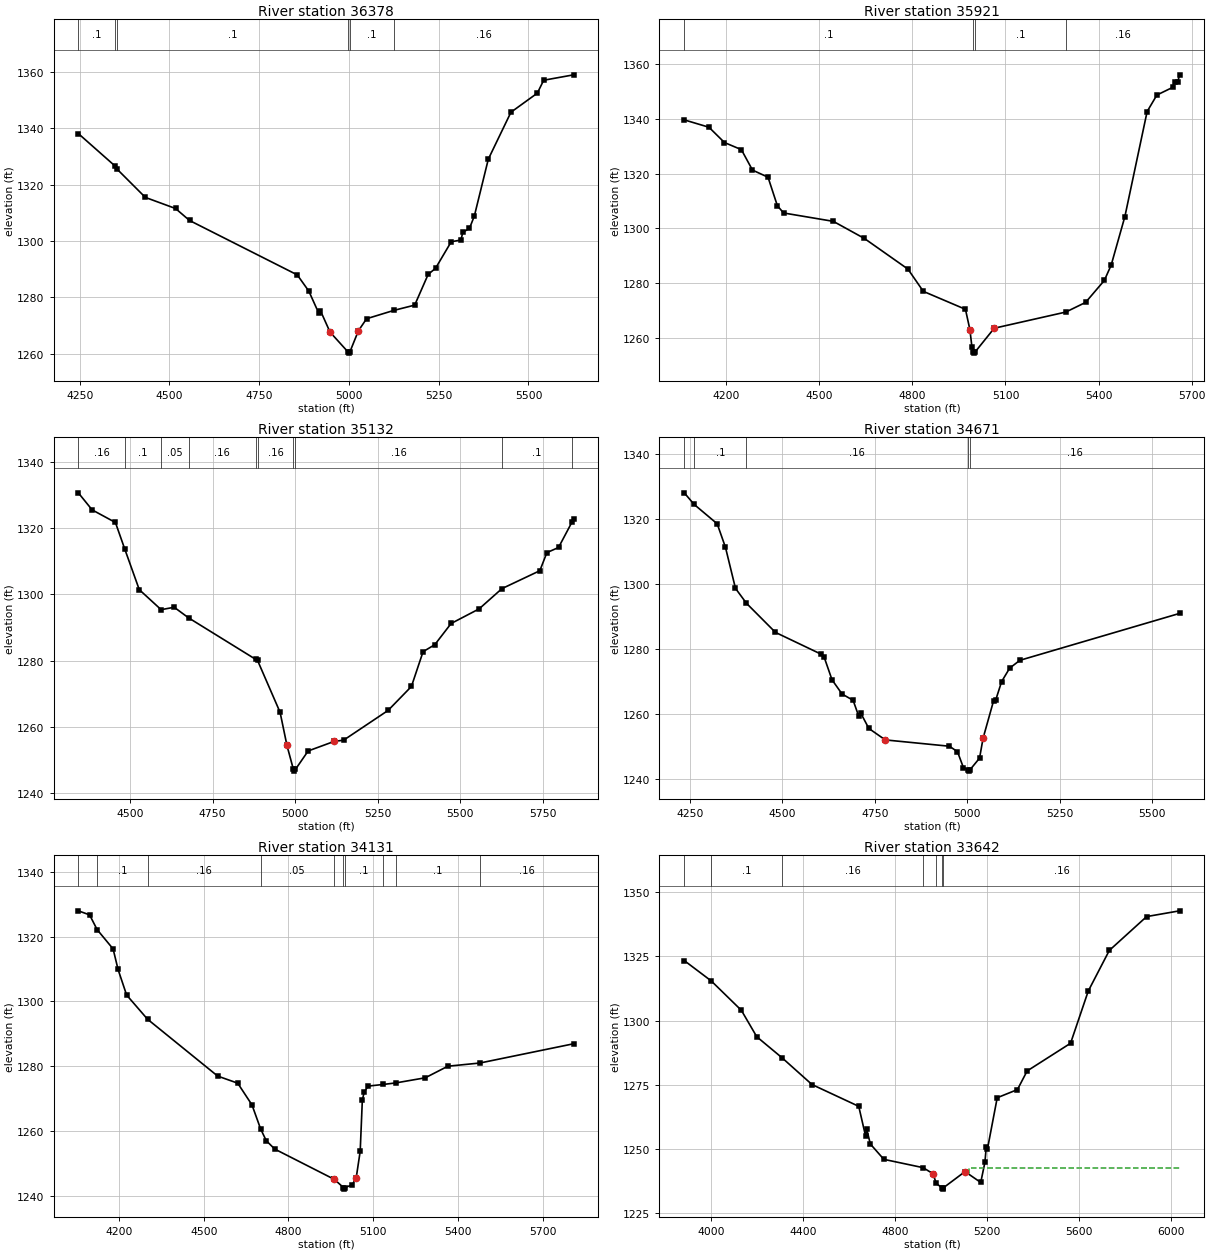
Type RM Length L Ch R = 1 ,36378   ,457,457,457
BEGIN DESCRIPTION:
YEAGER CREEK 71.0
END DESCRIPTION:
XS GIS Cut Line= 2
      2941520.47     10032213.61      2942834.91     10031793.96
#Sta/Elev= 30
  4246.1  1338.1  4347.2 1326.72  4354.1 1325.47  4432.9 1315.44  4516.9 1311.51
  4555.9 1307.26    4856 1287.96  4888.2  1282.2  4915.2 1274.56  4920.4  1275.3
  4947.3 1267.66  4996.8  1260.7  4999.6  1260.2  5002.8  1260.7 5026.36 1268.14
  5049.1  1272.4  5125.3 1275.37  5183.1 1277.23  5220.6 1288.13  5241.2  1290.3
  5284.9 1299.72  5311.9 1300.32  5317.1 1303.05  5335.7 1304.46  5349.3 1308.85
  5388.2 1329.02  5451.2 1345.66  5524.7 1352.43  5542.4 1357.01  5625.9 1358.93
#Mann= 6 ,-1 , 0
  4246.1      .1       0  4347.2     .05       0  4354.1      .1       0
  4996.8     .07       0  5002.8      .1       0  5125.3     .16       0
Bank Sta=4947.3,5026.36
XS Rating Curve= 0 ,0
Exp/Cntr=0.3,0.1

Type RM Length L Ch R = 1 ,35921   ,789,789,789
BEGIN DESCRIPTION:
YEAGER CREEK 70.0
END DESCRIPTION:
XS GIS Cut Line= 4
      2941569.02     10032467.08      2942332.96      10032515.7
      2942617.68       10032165.      2942953.22     10031988.58
#Sta/Elev= 30
  4064.9 1339.56  4144.5 1336.88  4194.6  1331.3    4249 1328.72  4284.8 1321.27
  4334.9 1318.67    4365 1308.29    4385 1305.65  4545.3  1302.6  4645.5 1296.36
  4785.8  1285.2  4835.3  1277.1  4971.1 1270.56  4985.4 1263.18  4991.9 1256.92
  4996.8  1255.1  4999.6  1254.6  5002.8  1255.1  5063.8 1263.67  5294.5 1269.56
  5358.2 1273.07  5418.6 1281.06  5440.8 1286.69  5484.8 1304.31  5556.6 1342.61
    5588 1348.61  5639.1 1351.41  5644.8 1353.49  5655.5 1353.51  5661.2 1355.97
#Mann= 4 ,-1 , 0
  4064.9      .1       0  4996.8     .07       0  5002.8      .1       0
  5294.5     .16       0
Bank Sta=4985.4,5063.8
XS Rating Curve= 0 ,0
Exp/Cntr=0.3,0.1

Type RM Length L Ch R = 1 ,35132   ,461,461,461
BEGIN DESCRIPTION:
YEAGER CREEK 68.0
END DESCRIPTION:
XS GIS Cut Line= 3
      2942173.25      10033376.8      2942846.84     10032845.56
      2943297.49     10032387.99
#Sta/Elev= 30
  4343.5 1330.64  4385.4 1325.49  4455.9 1321.68  4483.6 1313.82  4528.1  1301.4
  4594.3 1295.35  4633.9 1296.08  4677.3 1292.89    4881 1280.33  4886.3 1280.03
  4954.6 1264.34  4975.4 1254.33  4994.9 1247.09  4997.6 1246.59  5000.9 1247.09
  5039.5 1252.68  5118.1 1255.56    5147 1255.94  5281.6 1264.92  5352.3 1272.16
  5387.6 1282.67    5423 1284.77  5472.5 1291.18  5557.3 1295.59  5626.3  1301.7
  5741.2 1307.12  5762.5 1312.58  5797.8 1314.13  5837.9 1321.68  5843.6 1322.86
#Mann= 10 ,-1 , 0
  4343.5     .16       0  4483.6      .1       0  4594.3     .05       0
  4677.3     .16       0    4881      .1       0  4886.3     .16       0
  4994.9     .07       0  5000.9     .16       0  5626.3      .1       0
  5837.9     .16       0
Bank Sta=4975.4,5118.1
XS Rating Curve= 0 ,0
Exp/Cntr=0.3,0.1

Type RM Length L Ch R = 1 ,34671   ,540,540,540
BEGIN DESCRIPTION:
YEAGER CREEK 67.0
END DESCRIPTION:
XS GIS Cut Line= 4
      2942374.66     10033623.31      2942916.29     10033258.75
      2943211.43     10033095.56      2943332.95      10032769.2
#Sta/Elev= 30
    4235 1328.16  4261.7 1324.59    4324 1318.62  4346.4 1311.35  4373.4 1298.72
    4403 1294.13  4481.4 1285.15  4604.3 1278.46  4613.3 1277.43  4634.3 1270.53
  4661.5 1266.15  4691.3 1264.21  4706.3 1259.37  4712.3 1260.18  4733.8 1255.54
  4778.2 1252.01  4951.6 1250.06  4973.3 1248.37  4989.4 1243.44  5001.7 1242.89
  5004.4 1242.39  5007.7 1242.89  5032.9 1246.39 5042.39 1252.52  5070.7 1264.03
  5076.4 1264.24  5092.5 1269.98  5114.2 1274.12  5141.8 1276.54  5573.4    1291
#Mann= 5 ,-1 , 0
    4235     .16       0  4261.7      .1       0    4403     .16       0
  5001.7     .07       0  5007.7     .16       0
Bank Sta=4778.2,5042.39
XS Rating Curve= 0 ,0
Exp/Cntr=0.3,0.1

Type RM Length L Ch R = 1 ,34131   ,489,489,489
BEGIN DESCRIPTION:
YEAGER CREEK 66.0
END DESCRIPTION:
XS GIS Cut Line= 4
      2942398.92     10033824.73       2943152.4     10033724.03
      2943391.98     10033512.23      2943419.76     10032838.66
#Sta/Elev= 30
  4055.9 1327.93  4095.8 1326.69  4122.5 1322.14  4179.1 1316.18  4196.7 1309.84
    4227 1301.95    4301  1294.5  4549.4 1276.96  4620.4 1274.77  4670.9 1268.07
  4701.4 1260.68  4721.3 1257.05  4751.6 1254.44  4960.2  1245.2  4962.1 1245.14
  4994.7 1242.59  4997.4 1242.09  5000.7 1242.59  5025.7 1243.41  5039.9 1245.54
  5054.1 1253.76  5061.7 1269.56  5068.4 1272.08  5082.6 1273.87    5135 1274.37
  5180.2 1274.85  5284.5 1276.43  5364.5    1280  5478.2 1280.99    5810 1286.93
#Mann= 10 ,-1 , 0
  4055.9     .16       0  4122.5      .1       0    4301     .16       0
  4701.4     .05       0  4960.2      .1       0  4994.7     .07       0
  5000.7      .1       0    5135     .16       0  5180.2      .1       0
  5478.2     .16       0
Bank Sta=4962.1,5039.9
XS Rating Curve= 0 ,0
Exp/Cntr=0.3,0.1

Type RM Length L Ch R = 1 ,33642   ,296,296,296
BEGIN DESCRIPTION:
YEAGER CREEK 65.0
END DESCRIPTION:
XS GIS Cut Line= 3
      2942395.49     10033967.09      2943336.43     10034088.61
      2944450.99     10033626.82
#Sta/Elev= 30
  3883.6 1323.36  4001.2 1315.42  4132.1 1303.99  4199.2 1293.69  4309.1 1285.51
  4439.5 1275.08  4642.8  1266.6  4672.6 1254.99  4677.6 1257.68  4693.2 1251.94
    4752 1245.96  4922.8 1242.72  4966.3 1240.34  4979.6 1236.64  5004.8 1234.86
  5007.5 1234.36  5010.8 1234.86  5105.2 1241.19  5173.6 1236.96  5191.8 1244.81
  5197.5 1250.69  5202.9 1250.01  5245.3 1269.95  5333.2 1273.12  5375.5 1280.38
  5564.4 1291.16  5641.5 1311.51    5733 1327.31  5895.4 1340.49  6038.8 1342.73
#Mann= 7 ,-1 , 0
  3883.6     .16       0  4001.2      .1       0  4309.1     .16       0
  4922.8     .05       0  4979.6     .16       0  5004.8     .07       0
  5010.8     .16       0
#XS Ineff= 2 , 0
                         5122.73         1242.78
Permanent Ineff=
       T       T
Bank Sta=4966.3,5105.2
XS Rating Curve= 0 ,0
Exp/Cntr=0.3,0.1

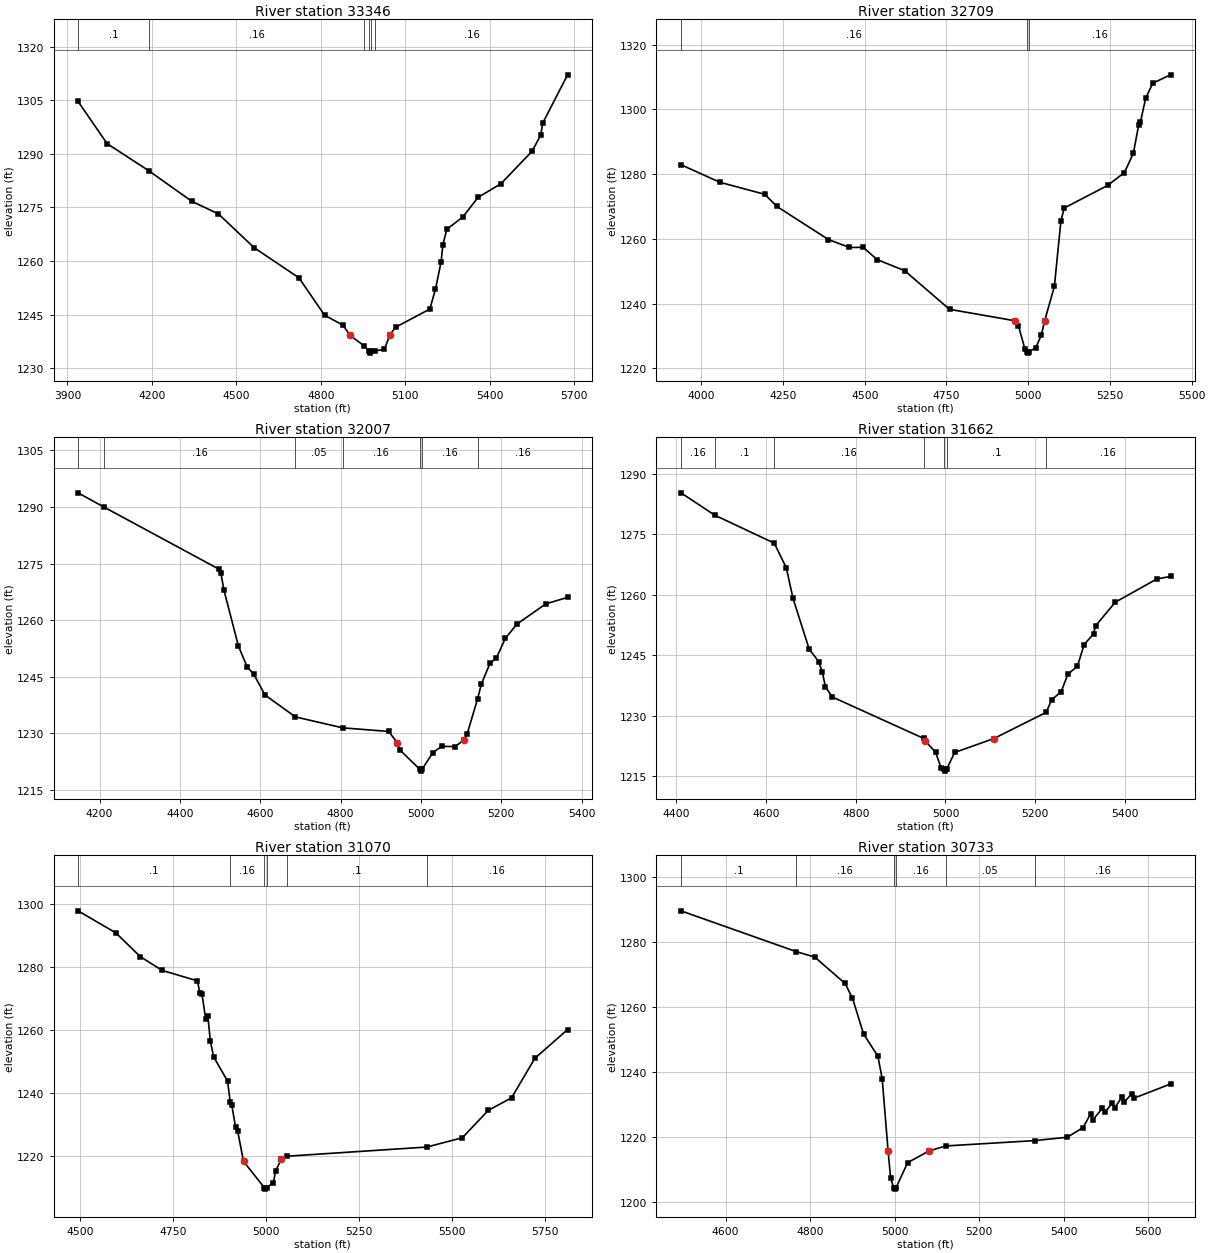
Type RM Length L Ch R = 1 ,33346   ,637,637,637
BEGIN DESCRIPTION:
YEAGER CREEK 64.0
END DESCRIPTION:
XS GIS Cut Line= 3
      2942544.72     10034154.58      2943322.54     10034338.61
      2944253.14     10034206.66
#Sta/Elev= 30
  3937.8 1304.66    4041 1292.85  4189.5 1285.24    4342  1276.7  4436.8 1273.17
  4563.6 1263.72  4722.6  1255.3  4813.8 1244.83  4879.1 1242.05  4904.7 1239.17
  4955.4 1236.19  4972.4 1234.73  4975.1 1234.23  4978.4 1234.73  4994.1 1234.89
  5026.1 1235.27  5046.1  1239.4  5066.3 1241.49  5187.5 1246.55  5207.7 1252.11
  5227.9 1259.86  5233.9 1264.54  5248.1 1268.89  5304.9 1272.32  5359.2 1277.82
    5440  1281.6  5551.1 1290.72  5581.4 1295.21  5588.7 1298.58    5677 1312.09
#Mann= 6 ,-1 , 0
  3937.8      .1       0  4189.5     .16       0  4955.4     .05       0
  4972.4     .07       0  4978.4     .05       0  4994.1     .16       0
Bank Sta=4904.7,5046.1
XS Rating Curve= 0 ,0
Exp/Cntr=0.3,0.1

Type RM Length L Ch R = 1 ,32709   ,702,702,702
BEGIN DESCRIPTION:
YEAGER CREEK 63.0
END DESCRIPTION:
XS GIS Cut Line= 4
      2942749.62      10034640.7      2943586.43     10034838.61
      2944044.76     10034859.45      2944200.98     10034772.66
#Sta/Elev= 30
  3937.9  1282.9  4057.3 1277.47  4194.4 1273.76  4231.5 1270.01  4388.8 1259.81
  4453.2 1257.36  4495.5 1257.38  4537.7 1253.63  4622.3 1250.18  4759.4 1238.26
    4960 1234.72    4970 1233.26    4990 1225.98    4997 1225.24  4999.8 1224.74
    5003 1225.24  5022.8 1226.37  5040.1 1230.21  5050.1 1234.63  5080.1 1245.32
  5100.1 1265.57  5110.2 1269.53  5243.1 1276.51  5294.3 1280.48  5321.8 1286.46
  5337.8  1295.1  5343.5 1296.19  5359.6 1303.51  5381.3 1308.08  5435.3 1310.65
#Mann= 3 ,-1 , 0
  3937.9     .16       0    4997     .07       0    5003     .16       0
Bank Sta=4960,5050.1
XS Rating Curve= 0 ,0
Exp/Cntr=0.3,0.1

Type RM Length L Ch R = 1 ,32007   ,345,345,345
BEGIN DESCRIPTION:
YEAGER CREEK 61.0
END DESCRIPTION:
XS GIS Cut Line= 4
      2942558.68     10034741.41      2943166.29     10035067.78
      2943312.12     10035387.23      2943450.98     10035498.31
#Sta/Elev= 30
  4146.3 1293.73    4211 1289.95  4496.1 1273.57  4501.8  1272.6  4509.3 1268.06
  4545.6 1253.14  4567.5 1247.57  4583.8  1245.7  4611.5 1240.19  4687.3 1234.37
    4805 1231.47  4919.5 1230.51  4941.5  1227.5  4948.3 1225.53  4996.9  1220.5
  4999.6    1220  5002.9  1220.5  5029.4 1224.87  5051.4 1226.56  5084.4  1226.5
  5106.4 1228.17    5115 1229.84    5141 1239.15  5150.4 1243.07  5172.3 1248.68
  5187.2 1249.85  5210.1 1255.18  5238.9 1258.95  5310.6  1264.3    5365 1266.03
#Mann= 7 ,-1 , 0
  4146.3      .1       0    4211     .16       0  4687.3     .05       0
    4805     .16       0  4996.9     .07       0  5002.9     .16       0
    5141     .16       0
Bank Sta=4941.5,5106.4
XS Rating Curve= 0 ,0
Exp/Cntr=0.3,0.1

Type RM Length L Ch R = 1 ,31662   ,592,592,592
BEGIN DESCRIPTION:
YEAGER CREEK 60.0
END DESCRIPTION:
XS GIS Cut Line= 3
      2942496.13     10035119.85      2943266.98     10035633.75
       2943422.4     10035689.01
#Sta/Elev= 30
  4410.3 1285.31  4485.7 1279.76  4618.3 1272.82  4645.1 1266.73  4660.1 1259.14
  4696.1 1246.56  4717.2 1243.44  4725.6  1240.8  4732.2 1237.23  4747.2 1234.68
  4951.2 1224.38  4954.5  1223.8    4978 1220.93  4990.6 1216.97  4996.6 1216.75
  4999.4 1216.25  5002.6 1216.75  5020.6 1220.88  5107.8 1224.33  5224.3 1230.82
    5237 1233.96    5258 1235.98    5273 1240.33  5294.1 1242.25  5309.1 1247.63
  5330.1 1250.32  5334.6 1252.29  5378.5 1258.16    5471 1263.92  5501.7 1264.56
#Mann= 7 ,-1 , 0
  4410.3     .16       0  4485.7      .1       0  4618.3     .16       0
  4951.2      .1       0  4996.6     .07       0  5002.6      .1       0
  5224.3     .16       0
Bank Sta=4954.5,5107.8
XS Rating Curve= 0 ,0
Exp/Cntr=0.3,0.1

Type RM Length L Ch R = 1 ,31070   ,337,337,337
BEGIN DESCRIPTION:
YEAGER CREEK 59.0
END DESCRIPTION:
XS GIS Cut Line= 3
      2942180.18     10035644.17      2942773.93     10035987.92
      2943384.26     10035824.93
#Sta/Elev= 30
  4493.6  1297.9  4595.6 1290.89  4660.8  1283.4  4719.6 1279.01  4815.2 1275.66
  4821.5 1271.81  4827.3 1271.44  4837.2 1263.65    4843 1264.58  4849.8 1256.57
  4858.8 1251.53    4896 1243.87  4903.4 1237.22  4907.6 1236.15  4917.6 1229.31
  4923.4 1227.96  4939.1 1218.36    4995 1210.06  4997.7 1209.56    5001 1210.06
  5019.5 1211.56  5025.3  1215.3    5041 1219.11  5056.2 1220.01  5432.7 1222.92
  5528.2 1225.88    5598 1234.57  5660.5 1238.53  5723.5 1251.11  5811.4 1260.21
#Mann= 6 ,-1 , 0
  4493.6      .1       0  4903.4     .16       0    4995     .07       0
    5001     .16       0  5056.2      .1       0  5432.7     .16       0
Bank Sta=4939.1,5041
XS Rating Curve= 0 ,0
Exp/Cntr=0.3,0.1

Type RM Length L Ch R = 1 ,30733   ,418,418,418
BEGIN DESCRIPTION:
YEAGER CREEK 58.0
END DESCRIPTION:
XS GIS Cut Line= 4
      2942119.82     10035944.36      2942401.07     10036212.59
       2942734.4     10036183.94      2943130.23     10036001.65
#Sta/Elev= 30
  4494.2 1289.45    4767 1276.91  4810.9 1275.23  4882.8 1267.11  4900.3 1262.58
  4926.6 1251.57  4960.5 1244.71  4970.6 1237.83 4984.66 1215.52  4990.6 1207.28
  4997.7 1204.36  5000.4 1203.86  5003.7 1204.36  5030.8    1212    5081 1215.57
    5121 1217.14  5331.5 1218.78    5409 1219.82  5446.3 1222.81  5463.8 1226.94
  5469.3 1225.18  5492.2 1228.75  5497.7 1227.48  5515.2 1230.26  5520.7 1228.76
  5538.2 1232.19  5543.7  1230.6  5561.1 1233.17  5566.6 1231.83  5653.2 1236.19
#Mann= 6 ,-1 , 0
  4494.2      .1       0    4767     .16       0  4997.7     .07       0
  5003.7     .16       0    5121     .05       0  5331.5     .16       0
Bank Sta=4984.66,5081
XS Rating Curve= 0 ,0
Exp/Cntr=0.3,0.1

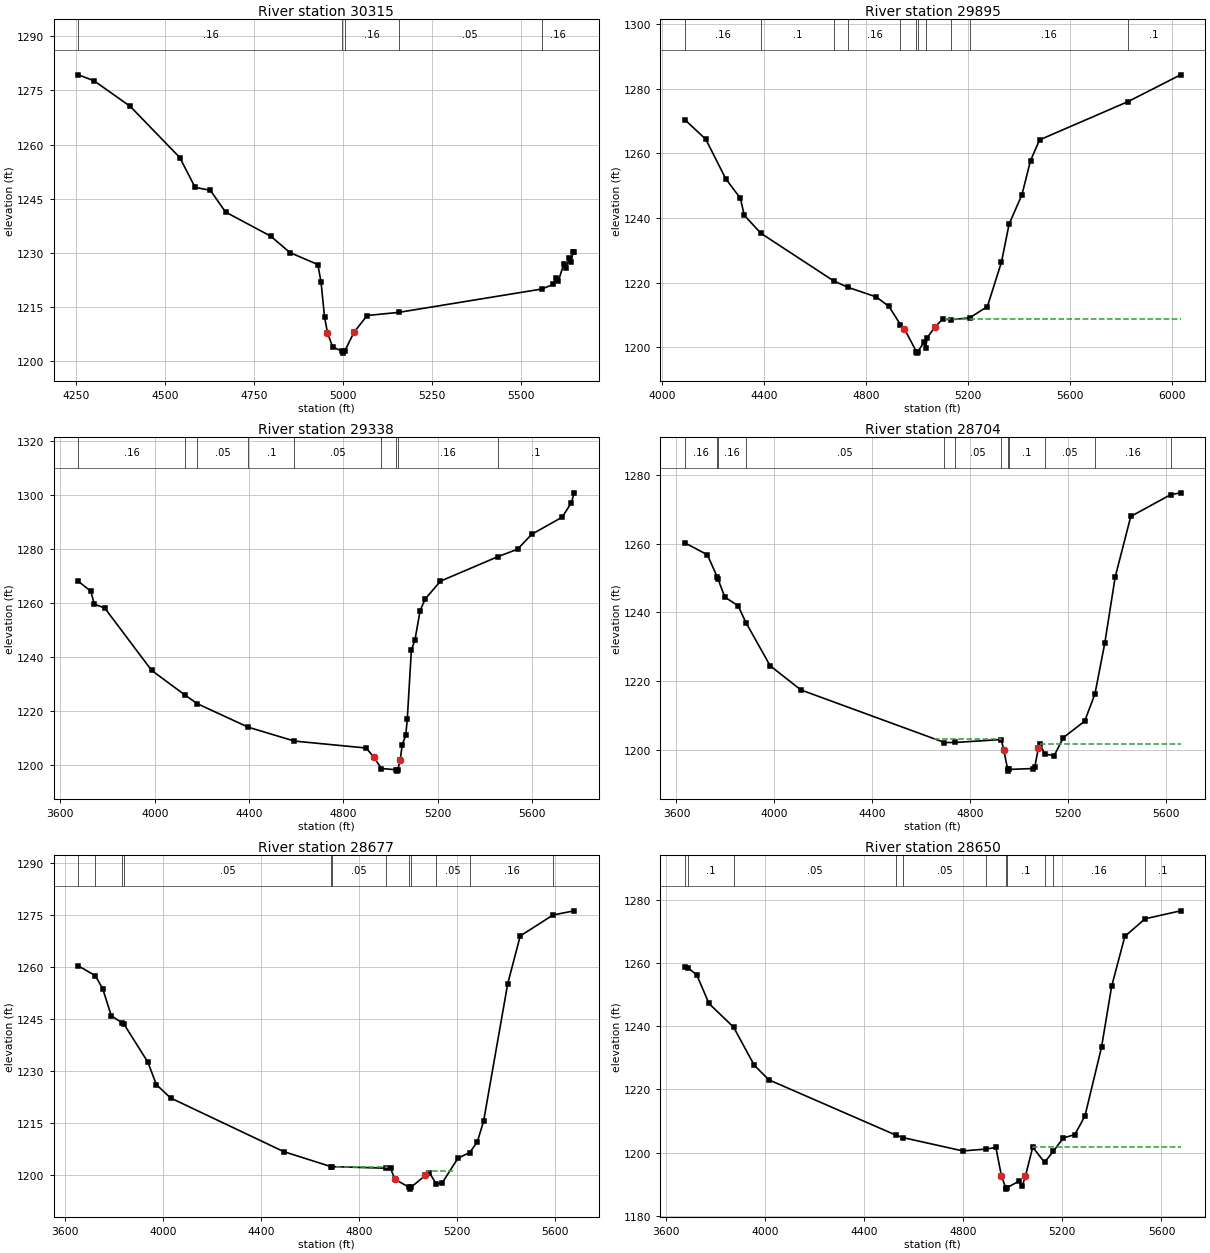
Type RM Length L Ch R = 1 ,30315   ,420,420,420
BEGIN DESCRIPTION:
Mapping XS 9807bf89
END DESCRIPTION:
XS GIS Cut Line= 4
      2941992.22     10036413.11      2942559.92     10036631.86
      2942809.92      10036530.3      2943098.96     10036103.25
#Sta/Elev= 30
  4256.8 1279.32  4300.6 1277.69  4402.8 1270.57  4542.1 1256.37    4585 1248.12
  4627.9  1247.3  4670.7 1241.27  4797.4 1234.59    4852 1230.02  4930.2 1226.71
  4939.2 1221.77  4948.9 1212.19 4957.27 1207.81  4971.6 1203.85  4999.4 1202.65
  5002.2 1202.15  5005.4 1202.65  5031.9 1207.96  5068.7 1212.58  5157.3 1213.45
    5560 1219.93  5591.6  1221.2  5600.5 1222.91  5606.5 1222.21  5621.5 1226.84
  5627.5 1225.71  5636.4 1228.41  5642.5 1227.37  5647.4 1230.25  5650.7 1230.25
#Mann= 5 ,-1 , 0
  4256.8     .16       0  4999.4     .07       0  5005.4     .16       0
  5157.3     .05       0    5560     .16       0
Bank Sta=4957.27,5031.9
XS Rating Curve= 0 ,0
Exp/Cntr=0.3,0.1

Type RM Length L Ch R = 1 ,29895   ,557,557,557
BEGIN DESCRIPTION:
Mapping XS 30ab6386
END DESCRIPTION:
XS GIS Cut Line= 4
      2942069.44     10036560.66      2942651.07     10036938.28
      2943284.75     10036990.37      2943788.18     10037346.24
#Sta/Elev= 30
  4089.8 1270.37  4172.1 1264.32  4250.6 1252.09  4307.9 1246.09  4323.1 1240.83
  4388.3 1235.27  4674.5 1220.51  4731.7 1218.52  4840.9  1215.6    4891 1212.64
  4936.1 1207.06  4951.2 1205.77  4998.4 1198.72  5001.1 1198.22  5004.4 1198.72
  5029.7 1201.72  5034.7  1199.8  5041.5 1203.04  5071.6 1206.33  5101.7 1208.72
  5135.1 1208.55  5207.9 1209.14  5277.2 1212.61  5332.5 1226.36  5362.6 1238.12
  5412.8 1247.16  5446.5  1257.7  5482.1 1264.13  5828.5 1275.93  6035.6 1284.23
#Mann= 11 ,-1 , 0
  4089.8     .16       0  4388.3      .1       0  4674.5     .05       0
  4731.7     .16       0  4936.1     .05       0  4998.4    .035       0
  5004.4     .05       0  5034.7     .16       0  5135.1      .1       0
  5207.9     .16       0  5828.5      .1       0
#XS Ineff= 2 , 0
                         5112.22         1208.84
Permanent Ineff=
       T       T
Bank Sta=4951.2,5071.6
XS Rating Curve= 0 ,0
Exp/Cntr=0.3,0.1

Type RM Length L Ch R = 1 ,29338   ,634,634,634
BEGIN DESCRIPTION:
YEAGER CREEK 57.0
END DESCRIPTION:
XS GIS Cut Line= 3
      2942044.79     10036602.54      2942551.71     10037303.89
      2943689.06     10037789.35
#Sta/Elev= 30
  3676.2 1268.06  3729.2 1264.38  3743.9 1259.58    3788 1258.17  3986.8 1235.02
  4127.8 1225.89  4181.1 1222.62  4396.6 1213.92  4592.1 1208.78  4896.9 1206.19
  4929.5 1202.71  4961.2 1198.59  5024.3 1198.12  5027.1 1197.62  5030.3 1198.12
  5040.8 1201.71  5049.1 1207.32  5064.4    1211  5070.8 1216.96    5088 1242.46
  5103.4 1246.39  5125.2  1257.2  5146.9 1261.53  5211.5 1268.13  5455.1 1277.23
  5538.3 1279.98  5598.2 1285.52  5727.2 1291.86  5766.7 1297.27  5778.2 1300.91
#Mann= 9 ,-1 , 0
  3676.2     .16       0  4127.8      .1       0  4181.1     .05       0
  4396.6      .1       0  4592.1     .05       0  4961.2     .16       0
  5024.3     .07       0  5030.3     .16       0  5455.1      .1       0
Bank Sta=4929.5,5040.8
XS Rating Curve= 0 ,0
Exp/Cntr=0.3,0.1

Type RM Length L Ch R = 1 ,28704   ,27,27,27
BEGIN DESCRIPTION:
YEAGER CREEK 56.0
END DESCRIPTION:
XS GIS Cut Line= 3
      2941947.53     10036901.09      2942541.29     10037991.39
      2943280.83     10038248.32
#Sta/Elev= 30
  3634.2 1260.29  3726.4  1256.8  3767.5  1250.2  3769.3 1249.81  3797.6 1244.48
  3851.8 1241.93    3884 1237.02  3982.8 1224.44  4108.2 1217.41  4694.4 1202.08
  4738.1 1202.09  4926.4 1202.95  4936.2 1199.95  4952.6 1194.24  4955.3 1193.74
  4958.6 1194.24  5054.2 1194.49  5063.3 1194.99 5077.79 1200.45  5085.3 1201.65
  5102.9 1198.77  5142.2 1198.24  5179.7 1203.51  5266.7  1208.3  5308.8 1216.25
  5349.1 1231.11  5391.4 1250.31    5455 1267.97  5617.5 1274.31  5658.6 1274.86
#Mann= 12 ,-1 , 0
  3634.2     .16       0  3767.5      .1       0  3769.3     .16       0
    3884     .05       0  4694.4      .1       0  4738.1     .05       0
  4926.4      .1       0  4952.6     .07       0  4958.6      .1       0
  5102.9     .05       0  5308.8     .16       0  5617.5      .1       0
#XS Ineff= 2 ,-1
 4650.51 4924.42 1203.07 5085.28  5658.6 1201.66
Permanent Ineff=
       T       T
Bank Sta=4936.2,5077.79
XS Rating Curve= 0 ,0
Exp/Cntr=0.3,0.1

Type RM Length L Ch R = 1 ,28677   ,27,27,27
BEGIN DESCRIPTION:
YEAGER CREEK 55.0
END DESCRIPTION:
XS GIS Cut Line= 3
      2941919.79     10036956.71      2942520.46     10038012.23
      2943286.62     10038279.17
#Sta/Elev= 30
  3653.6 1260.34  3723.3 1257.51  3753.7 1253.65  3788.2 1245.95  3830.6 1243.97
  3839.3 1243.61  3937.8 1232.52  3972.3 1226.06  4030.3  1222.2  4492.9 1206.69
  4686.9 1202.34  4688.3 1202.36  4909.7 1201.91  4929.5 1201.82    4947 1198.69
  5006.2 1196.36  5008.9 1195.86  5012.2 1196.36  5071.3 1199.82  5088.3 1200.56
  5116.2 1197.33  5141.3 1197.77  5204.8 1204.81  5252.8 1206.43  5283.6 1209.47
  5309.4  1215.5  5407.9 1255.18    5459 1268.98  5593.2 1275.05  5679.4 1276.25
#Mann= 12 ,-1 , 0
  3653.6     .16       0  3723.3      .1       0  3830.6     .16       0
  3839.3     .05       0  4686.9      .1       0  4688.3     .05       0
  4909.7      .1       0  5006.2     .07       0  5012.2      .1       0
  5116.2     .05       0  5252.8     .16       0  5593.2      .1       0
#XS Ineff= 2 ,-1
 4705.59 4915.55 1202.28 5077.89 5182.88 1201.03
Permanent Ineff=
       T       T
Bank Sta=4947,5071.3
XS Rating Curve= 0 ,0
Exp/Cntr=0.3,0.1

Type RM Length L Ch R = 1 ,28650   ,265,265,265
BEGIN DESCRIPTION:
YEAGER CREEK 54.0
END DESCRIPTION:
XS GIS Cut Line= 3
      2941905.85     10037012.19      2942492.68     10038029.59
      2943270.46     10038307.37
#Sta/Elev= 30
  3676.9 1258.88    3690 1258.54  3724.9  1256.4  3774.5 1247.28  3873.9 1239.75
  3956.9 1227.72  4015.8 1223.07  4528.3 1205.53  4558.7 1204.71  4798.6 1200.51
  4892.2 1201.09  4931.9 1201.62 4954.55 1192.52  4971.4 1188.89  4974.1 1188.39
  4977.4 1188.89  5024.7 1190.89  5038.1 1189.32 5051.14 1192.52  5080.5 1201.68
  5128.4  1196.9  5163.9  1200.4  5204.1 1204.63  5250.4 1205.68  5291.2 1211.57
  5358.1 1233.38  5399.1 1252.77  5452.2 1268.56  5533.8 1274.15  5677.3 1276.68
#Mann= 11 ,-1 , 0
  3676.9     .16       0    3690      .1       0  3873.9     .05       0
  4528.3      .1       0  4558.7     .05       0  4892.2      .1       0
  4971.4     .07       0  4977.4      .1       0  5128.4     .05       0
  5163.9     .16       0  5533.8      .1       0
#XS Ineff= 2 , 0
                         5082.39          1201.9
Permanent Ineff=
       T       T
Bank Sta=4954.55,5051.14
XS Rating Curve= 0 ,0
Exp/Cntr=0.3,0.1