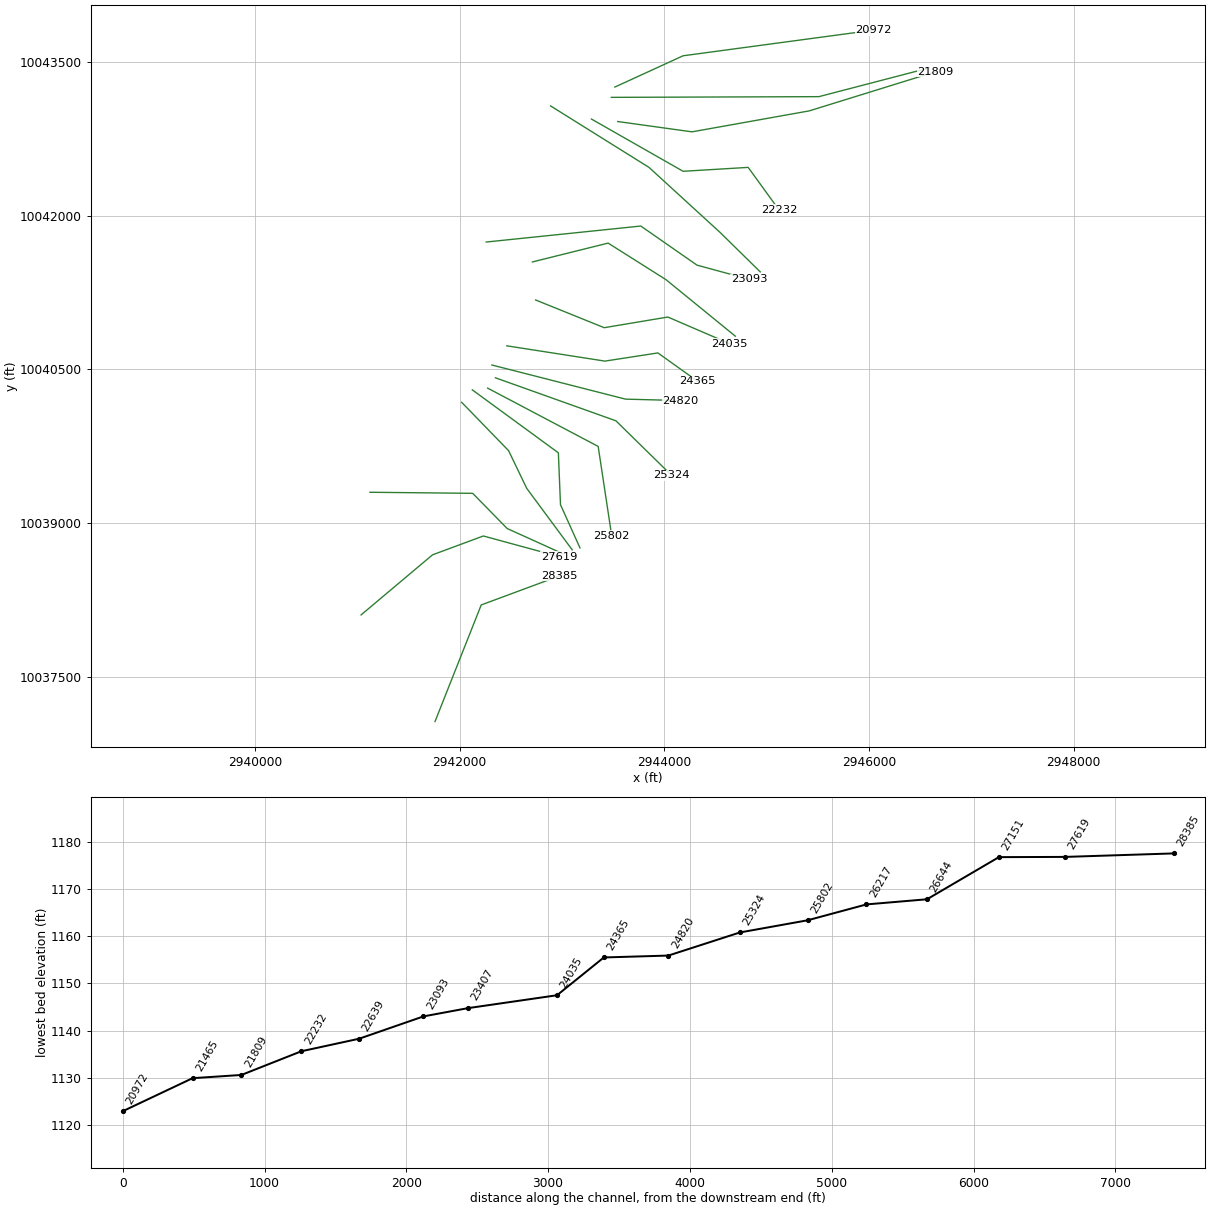
HEC-RAS study YEAGER CREEK.prj: YEAGER CREEK Base Level Engineering

--- YEAGER CREEK.g01 (geometry) --- (continued)

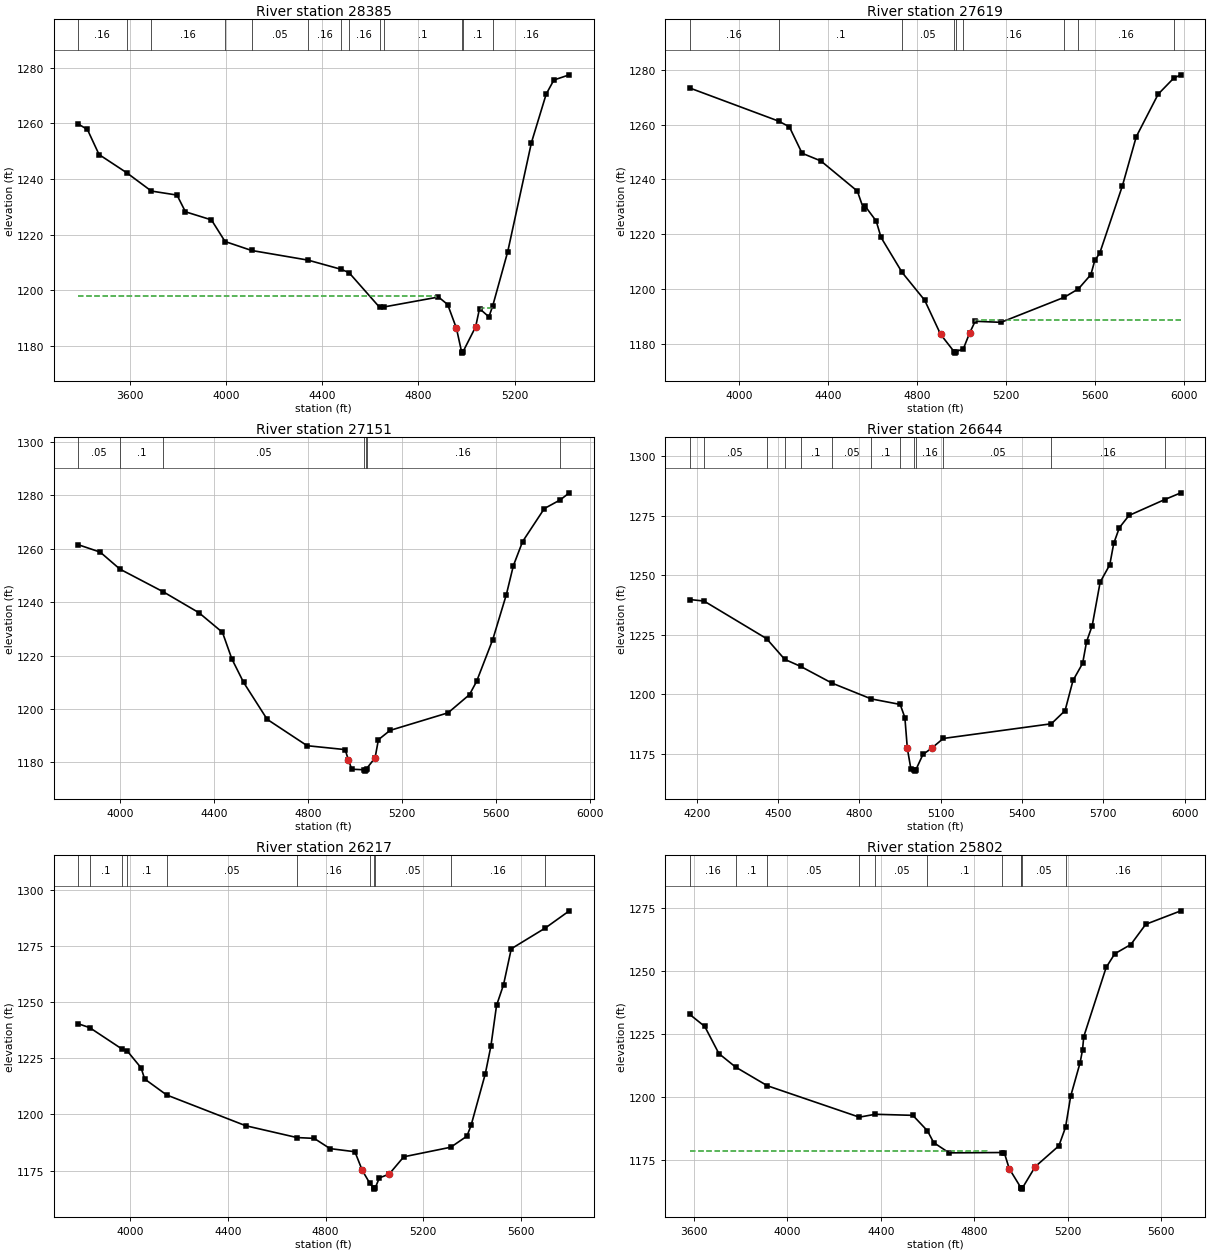
Type RM Length L Ch R = 1 ,28385   ,766,766,766
BEGIN DESCRIPTION:
YEAGER CREEK 53.0
END DESCRIPTION:
XS GIS Cut Line= 3
      2941760.05     10037060.86      2942211.43     10038199.73
      2942978.76     10038484.44
#Sta/Elev= 30
  3384.2 1259.77  3422.8  1257.8  3471.4 1248.78  3585.6  1242.3    3689 1235.68
  3795.6 1234.24  3830.7 1228.24  3938.8 1225.34  3995.5 1217.57  4105.7 1214.36
  4340.4  1210.9    4479 1207.58  4511.4 1206.38  4638.2 1193.97  4657.1 1194.09
  4883.4 1197.65  4921.7 1194.94  4958.1 1186.41  4979.4 1178.01  4982.2 1177.51
  4985.4 1178.01  5037.8 1186.92  5054.1 1193.49  5093.2 1190.52  5109.2 1194.53
  5171.4 1213.92  5270.1 1253.08  5331.4 1270.47  5363.4 1275.54  5427.7  1277.4
#Mann= 13 ,-1 , 0
  3384.2     .16       0  3585.6      .1       0    3689     .16       0
  3995.5      .1       0  4105.7     .05       0  4340.4     .16       0
    4479     .05       0  4511.4     .16       0  4638.2     .05       0
  4657.1      .1       0  4979.4     .07       0  4985.4      .1       0
  5109.2     .16       0
#XS Ineff= 2 ,-1
  3384.2 4872.16 1197.85 5061.08 5123.58 1193.79
Permanent Ineff=
       T       T
Bank Sta=4958.1,5037.8
XS Rating Curve= 0 ,0
Exp/Cntr=0.3,0.1

Type RM Length L Ch R = 1 ,27619   ,468,468,468
BEGIN DESCRIPTION:
YEAGER CREEK 51.0
END DESCRIPTION:
XS GIS Cut Line= 4
      2941037.84     10038102.52      2941735.73     10038689.31
      2942232.26     10038873.34       2942971.8     10038671.96
#Sta/Elev= 30
  3779.3 1273.31  4178.9 1261.25  4227.5 1259.16  4284.7 1249.54  4369.2 1246.74
  4533.1 1235.76  4561.7  1229.1  4568.2 1230.25  4617.7 1224.88  4639.7 1218.88
  4734.4 1206.14  4835.7 1196.03  4907.3 1183.61  4968.3 1177.27    4971 1176.77
  4974.3 1177.27  5009.3 1178.29  5037.7 1184.08  5062.7 1188.37  5178.9 1187.98
    5463  1197.1  5526.8 1200.17  5582.7 1205.35  5600.2  1210.5  5622.4 1213.14
  5724.5 1237.71  5786.7 1255.56  5885.2 1271.06  5955.2 1276.89  5987.1 1278.09
#Mann= 9 ,-1 , 0
  3779.3     .16       0  4178.9      .1       0  4734.4     .05       0
  4968.3    .035       0  4974.3     .05       0  5009.3     .16       0
    5463      .1       0  5526.8     .16       0  5955.2      .1       0
#XS Ineff= 2 , 0
                         5061.08         1188.84
Permanent Ineff=
       T       T
Bank Sta=4907.3,5037.7
XS Rating Curve= 0 ,0
Exp/Cntr=0.3,0.1

Type RM Length L Ch R = 1 ,27151   ,507,507,507
BEGIN DESCRIPTION:
YEAGER CREEK 50.0
END DESCRIPTION:
XS GIS Cut Line= 4
      2941124.58     10039300.42      2942128.09       10039290.
       2942464.9     10038946.25      2943015.19     10038697.06
#Sta/Elev= 30
  3822.1 1261.52    3916 1258.73    4000 1252.36  4184.5 1243.85    4336 1236.03
    4436 1228.68    4476 1218.72    4526 1209.92    4626 1196.12    4796 1186.24
  4957.7 1184.78  4971.8  1180.8    4986 1177.43  5039.6 1177.22  5042.3 1176.72
  5045.6 1177.22  5048.6 1177.63    5085 1181.71  5099.1 1188.49  5148.6 1191.97
  5395.5 1198.56  5486.5 1205.37  5516.5 1210.29  5585.3 1225.96    5643 1242.76
  5673.1 1253.66  5712.3 1262.68  5804.7 1275.04  5871.8 1278.26    5911 1280.93
#Mann= 7 ,-1 , 0
  3822.1     .05       0    4000      .1       0  4184.5     .05       0
  5039.6    .035       0  5045.6     .05       0  5048.6     .16       0
  5871.8      .1       0
Bank Sta=4971.8,5085
XS Rating Curve= 0 ,0
Exp/Cntr=0.3,0.1

Type RM Length L Ch R = 1 ,26644   ,427,427,427
BEGIN DESCRIPTION:
YEAGER CREEK 49.0
END DESCRIPTION:
XS GIS Cut Line= 4
      2942020.46     10040178.88      2942478.79     10039706.67
      2942655.87     10039338.61        2943100.     10038738.35
#Sta/Elev= 30
    4173 1239.88  4226.2 1239.23  4456.9 1223.46    4524 1214.75  4582.7 1211.79
  4697.9  1204.8  4843.2 1198.14  4950.2 1195.81  4967.5  1190.3  4976.6 1177.35
  4989.7 1168.72  5001.8  1168.3  5004.6  1167.8  5007.8  1168.3  5034.1 1174.79
  5067.2 1177.51  5109.3 1181.52  5508.2 1187.69  5558.8 1193.22  5588.1 1205.88
  5623.6 1213.06  5638.2 1222.18    5659 1228.91  5688.3 1247.17  5723.8 1254.46
  5738.4 1263.43  5759.2 1270.04  5794.7 1275.18  5926.8 1281.87  5986.2 1284.69
#Mann= 13 ,-1 , 0
    4173      .1       0  4226.2     .05       0  4456.9      .1       0
    4524     .05       0  4582.7      .1       0  4697.9     .05       0
  4843.2      .1       0  4950.2     .16       0  5001.8     .07       0
  5007.8     .16       0  5109.3     .05       0  5508.2     .16       0
  5926.8      .1       0
Bank Sta=4976.6,5067.2
XS Rating Curve= 0 ,0
Exp/Cntr=0.3,0.1

Type RM Length L Ch R = 1 ,26217   ,415,415,415
BEGIN DESCRIPTION:
YEAGER CREEK 48.0
END DESCRIPTION:
XS GIS Cut Line= 4
       2942124.6     10040300.44       2942964.9     10039685.84
      2942985.73     10039178.89      2943175.92     10038757.03
#Sta/Elev= 30
    3787 1240.48  3834.6 1238.72  3968.1 1229.09  3987.3 1228.45  4044.9 1220.79
  4059.5 1215.83  4149.6  1208.7  4473.4 1194.98  4683.1 1189.71  4753.7 1189.34
  4818.5 1184.78  4920.3 1183.38  4950.3 1175.11  4981.8 1169.22  4997.3 1167.21
  5000.1 1166.71  5003.3 1167.21  5020.3 1171.71  5060.4  1173.4  5120.4 1181.13
  5312.8  1185.4    5379 1190.34    5396 1195.16  5453.9 1218.02  5477.1 1230.49
  5500.2 1248.63  5528.8 1257.87  5560.5  1273.9  5699.8 1283.16  5798.2 1290.83
#Mann= 11 ,-1 , 0
    3787     .16       0  3834.6      .1       0  3968.1     .16       0
  3987.3      .1       0  4149.6     .05       0  4683.1     .16       0
  4981.8     .05       0  4997.3    .035       0  5003.3     .05       0
  5312.8     .16       0  5699.8      .1       0
Bank Sta=4950.3,5060.4
XS Rating Curve= 0 ,0
Exp/Cntr=0.3,0.1

Type RM Length L Ch R = 1 ,25802   ,478,478,478
BEGIN DESCRIPTION:
YEAGER CREEK 47.0
END DESCRIPTION:
XS GIS Cut Line= 3
      2942273.97     10040317.76      2943353.79     10039748.34
      2943485.58     10038877.82
#Sta/Elev= 30
  3582.5 1232.74  3647.2 1227.92  3707.7 1217.15    3779 1211.81    3915 1204.38
  4308.3 1191.92  4376.5 1193.06  4537.2 1192.64  4599.5 1186.53  4626.5 1181.81
  4692.5 1177.74  4917.9 1177.88  4929.3 1177.55  4949.5 1171.49  4999.7 1163.88
  5000.3 1163.85  5003.1 1163.35  5006.3 1163.85  5060.8 1172.26  5161.9 1180.53
  5190.4 1187.89  5212.5 1200.27  5252.9 1213.59    5263 1218.58  5268.4 1223.89
  5364.2 1251.35    5401 1256.78  5469.8 1260.45  5533.5 1268.47  5683.7 1273.82
#Mann= 11 ,-1 , 0
  3582.5     .16       0    3779      .1       0    3915     .05       0
  4308.3     .16       0  4376.5     .05       0  4599.5      .1       0
  4917.9     .16       0  4999.7     .05       0  5000.3    .035       0
  5006.3     .05       0  5190.4     .16       0
#XS Ineff= 2 , 0
         4856.53 1178.47
Permanent Ineff=
       T       T
Bank Sta=4949.5,5060.8
XS Rating Curve= 0 ,0
Exp/Cntr=0.3,0.1

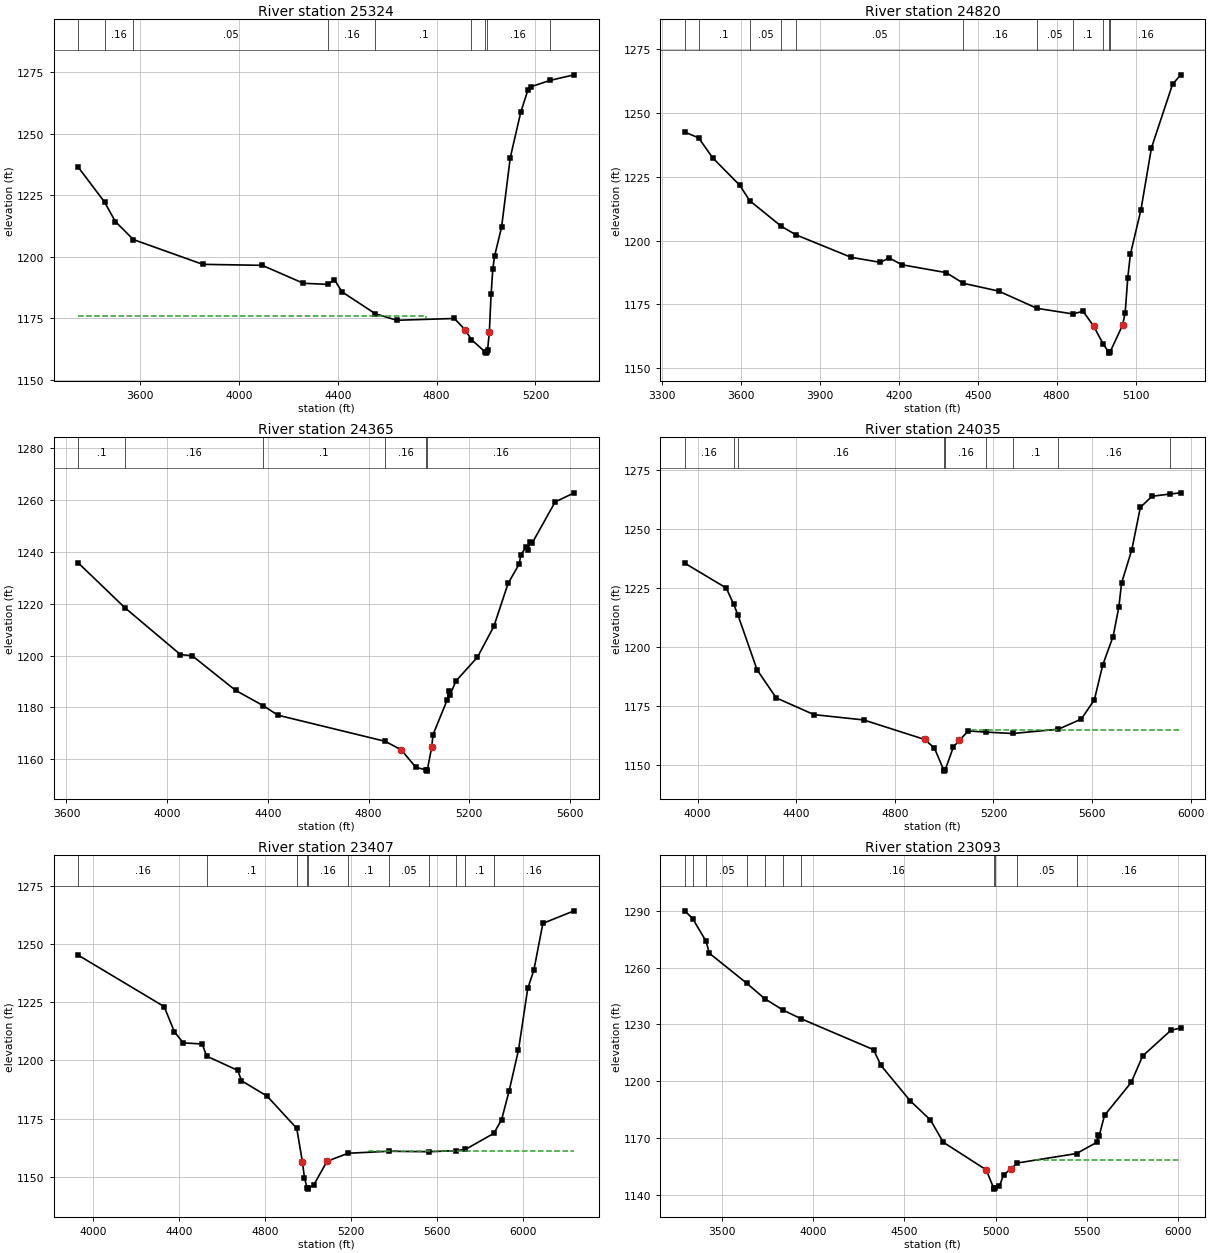
Type RM Length L Ch R = 1 ,25324   ,504,504,504
BEGIN DESCRIPTION:
YEAGER CREEK 46.0
END DESCRIPTION:
XS GIS Cut Line= 3
      2942350.31     10040418.48       2943527.4     10039998.34
      2944068.26     10039467.88
#Sta/Elev= 30
  3349.6 1236.29  3455.6  1222.2  3499.6 1214.24  3572.6 1206.92  3853.3 1196.86
  4094.4 1196.45  4260.8 1189.16  4359.4 1188.71  4386.5 1190.57  4417.3 1185.66
  4552.3 1176.77  4638.8 1174.13  4872.1 1174.85  4914.6 1170.36  4941.1 1166.27
  4996.4 1161.27  4999.2 1160.77  5002.4 1161.27  5006.6 1162.21  5013.6 1169.19
  5020.7 1184.65  5027.7 1194.99  5034.9 1200.29  5063.1 1211.93  5098.4 1240.26
  5140.9 1258.73  5169.2 1267.55  5183.3 1269.09  5259.3 1271.63    5357 1273.89
#Mann= 9 ,-1 , 0
  3349.6      .1       0  3455.6     .16       0  3572.6     .05       0
  4359.4     .16       0  4552.3      .1       0  4941.1     .16       0
  4996.4     .07       0  5002.4     .16       0  5259.3      .1       0
#XS Ineff= 2 , 0
         4758.84 1175.69
Permanent Ineff=
       T       T
Bank Sta=4914.6,5013.6
XS Rating Curve= 0 ,0
Exp/Cntr=0.3,0.1

Type RM Length L Ch R = 1 ,24820   ,455,455,455
BEGIN DESCRIPTION:
YEAGER CREEK 45.0
END DESCRIPTION:
XS GIS Cut Line= 3
      2942315.64     10040543.46      2943621.15     10040210.14
      2944159.38     10040196.25
#Sta/Elev= 30
  3385.6 1242.58    3438 1240.35  3491.7 1232.48  3594.9 1221.71    3632 1215.72
  3752.7 1205.62  3808.8 1202.27  4018.1 1193.47  4129.4 1191.48  4162.6 1193.24
  4211.1 1190.55  4379.7 1187.46    4445 1183.26  4578.8 1180.23  4725.2 1173.45
  4861.9 1171.25  4900.4 1172.31  4940.4 1166.48  4977.8 1159.29  4997.4 1156.38
  5000.1 1155.88  5003.4 1156.38  5050.4 1166.82  5060.4  1171.6  5070.4 1185.48
  5080.4 1194.71  5120.4 1212.03  5160.4 1236.39  5240.5 1261.27  5271.4 1265.05
#Mann= 11 ,-1 , 0
  3385.6     .16       0    3438      .1       0    3632     .05       0
  3752.7      .1       0  3808.8     .05       0    4445     .16       0
  4725.2     .05       0  4861.9      .1       0  4977.8     .16       0
  4997.4     .07       0  5003.4     .16       0
Bank Sta=4940.4,5050.4
XS Rating Curve= 0 ,0
Exp/Cntr=0.3,0.1

Type RM Length L Ch R = 1 ,24365   ,330,330,330
BEGIN DESCRIPTION:
YEAGER CREEK 44.0
END DESCRIPTION:
XS GIS Cut Line= 4
      2942461.44     10040730.97      2943419.76     10040581.67
      2943937.12     10040661.53      2944324.73     10040384.67
#Sta/Elev= 30
  3647.1 1235.69  3831.6 1218.48  4052.7 1200.39  4099.5 1199.94  4271.6 1186.61
  4381.1 1180.74  4439.9 1177.04  4866.9 1166.94  4929.9 1163.67    4988 1156.94
  5027.5 1155.98  5030.3 1155.48  5033.5 1155.98  5050.8 1164.62  5056.2 1169.54
  5111.5  1182.7  5119.3 1186.43  5124.4 1184.93  5146.8 1190.16  5232.8 1199.41
  5297.9 1211.29  5354.5 1227.85  5398.7 1235.32  5404.8 1238.78  5425.7 1241.78
  5434.3 1240.79  5440.5 1243.81  5449.1 1243.21  5541.2  1259.2  5616.8 1262.72
#Mann= 6 ,-1 , 0
  3647.1      .1       0  3831.6     .16       0  4381.1      .1       0
  4866.9     .16       0  5027.5     .07       0  5033.5     .16       0
Bank Sta=4929.9,5050.8
XS Rating Curve= 0 ,0
Exp/Cntr=0.3,0.1

Type RM Length L Ch R = 1 ,24035   ,628,628,628
BEGIN DESCRIPTION:
YEAGER CREEK 43.0
END DESCRIPTION:
XS GIS Cut Line= 4
      2942742.64     10041178.91      2943412.82     10040908.06
      2944034.34     10041012.23      2944638.48     10040751.82
#Sta/Elev= 30
  3948.3 1235.43  4116.4 1224.95  4146.3 1218.12  4164.4 1213.36  4241.4 1190.33
  4319.1 1178.46  4472.3 1171.38  4673.5 1169.14  4921.2 1160.87  4960.8 1157.23
  4998.3 1147.98  5001.1 1147.48  5004.3 1147.98  5037.5 1157.67  5062.2 1160.57
  5098.2 1164.46  5169.4 1163.99  5278.6  1163.4  5463.1  1165.2  5556.3  1169.5
  5609.3 1177.63  5643.7 1192.52  5685.3 1204.42  5708.7  1216.9  5719.7 1227.05
  5761.3 1241.18  5795.8 1259.03  5842.8 1263.74  5915.6  1264.7  5959.2 1265.21
#Mann= 9 ,-1 , 0
  3948.3     .16       0  4146.3      .1       0  4164.4     .16       0
  4998.3     .07       0  5004.3     .16       0  5169.4     .05       0
  5278.6      .1       0  5463.1     .16       0  5915.6      .1       0
#XS Ineff= 2 , 0
                         5112.22         1164.88
Permanent Ineff=
       T       T
Bank Sta=4921.2,5062.2
XS Rating Curve= 0 ,0
Exp/Cntr=0.3,0.1

Type RM Length L Ch R = 1 ,23407   ,314,314,314
BEGIN DESCRIPTION:
YEAGER CREEK 42.0
END DESCRIPTION:
XS GIS Cut Line= 4
      2942711.38     10041550.41      2943451.01     10041734.45
      2944016.98     10041376.81      2944693.74     10040824.99
#Sta/Elev= 30
  3931.1 1245.11    4330 1223.08    4378 1212.18  4419.4  1207.5  4507.1 1207.03
  4527.5 1201.83  4672.4 1195.69  4689.4 1191.27  4808.6 1184.66  4946.4 1170.82
 4972.57  1156.6  4982.4 1149.53  4994.7 1145.25  4997.5 1144.75  5000.7 1145.25
  5024.8 1146.42 5087.19  1156.7  5185.2 1160.14  5373.5    1161  5561.9  1160.8
  5687.4 1161.27  5730.7 1161.79  5862.5 1168.68    5899 1174.61  5934.1 1187.06
  5977.2 1204.42  6020.3 1230.89  6048.5 1238.65  6090.7  1258.8    6236 1264.17
#Mann= 11 ,-1 , 0
  3931.1     .16       0  4527.5      .1       0  4946.4     .16       0
  4994.7     .07       0  5000.7     .16       0  5185.2      .1       0
  5373.5     .05       0  5561.9     .16       0  5687.4     .05       0
  5730.7      .1       0  5862.5     .16       0
#XS Ineff= 2 , 0
                          5280.7         1161.19
Permanent Ineff=
       T       T
Bank Sta=4972.57,5087.19
XS Rating Curve= 0 ,0
Exp/Cntr=0.3,0.1

Type RM Length L Ch R = 1 ,23093   ,454,454,454
BEGIN DESCRIPTION:
YEAGER CREEK 41.0
END DESCRIPTION:
XS GIS Cut Line= 4
      2942260.04     10041744.86      2943770.46     10041901.11
      2944319.07     10041519.17      2944829.46     10041380.29
#Sta/Elev= 30
  3296.7 1290.05  3340.1 1285.87  3412.8 1274.03  3431.2 1267.66  3636.3 1251.75
  3735.1 1243.59  3833.8 1237.65  3932.6 1233.07  4330.6 1216.69  4370.8  1208.4
  4531.7 1189.63  4642.3 1179.52  4712.6 1167.77  4947.4 1153.21  4988.9  1143.5
  4991.6    1143  4994.9  1143.5  5019.9 1144.49  5042.5 1150.49  5084.4 1153.79
  5117.9  1156.8  5442.3  1161.8  5555.6 1167.85  5561.1 1171.56  5566.3 1171.07
  5595.7 1181.97  5742.1  1199.4  5804.3 1213.33  5959.7 1226.95  6012.6 1228.13
#Mann= 11 ,-1 , 0
  3296.7     .16       0  3340.1      .1       0  3412.8     .05       0
  3636.3      .1       0  3735.1     .16       0  3833.8      .1       0
  3932.6     .16       0  4988.9     .07       0  4994.9     .16       0
  5117.9     .05       0  5442.3     .16       0
#XS Ineff= 2 , 0
                         5215.15         1158.51
Permanent Ineff=
       T       T
Bank Sta=4947.4,5084.4
XS Rating Curve= 0 ,0
Exp/Cntr=0.3,0.1

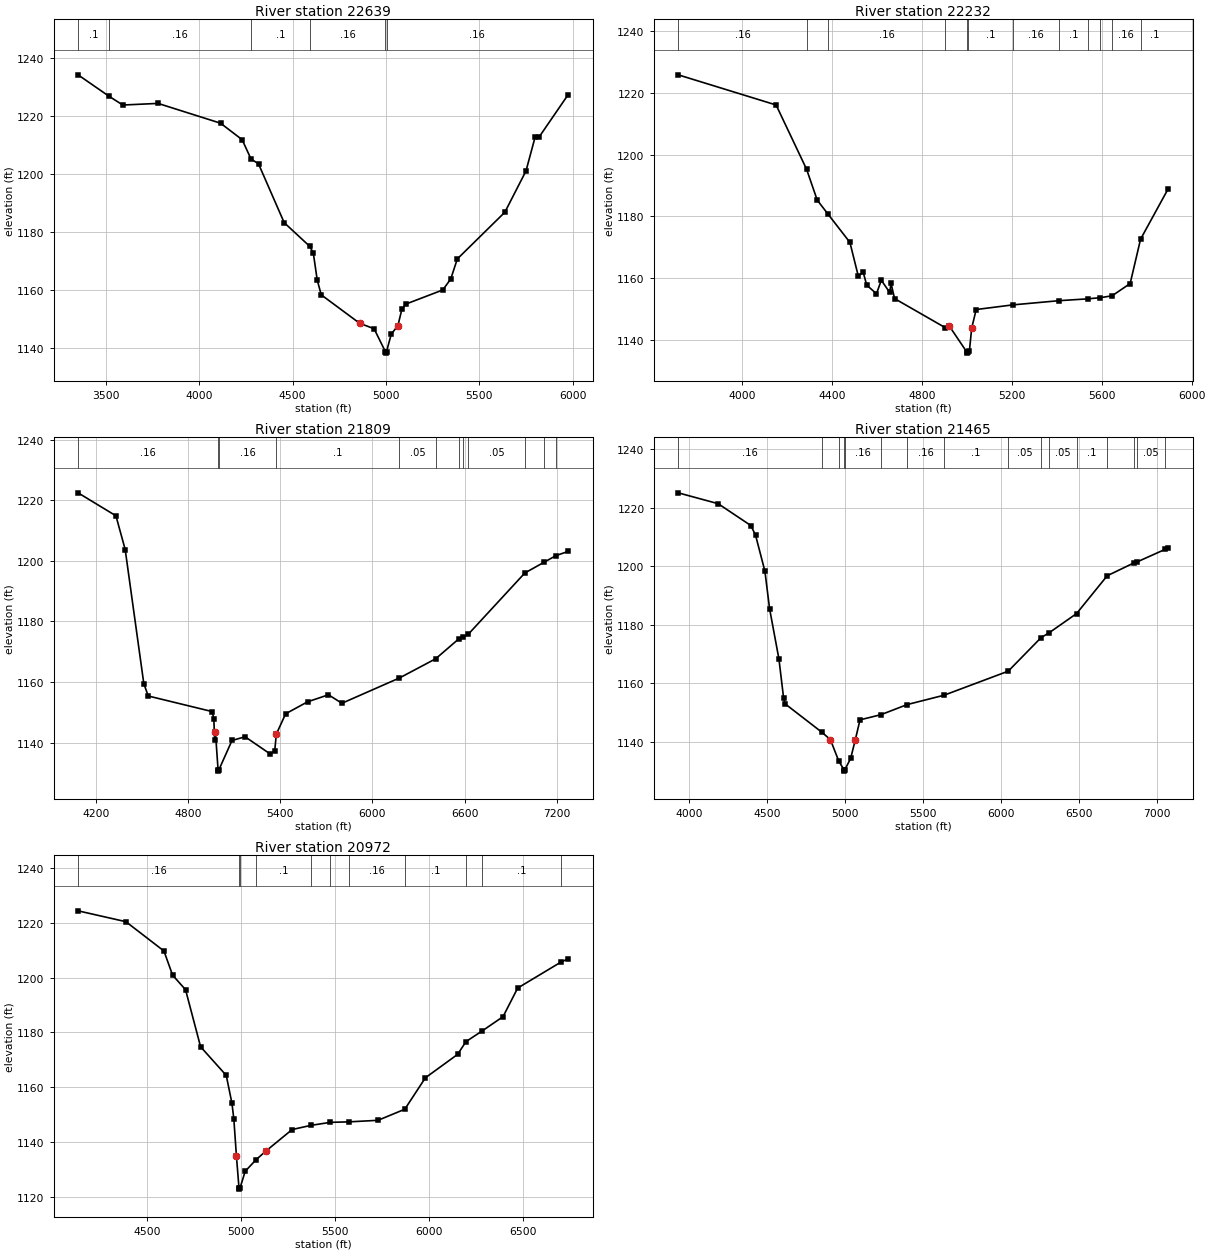
Type RM Length L Ch R = 1 ,22639   ,407,407,407
BEGIN DESCRIPTION:
YEAGER CREEK 40.0
END DESCRIPTION:
XS GIS Cut Line= 4
      2942888.51     10043074.73      2943850.32     10042474.03
      2944544.76     10041838.61      2944937.16     10041453.16
#Sta/Elev= 30
  3350.6 1234.29  3515.8 1226.93  3590.3 1223.87  3779.1 1224.43    4114  1217.6
  4229.6 1211.91  4277.1 1205.26  4317.3 1203.58  4454.9 1183.28  4591.8 1175.11
  4610.9 1172.79  4631.8  1163.5  4653.4 1158.38  4858.8 1148.58  4936.5 1146.68
    4997 1138.77  4999.8 1138.27    5003 1138.77  5028.4 1144.82  5064.1 1147.77
  5085.1 1153.36  5106.1 1155.18  5304.6 1160.07  5347.2 1163.87  5382.3 1170.77
    5637 1186.89  5750.2 1201.13  5799.6 1212.96  5820.9 1212.88  5975.9 1227.43
#Mann= 6 ,-1 , 0
  3350.6      .1       0  3515.8     .16       0  4277.1      .1       0
  4591.8     .16       0    4997     .07       0    5003     .16       0
Bank Sta=4858.8,5064.1
XS Rating Curve= 0 ,0
Exp/Cntr=0.3,0.1

Type RM Length L Ch R = 1 ,22232   ,423,423,423
BEGIN DESCRIPTION:
YEAGER CREEK 39.0
END DESCRIPTION:
XS GIS Cut Line= 4
      2943287.85     10042946.24      2944183.65     10042435.84
      2944819.07     10042474.03      2945120.67     10042058.03
#Sta/Elev= 30
  3714.5 1225.87  4150.3 1216.09    4286 1195.24  4333.3 1185.24  4380.8 1180.75
  4478.8 1171.53  4516.3 1160.55  4537.9 1161.86  4553.7 1157.67    4597 1154.87
  4618.6 1159.25    4656  1155.3  4661.8 1158.25  4677.6 1153.31  4903.9 1143.85
  4920.6 1144.47  4997.8 1136.12  5000.5 1135.62  5003.8 1136.12  5010.8 1136.38
  5020.8 1143.71  5040.9 1149.76  5203.3 1151.26  5410.1 1152.63  5538.9 1153.23
  5593.9 1153.61  5645.8 1154.21  5726.2 1158.19  5772.5 1172.56  5895.9 1188.97
#Mann= 12 ,-1 , 0
  3714.5     .16       0    4286      .1       0  4380.8     .16       0
  4903.9      .1       0  4997.8     .07       0  5003.8      .1       0
  5203.3     .16       0  5410.1      .1       0  5538.9     .16       0
  5593.9      .1       0  5645.8     .16       0  5772.5      .1       0
Bank Sta=4920.6,5020.8
XS Rating Curve= 0 ,0
Exp/Cntr=0.3,0.1

Type RM Length L Ch R = 1 ,21809   ,344,344,344
BEGIN DESCRIPTION:
YEAGER CREEK 38.0
END DESCRIPTION:
XS GIS Cut Line= 4
      2943544.78     10042921.94      2944270.46     10042821.25
      2945416.29     10043026.11      2946648.94     10043408.06
#Sta/Elev= 30
  4085.6 1222.46    4332 1214.88  4392.2 1203.73  4513.3 1159.48  4542.1  1155.4
  4958.4 1150.25  4968.6 1147.77    4974  1140.8  4979.1 1143.45  4996.1  1131.1
  4998.8  1130.6  5002.1  1131.1  5086.7 1140.71  5171.8 1141.95  5334.3 1136.29
  5364.8 1137.31    5375 1142.82  5435.9 1149.54  5578.1 1153.47  5714.1  1155.8
  5801.6    1153  6175.4 1161.34  6411.6 1167.69  6562.7  1174.3  6588.6 1174.75
  6622.8 1175.75    6991 1195.99  7113.4 1199.47  7194.8 1201.77  7272.7 1203.11
#Mann= 12 ,-1 , 0
  4085.6     .16       0  4996.1     .07       0  5002.1     .16       0
    5375      .1       0  6175.4     .05       0  6411.6      .1       0
  6562.7     .05       0  6588.6      .1       0  6622.8     .05       0
    6991      .1       0  7113.4     .05       0  7194.8      .1       0
Bank Sta=4979.1,5375
XS Rating Curve= 0 ,0
Exp/Cntr=0.3,0.1

Type RM Length L Ch R = 1 ,21465   ,493,493,493
BEGIN DESCRIPTION:
YEAGER CREEK 37.0
END DESCRIPTION:
XS GIS Cut Line= 3
       2943482.3     10043158.06      2945510.04       10043165.
      2946589.87     10043446.25
#Sta/Elev= 30
  3929.5 1225.03  4185.7 1221.32  4395.7 1213.84  4425.7 1210.54  4485.7 1198.25
  4515.7 1185.42  4575.7 1168.23  4605.7 1154.88  4615.7  1152.9    4851 1143.21
  4905.7 1140.69  4959.4 1133.36  4992.7 1130.42  4995.4 1129.92  4998.7 1130.42
  5035.7 1134.26  5065.7 1140.67  5095.7 1147.44  5230.7 1149.22  5397.8 1152.66
  5635.3 1155.87  6046.5 1164.08  6257.8 1175.58  6306.1  1177.1  6484.8 1183.76
  6681.4 1196.69  6853.1 1201.09    6872 1201.39  7054.8 1205.76  7073.1 1206.05
#Mann= 16 ,-1 , 0
  3929.5     .16       0    4851     .05       0  4959.4     .16       0
  4992.7     .07       0  4998.7     .16       0  5230.7      .1       0
  5397.8     .16       0  5635.3      .1       0  6046.5     .05       0
  6257.8      .1       0  6306.1     .05       0  6484.8      .1       0
  6681.4     .05       0  6853.1      .1       0    6872     .05       0
  7054.8      .1       0
Bank Sta=4905.7,5065.7
XS Rating Curve= 0 ,0
Exp/Cntr=0.3,0.1

Type RM Length L Ch R = 1 ,20972   ,398,398,398
BEGIN DESCRIPTION:
YEAGER CREEK 36.0
END DESCRIPTION:
XS GIS Cut Line= 3
      2943517.02     10043258.77      2944183.65     10043564.31
      2946041.29     10043814.31
#Sta/Elev= 30
  4134.6 1224.31  4389.2 1220.35  4591.6 1209.68  4637.6 1200.89  4706.6 1195.57
  4786.6 1174.79  4923.2 1164.35  4953.5 1154.19  4963.6 1148.44  4977.4 1134.89
  4990.9 1123.42  4993.6 1122.92  4996.9 1123.42  5024.1 1129.43  5081.4 1133.61
  5135.1 1136.84  5273.6 1144.62  5373.5 1146.15  5477.3 1147.25  5576.3 1147.43
  5730.6 1147.99  5873.3 1152.03  5982.7 1163.48  6154.2 1172.01  6198.6 1176.65
  6284.6 1180.54    6396 1185.75  6473.8 1196.17  6705.9 1205.71  6742.3  1206.8
#Mann= 11 ,-1 , 0
  4134.6     .16       0  4990.9     .07       0  4996.9     .16       0
  5081.4      .1       0  5373.5     .05       0  5477.3      .1       0
  5576.3     .16       0  5873.3      .1       0  6198.6     .05       0
  6284.6      .1       0  6705.9     .05       0
Bank Sta=4977.4,5135.1
XS Rating Curve= 0 ,0
Exp/Cntr=0.3,0.1