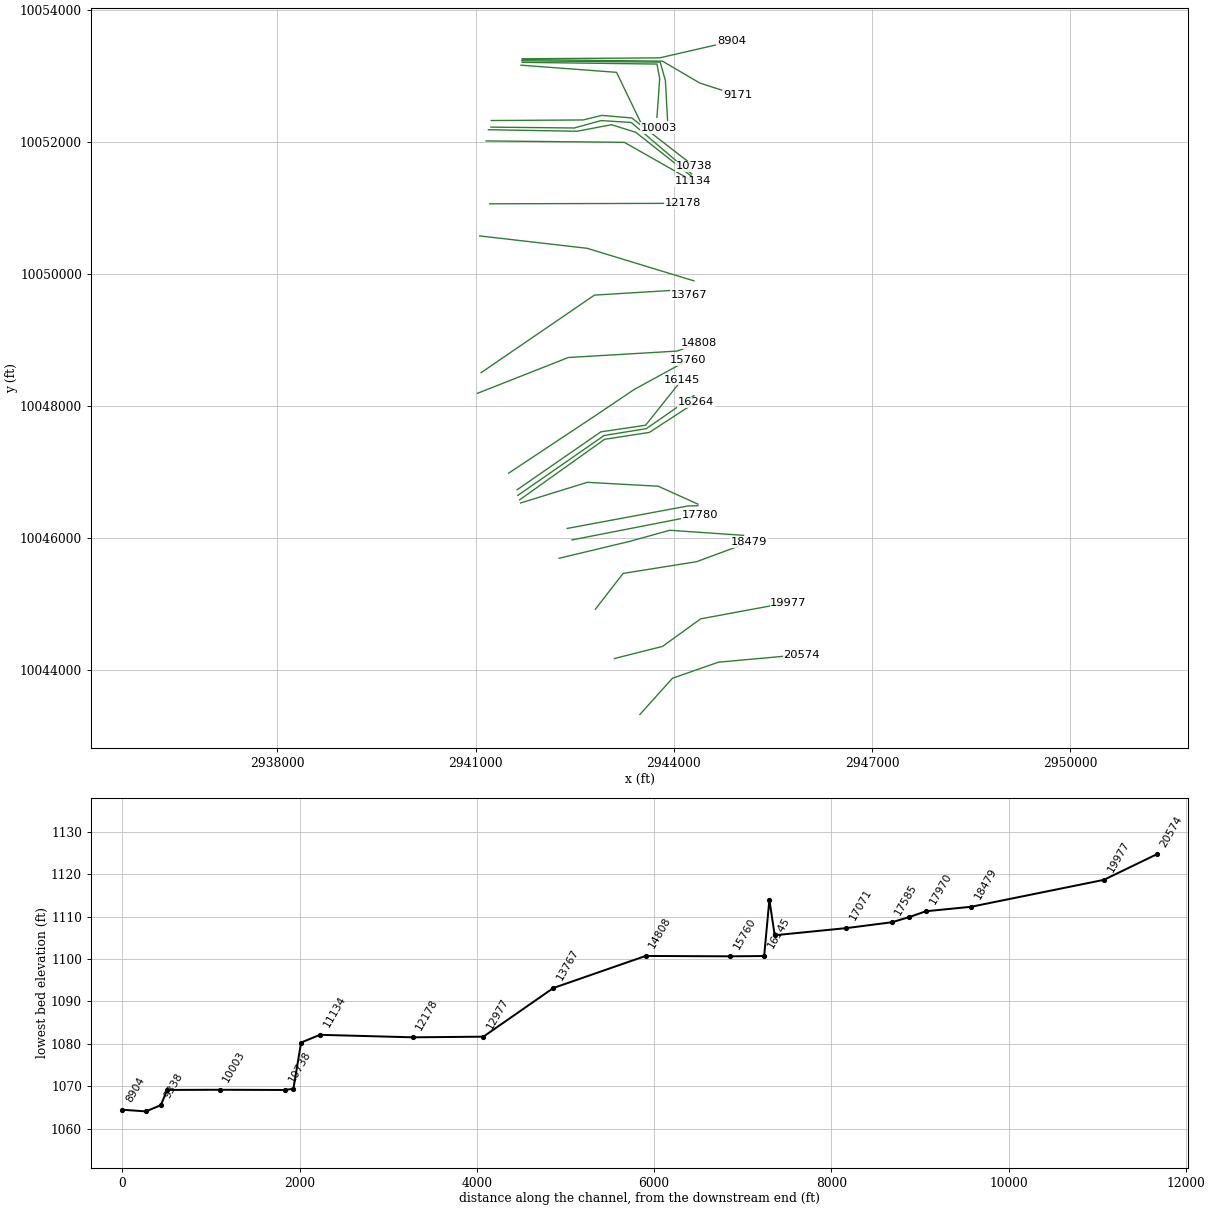
HEC-RAS study YEAGER CREEK.prj: YEAGER CREEK Base Level Engineering

--- YEAGER CREEK.g01 (geometry) --- (continued)

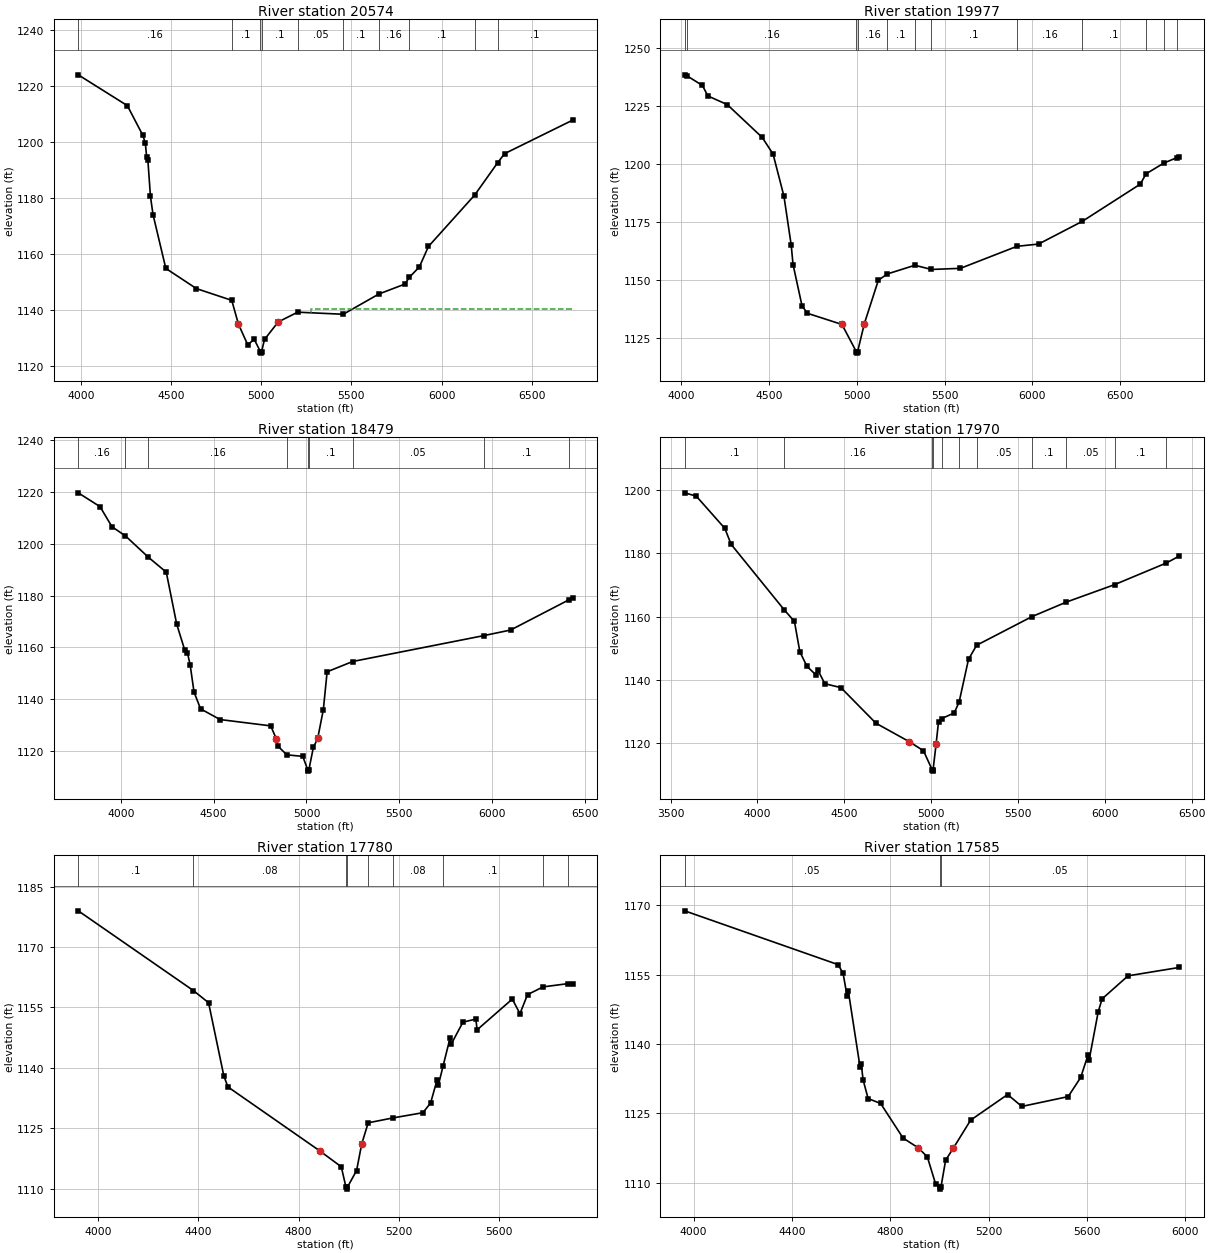
Type RM Length L Ch R = 1 ,20574   ,597,597,597
BEGIN DESCRIPTION:
YEAGER CREEK 35.0
END DESCRIPTION:
XS GIS Cut Line= 4
      2943485.74     10043331.68      2943978.79     10043880.28
      2944673.23     10044123.34      2945933.58     10044237.91
#Sta/Elev= 30
  3986.4 1223.92  4258.5 1212.93  4343.7 1202.42    4358 1199.65  4365.4 1194.69
  4372.2 1193.47  4386.4  1180.6  4400.6 1174.11  4471.6 1154.89  4641.2 1147.69
    4837  1143.5    4874 1135.01    4925 1127.72  4961.8 1129.55  4996.1 1125.18
  4998.9 1124.68  5002.1 1125.18  5018.5 1129.56  5094.5  1135.8  5202.2 1139.28
    5455 1138.54  5652.5 1145.77  5796.4  1149.3  5821.9 1151.77  5876.7 1155.43
  5926.9 1162.71  6183.5 1181.08  6309.7 1192.52  6348.6  1195.8  6725.3 1207.74
#Mann= 10 ,-1 , 0
  3986.4     .16       0    4837      .1       0  4996.1     .07       0
  5002.1      .1       0  5202.2     .05       0    5455      .1       0
  5652.5     .16       0  5821.9      .1       0  6183.5     .05       0
  6309.7      .1       0
#XS Ineff= 2 , 0
                         5274.33         1140.35
Permanent Ineff=
       T       T
Bank Sta=4874,5094.5
XS Rating Curve= 0 ,0
Exp/Cntr=0.3,0.1

Type RM Length L Ch R = 1 ,19977   ,1498,1498,1498
BEGIN DESCRIPTION:
YEAGER CREEK 34.0
END DESCRIPTION:
XS GIS Cut Line= 4
      2943100.35      10044178.9      2943829.48     10044362.92
      2944405.87     10044779.59      2945734.61     10045025.91
#Sta/Elev= 30
  4019.3 1238.45    4031 1238.09  4120.5 1233.87  4151.4 1229.36  4261.8 1225.64
  4460.8 1211.51  4522.7 1204.34  4584.6 1186.22  4625.9 1165.23  4636.5 1156.79
  4687.7 1138.97  4718.7 1135.79  4914.9    1131  4997.7 1119.15  5000.5 1118.65
  5003.7 1119.15  5042.5 1131.33  5122.2 1150.03  5173.1 1152.72    5330 1156.47
  5424.5 1154.67  5589.8 1155.15  5911.6 1164.63  6034.4  1165.6  6283.8 1175.38
  6614.1 1191.41  6646.6 1195.83  6746.9 1200.42  6821.1 1202.77  6833.9 1202.97
#Mann= 12 ,-1 , 0
  4019.3      .1       0    4031     .16       0  4997.7     .07       0
  5003.7     .16       0  5173.1      .1       0    5330     .16       0
  5424.5      .1       0  5911.6     .16       0  6283.8      .1       0
  6646.6     .16       0  6746.9      .1       0  6821.1     .16       0
Bank Sta=4914.9,5042.5
XS Rating Curve= 0 ,0
Exp/Cntr=0.3,0.1

Type RM Length L Ch R = 1 ,18479   ,509,509,509
BEGIN DESCRIPTION:
YEAGER CREEK 33.0
END DESCRIPTION:
XS GIS Cut Line= 4
      2942812.13     10044925.43      2943232.26     10045467.09
      2944343.37     10045644.17       2945141.2     10045939.02
#Sta/Elev= 30
  3771.2 1219.64  3888.4 1214.31  3952.7 1206.56  4025.5 1203.01  4148.3 1194.82
  4245.1 1189.04  4301.2    1169  4344.7 1158.96  4359.2 1157.88  4373.6 1153.34
  4394.5  1142.8  4429.8 1136.32  4534.8 1132.19  4807.3 1129.76  4837.7 1124.73
  4845.5 1121.99  4894.1 1118.58    4980 1117.99  5006.8  1112.8  5009.5  1112.3
  5012.8  1112.8    5037 1121.42  5060.4 1124.92  5090.8 1136.05  5111.1 1150.61
  5248.5 1154.58  5955.5 1164.58    6099 1166.72  6411.8 1178.33  6432.4  1178.9
#Mann= 9 ,-1 , 0
  3771.2     .16       0  4025.5      .1       0  4148.3     .16       0
  4894.1      .1       0  5006.8     .07       0  5012.8      .1       0
  5248.5     .05       0  5955.5      .1       0  6411.8     .05       0
Bank Sta=4837.7,5060.4
XS Rating Curve= 0 ,0
Exp/Cntr=0.3,0.1

Type RM Length L Ch R = 1 ,17970   ,190,190,190
BEGIN DESCRIPTION:
YEAGER CREEK 32.0
END DESCRIPTION:
XS GIS Cut Line= 4
      2942263.52     10045696.25      2943336.43      10045953.2
      2943937.12     10046119.86      2945054.28     10046043.54
#Sta/Elev= 30
  3580.6 1199.12  3647.4 1198.08  3811.9 1187.89  3848.4 1182.84    4153 1162.24
  4212.9  1158.5  4243.8 1148.96  4284.9 1144.33  4336.3 1141.65  4346.6 1143.29
  4387.7 1138.85  4480.3 1137.62  4682.3 1126.37  4872.8 1120.59  4955.8 1117.69
  5005.3 1111.75  5008.1 1111.25  5011.3 1111.75  5028.4 1119.71  5042.6 1126.91
  5059.7 1127.83  5132.2  1129.6  5160.8 1132.98  5215.2 1146.56    5262 1150.99
  5579.6 1160.01  5779.5 1164.64  6056.4 1170.13  6353.9 1176.95    6427  1179.1
#Mann= 11 ,-1 , 0
  3580.6      .1       0    4153     .16       0  5005.3     .07       0
  5011.3     .16       0  5059.7     .05       0  5160.8     .16       0
    5262     .05       0  5579.6      .1       0  5779.5     .05       0
  6056.4      .1       0  6353.9     .05       0
Bank Sta=4872.8,5028.4
XS Rating Curve= 0 ,0
Exp/Cntr=0.3,0.1

Type RM Length L Ch R = 1 ,17780   ,195,195,195
BEGIN DESCRIPTION:
YEAGER CREEK 31.0
END DESCRIPTION:
XS GIS Cut Line= 2
      2942457.93     10045974.03      2944394.43      10046352.3
#Sta/Elev= 30
  3920.2 1178.97  4379.7 1159.17  4440.4 1156.15  4501.5 1137.94  4517.7 1135.24
  4883.6 1119.39  4970.2 1115.41  4988.8 1110.36  4991.6 1109.86  4994.8 1110.36
  5031.3 1114.48  5051.7 1121.08  5077.6 1126.33  5177.3 1127.55    5296 1128.84
  5326.8 1131.25  5352.7 1137.02  5357.8 1135.68  5376.7 1140.47  5404.2 1147.33
  5409.3 1145.89  5455.8 1151.32  5507.3 1152.09  5512.4 1149.42  5652.9 1157.06
  5683.4 1153.43  5713.6 1158.15  5775.5 1160.08  5875.2 1160.89  5893.3 1160.91
#Mann= 9 ,-1 , 0
  3920.2      .1       0  4379.7     .08       0  4988.8     .07       0
  4994.8     .08       0  5077.6     .05       0  5177.3     .08       0
  5376.7      .1       0  5775.5     .08       0  5875.2      .1       0
Bank Sta=4883.6,5051.7
XS Rating Curve= 0 ,0
Exp/Cntr=0.3,0.1

Type RM Length L Ch R = 1 ,17585   ,514,514,514
BEGIN DESCRIPTION:
YEAGER CREEK 30.0
END DESCRIPTION:
XS GIS Cut Line= 3
      2942385.03     10046147.64      2944211.43     10046487.92
      2944363.86     10046491.38
#Sta/Elev= 30
  3963.5 1168.76  4587.5 1157.14  4607.8 1155.28  4623.9 1150.42  4628.9 1151.51
  4676.6  1135.1  4681.7 1135.64  4689.2 1132.26  4709.6 1128.21  4760.4 1127.16
    4852 1119.67    4913 1117.59  4950.4 1115.63  4984.2 1109.76  5000.1 1109.15
  5002.9 1108.65  5006.1 1109.15  5024.9 1114.89  5055.4 1117.43  5126.6 1123.55
    5277 1129.08  5334.8 1126.51  5523.3 1128.63  5574.2 1132.77  5603.5 1137.53
  5608.6 1136.56  5645.4 1146.93  5661.3 1149.74  5766.8 1154.72  5973.8 1156.52
#Mann= 3 ,-1 , 0
  3963.5     .05       0  5000.1     .04       0  5006.1     .05       0
Bank Sta=4913,5055.4
XS Rating Curve= 0 ,0
Exp/Cntr=0.3,0.1

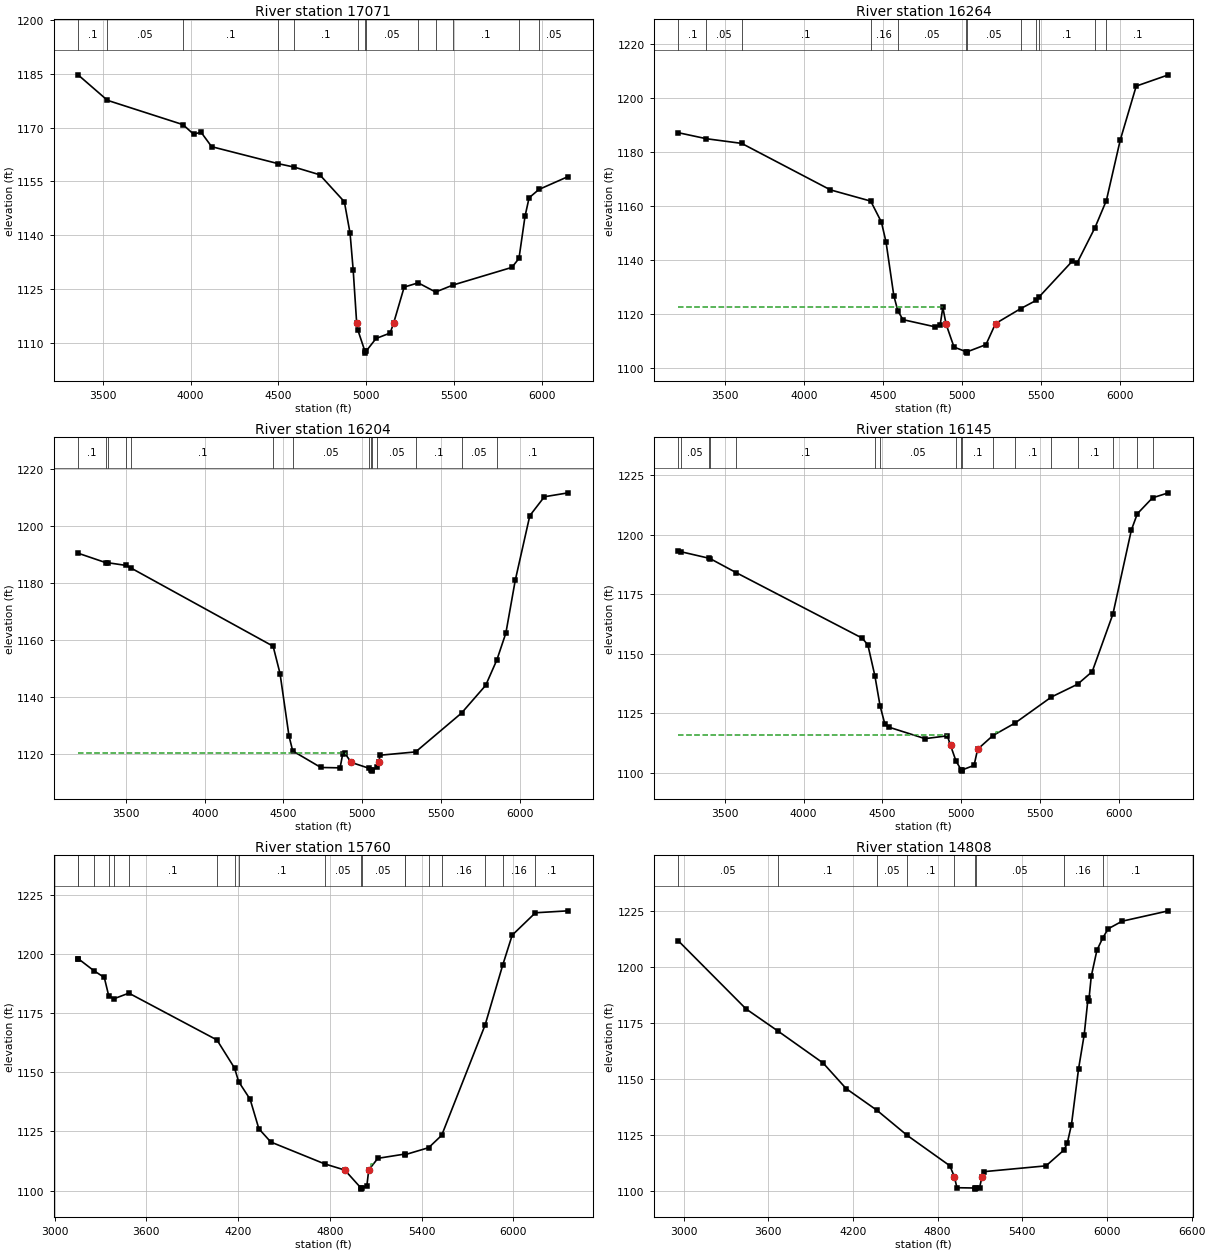
Type RM Length L Ch R = 1 ,17071   ,807,807,807
BEGIN DESCRIPTION:
YEAGER CREEK 29.0
END DESCRIPTION:
XS GIS Cut Line= 4
      2941680.14     10046533.05      2942690.59     10046845.56
      2943763.51     10046786.53       2944363.8     10046515.88
#Sta/Elev= 30
  3359.5 1184.66  3526.9 1177.57  3956.8 1170.81  4016.9 1168.17    4060 1168.69
    4120 1164.68  4499.4 1159.95    4591 1158.99  4735.5 1156.87  4875.7 1149.36
  4908.2 1140.61  4925.8 1130.47  4945.8 1115.63  4952.6 1113.68  4992.9 1107.77
  4995.7 1107.27  4998.9 1107.77    5056 1111.34  5136.1 1112.85  5156.2 1115.62
  5216.3 1125.64  5296.2 1126.81  5395.2 1124.26  5494.5 1126.21  5829.3 1131.11
  5869.8  1133.6  5904.2 1145.31  5927.4 1150.46  5983.2 1152.78  6150.2 1156.38
#Mann= 13 ,-1 , 0
  3359.5      .1       0  3526.9     .05       0  3956.8      .1       0
  4499.4     .05       0    4591      .1       0  4952.6     .05       0
  4992.9    .033       0  4998.9     .05       0  5296.2      .1       0
  5395.2     .05       0  5494.5      .1       0  5869.8     .16       0
  5983.2     .05       0
Bank Sta=4945.8,5156.2
XS Rating Curve= 0 ,0
Exp/Cntr=0.3,0.1

Type RM Length L Ch R = 1 ,16264   ,60,60,60
BEGIN DESCRIPTION:
Mapping XS 194e1812
END DESCRIPTION:
XS GIS Cut Line= 4
      2941666.83     10046580.93      2942951.52     10047496.71
       2943628.6     10047600.87      2944334.78     10048060.11
#Sta/Elev= 30
  3202.8 1187.06  3381.2 1184.83  3604.3 1183.11  4166.3 1165.93  4421.7 1161.78
  4489.6    1154  4518.8 1146.62    4568 1126.86  4593.4 1121.22  4626.1 1117.96
    4828 1115.33  4861.5 1115.96  4878.6  1122.5  4898.8 1116.35  4949.4 1107.82
  5027.3 1106.09  5030.1 1105.59  5033.3 1106.09  5151.7 1108.73  5212.5 1116.52
  5371.2 1122.02  5470.3  1125.1  5490.2 1126.48    5699 1139.61  5727.8 1138.76
  5842.7 1152.01  5914.4 1161.97  6002.2 1184.29  6103.6 1204.28  6307.9 1208.45
#Mann= 12 ,-1 , 0
  3202.8      .1       0  3381.2     .05       0  3604.3      .1       0
  4421.7     .16       0  4593.4     .05       0  5027.3    .033       0
  5033.3     .05       0  5371.2      .1       0  5470.3     .16       0
  5490.2      .1       0  5842.7     .05       0  5914.4      .1       0
#XS Ineff= 2 , 0
         4877.27 1122.68
Permanent Ineff=
       T       T
Bank Sta=4898.8,5212.5
XS Rating Curve= 0 ,0
Exp/Cntr=0.3,0.1

Type RM Length L Ch R = 1 ,16204   ,59,59,59
BEGIN DESCRIPTION:
YEAGER CREEK 28.0
END DESCRIPTION:
XS GIS Cut Line= 4
      2941638.49     10046647.63      2942944.07     10047553.89
      2943582.96     10047658.06      2944304.33     10048157.47
#Sta/Elev= 30
    3195 1190.45  3371.5 1187.13  3384.5  1187.1  3501.1 1186.15  3534.2 1185.16
  4434.3  1157.8  4478.2 1148.21  4534.9 1126.37  4558.6 1121.05  4737.5 1115.24
  4859.7 1115.11  4875.7 1119.81  4890.1  1120.2  4930.6 1117.02  5040.5 1115.02
  5057.1 1114.46  5059.8 1113.96  5063.1 1114.46  5095.1 1115.24 5106.03 1116.99
    5113 1119.54  5339.7 1120.71  5631.2 1134.34  5784.6 1144.06  5855.5 1152.97
  5912.9 1162.42  5972.4  1180.9    6065 1203.62  6157.5 1210.26    6309 1211.64
#Mann= 14 ,-1 , 0
    3195      .1       0  3371.5     .05       0  3384.5      .1       0
  3501.1     .05       0  3534.2      .1       0  4434.3     .16       0
  4558.6     .05       0  5040.5      .1       0  5057.1    .033       0
  5063.1      .1       0  5095.1     .05       0  5339.7      .1       0
  5631.2     .05       0  5855.5      .1       0
#XS Ineff= 2 , 0
         4899.65 1120.22
Permanent Ineff=
       T       T
Bank Sta=4930.6,5106.03
XS Rating Curve= 0 ,0
Exp/Cntr=0.3,0.1

Type RM Length L Ch R = 1 ,16145   ,385,385,385
BEGIN DESCRIPTION:
YEAGER CREEK 27.0
END DESCRIPTION:
XS GIS Cut Line= 4
      2941627.78     10046732.85       2942895.1     10047609.56
      2943572.18     10047709.38      2944123.12     10048399.14
#Sta/Elev= 30
  3205.5 1193.07    3222 1192.88  3403.1  1190.1  3406.2 1190.03  3571.7 1184.12
  4371.8 1156.57  4407.6 1153.71    4452 1140.76  4484.9 1128.13    4515 1120.56
  4543.9  1119.1  4770.1 1114.34  4911.6 1115.52  4931.9 1111.47  4966.5 1104.92
  4999.6 1101.19  5002.4 1100.69  5005.6 1101.19    5081 1103.11  5103.7 1109.89
  5200.4 1115.63  5339.8 1120.85  5571.5 1131.84  5737.1 1137.19  5830.2 1142.51
  5961.5  1166.7  6078.4 1201.99  6116.3 1208.84  6212.7 1215.54  6313.7 1217.63
#Mann= 17 ,-1 , 0
  3205.5      .1       0    3222     .05       0  3403.1      .1       0
  3406.2     .05       0  3571.7      .1       0    4452     .16       0
  4484.9     .05       0  4966.5      .1       0  4999.6     .07       0
  5005.6      .1       0  5200.4     .05       0  5339.8      .1       0
  5571.5     .05       0  5737.1      .1       0  5961.5     .16       0
  6116.3      .1       0  6212.7     .16       0
#XS Ineff= 2 ,-1
  3205.5  4907.1 1116.07 5220.39 5255.73 1116.95
Permanent Ineff=
       T       T
Bank Sta=4931.9,5103.7
XS Rating Curve= 0 ,0
Exp/Cntr=0.3,0.1

Type RM Length L Ch R = 1 ,15760   ,952,952,952
BEGIN DESCRIPTION:
YEAGER CREEK 26.0
END DESCRIPTION:
XS GIS Cut Line= 4
      2941499.66     10046984.47      2942881.57     10047901.11
      2943395.46     10048248.34      2944207.96     10048692.78
#Sta/Elev= 30
  3153.9 1197.91  3156.6 1197.89  3255.9 1192.97  3325.4 1190.04  3354.7 1182.23
  3389.9 1181.08  3486.2 1183.41  4061.9 1163.64    4177 1151.77  4203.9 1146.02
  4278.9 1138.57    4336 1126.12  4414.2 1120.52  4765.2 1111.31  4898.1 1108.67
    5003 1101.12  5005.7 1100.62    5009 1101.12    5042 1101.96 5054.26 1108.71
  5113.9 1113.63  5289.9 1115.43  5292.5 1115.18  5446.2 1118.14  5531.2 1123.35
  5815.1 1169.96  5929.5 1195.11  5992.2 1207.91    6144 1217.37  6358.5 1218.19
#Mann= 19 ,-1 , 0
  3153.9     .05       0  3156.6      .1       0  3255.9     .05       0
  3354.7      .1       0  3389.9     .05       0  3486.2      .1       0
  4061.9     .16       0    4177     .05       0  4203.9      .1       0
  4765.2     .05       0    5003    .035       0    5009     .05       0
  5289.9      .1       0  5292.5     .05       0  5446.2      .1       0
  5531.2     .16       0  5815.1      .1       0  5929.5     .16       0
    6144      .1       0
#XS Ineff= 2 ,-1
 5071.81 5099.34  1111.1 5122.93  6358.5 1113.71
Permanent Ineff=
       T       T
Bank Sta=4898.1,5054.26
XS Rating Curve= 0 ,0
Exp/Cntr=0.3,0.1

Type RM Length L Ch R = 1 ,14808   ,1041,1041,1041
BEGIN DESCRIPTION:
YEAGER CREEK 24.0
END DESCRIPTION:
XS GIS Cut Line= 4
      2941027.39     10048192.78       2942402.4     10048734.45
      2944048.23     10048831.67      2944374.59     10048949.71
#Sta/Elev= 30
    2962 1211.64  3441.7 1181.23  3667.2 1171.37  3988.7 1157.01  4151.1 1145.64
    4370 1135.91    4584 1124.72  4886.7 1111.13  4918.6 1106.15  4936.8 1101.34
    5064 1101.21  5066.8 1100.71    5070 1101.21  5097.1 1101.33 5113.64 1106.13
  5127.1 1108.51  5567.9 1111.11  5694.7 1118.15  5718.1  1121.1  5748.2 1129.52
  5798.3 1154.36  5838.4 1169.68  5866.3 1186.31  5871.3 1184.97  5888.4 1195.76
  5928.5  1207.4  5970.1 1212.94  6008.6 1217.01    6107 1220.39  6435.6 1225.03
#Mann= 9 ,-1 , 0
    2962     .05       0  3667.2      .1       0    4370     .05       0
    4584      .1       0  4918.6     .05       0    5064    .033       0
    5070     .05       0  5694.7     .16       0  5970.1      .1       0
#XS Ineff= 2 , 0
                         5256.29         1108.86
Permanent Ineff=
       T       T
Bank Sta=4918.6,5113.64
XS Rating Curve= 0 ,0
Exp/Cntr=0.3,0.1

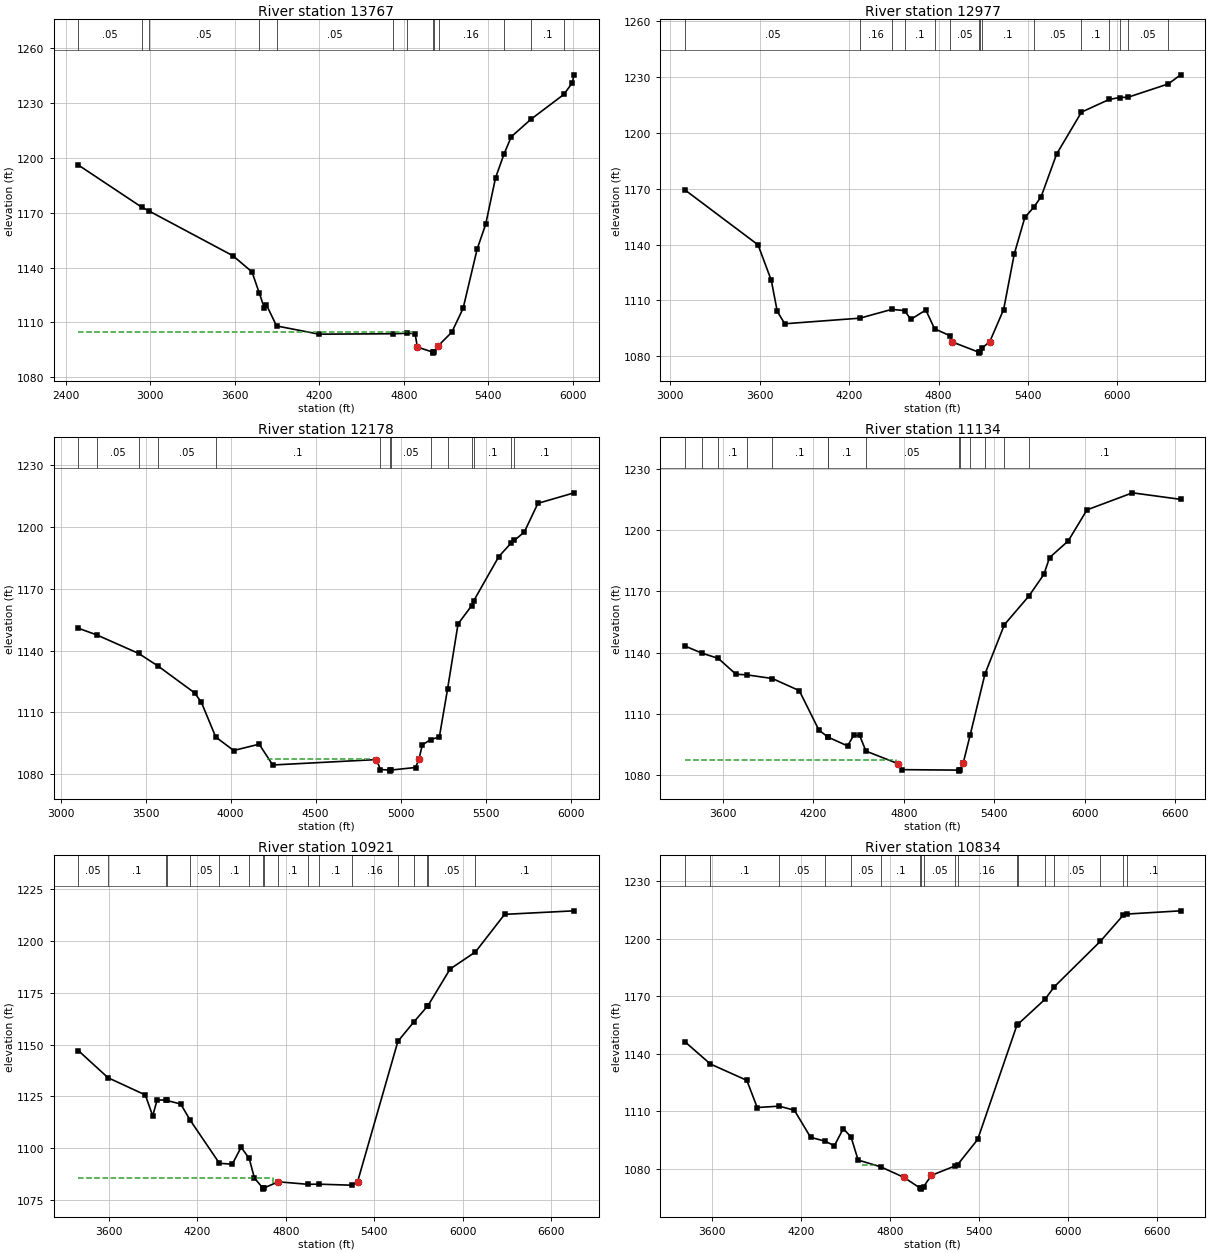
Type RM Length L Ch R = 1 ,13767   ,790,790,790
BEGIN DESCRIPTION:
YEAGER CREEK 22.0
END DESCRIPTION:
XS GIS Cut Line= 4
      2941082.93     10048505.27      2942798.23     10049678.89
      2943944.07     10049748.34      2944228.78     10049685.84
#Sta/Elev= 30
  2490.8 1196.16    2939 1173.16    2990 1171.09    3588 1146.46  3723.1 1137.61
  3775.5 1125.82  3809.8 1118.01  3824.7 1119.66  3897.4 1108.03  4198.5 1103.54
  4723.1 1103.76  4821.7 1104.02    4880 1103.81  4896.1 1096.48  5007.2 1093.65
    5010 1093.15  5013.2 1093.65  5040.3 1097.01  5046.3 1097.32  5140.5 1104.63
  5220.6 1117.64  5320.8 1150.26  5380.9 1163.71    5451 1189.21  5511.8 1202.34
  5562.3 1211.62  5702.6 1221.26  5935.8 1234.84    5994 1241.04  6008.6 1245.56
#Mann= 13 ,-1 , 0
  2490.8     .05       0    2939      .1       0    2990     .05       0
  3775.5      .1       0  3897.4     .05       0  4723.1     .16       0
  4821.7     .05       0  5007.2    .033       0  5013.2     .05       0
  5046.3     .16       0  5511.8     .05       0  5702.6      .1       0
  5935.8     .05       0
#XS Ineff= 2 , 0
         4860.31 1104.91
Permanent Ineff=
       T       T
Bank Sta=4896.1,5040.3
XS Rating Curve= 0 ,0
Exp/Cntr=0.3,0.1

Type RM Length L Ch R = 1 ,12977   ,799,799,799
BEGIN DESCRIPTION:
YEAGER CREEK 21.0
END DESCRIPTION:
XS GIS Cut Line= 3
      2941062.14     10050574.72      2942687.12     10050387.23
      2944304.34     10049894.43
#Sta/Elev= 30
  3097.3 1169.37  3588.8 1139.81  3677.8 1120.68  3717.7 1104.05  3768.1 1097.44
  4272.2 1100.45  4485.9 1105.16  4571.6 1104.52  4613.6  1099.8  4714.3 1104.82
    4773 1094.74  4877.5 1090.97  4891.3 1087.68  5069.6 1082.17  5072.3 1081.67
  5075.6 1082.17  5094.1 1084.56  5143.5 1087.86  5236.3 1105.08  5307.7 1134.94
  5378.6 1154.57  5437.4 1159.92  5487.5 1165.59  5591.7 1188.56  5758.5  1211.1
  5943.7 1217.89  6015.7 1218.95  6071.8 1219.12  6340.5 1226.23  6423.7 1231.13
#Mann= 15 ,-1 , 0
  3097.3     .05       0  4272.2     .16       0  4485.9     .05       0
  4571.6      .1       0    4773     .16       0  4877.5     .05       0
  5069.6    .033       0  5075.6     .05       0  5094.1      .1       0
  5437.4     .05       0  5758.5      .1       0  5943.7     .05       0
  6015.7      .1       0  6071.8     .05       0  6340.5      .1       0
Bank Sta=4891.3,5143.5
XS Rating Curve= 0 ,0
Exp/Cntr=0.3,0.1

Type RM Length L Ch R = 1 ,12178   ,1044,1044,1044
BEGIN DESCRIPTION:
YEAGER CREEK 19.0
END DESCRIPTION:
XS GIS Cut Line= 2
       2941214.9     10051060.84      2944131.59     10051067.78
#Sta/Elev= 30
  3104.7 1150.86  3214.7 1147.57  3459.2 1138.64  3572.9 1132.55  3788.3 1119.52
  3828.3 1114.96  3912.9 1098.08  4018.3 1091.53  4168.3 1094.59  4248.3  1084.5
  4858.3 1087.12  4881.8  1082.3  4935.3 1082.02    4938 1081.52  4941.3 1082.02
  5088.3 1083.28  5108.3 1087.32  5128.3 1094.25  5177.7 1096.86  5228.3 1098.07
  5276.4  1121.2  5338.3 1152.94  5417.6 1161.71    5431 1164.25  5578.3 1185.65
  5652.6  1192.4  5669.7 1193.47  5728.3 1197.58  5808.3 1211.47  6021.4 1216.57
#Mann= 14 ,-1 , 0
  3104.7      .1       0  3214.7     .05       0  3459.2      .1       0
  3572.9     .05       0  3912.9      .1       0  4881.8     .05       0
  4935.3    .033       0  4941.3     .05       0  5177.7     .16       0
  5276.4      .1       0  5417.6     .05       0    5431      .1       0
  5652.6     .05       0  5669.7      .1       0
#XS Ineff= 2 ,-1
 3979.79 4138.59 1093.51 4213.03 4849.07 1087.64
Permanent Ineff=
       T       T
Bank Sta=4858.3,5108.3
XS Rating Curve= 0 ,0
Exp/Cntr=0.3,0.1

Type RM Length L Ch R = 1 ,11134   ,213,213,213
BEGIN DESCRIPTION:
YEAGER CREEK 17.0
END DESCRIPTION:
XS GIS Cut Line= 3
      2941159.34     10052012.23      2943249.62     10051991.39
      2944291.31      10051401.1
#Sta/Elev= 30
  3347.2 1143.31  3462.3 1139.77  3569.3 1137.25  3686.3 1129.48  3758.4  1129.2
  3927.8  1127.4  4106.4 1121.47  4236.4 1102.18  4295.9 1098.79  4296.6 1098.76
  4426.4 1094.44  4466.4 1099.57  4506.4 1099.58  4548.1 1091.91 4759.14 1085.81
  4786.4 1082.83  5163.4 1082.61  5166.2 1082.11  5169.4 1082.61 5192.53 1085.85
  5239.1 1099.67  5337.8 1129.69  5466.4 1153.73  5629.5  1167.8  5728.2 1178.33
  5765.7 1186.52  5889.7 1194.69  6013.8 1209.86  6315.4 1218.21  6634.9 1215.02
#Mann= 14 ,-1 , 0
  3347.2     .16       0  3462.3     .05       0  3569.3      .1       0
  3758.4     .05       0  3927.8      .1       0  4295.9     .05       0
  4296.6      .1       0  4548.1     .05       0  5163.4    .033       0
  5169.4     .05       0  5239.1     .16       0  5337.8      .1       0
  5466.4     .05       0  5629.5      .1       0
#XS Ineff= 2 , 0
          4745.6 1087.57
Permanent Ineff=
       T       T
Bank Sta=4759.14,5192.53
XS Rating Curve= 0 ,0
Exp/Cntr=0.3,0.1

Type RM Length L Ch R = 1 ,10921   ,87,87,87
BEGIN DESCRIPTION:
Mapping XS 10b27ea1
END DESCRIPTION:
XS GIS Cut Line= 5
      2941193.89     10052182.09      2942535.07     10052158.65
       2943055.9     10052257.61      2943423.09     10052143.02
       2944292.9     10051455.51
#Sta/Elev= 30
    3392 1147.08  3593.7 1133.99  3846.6 1125.69  3896.7 1115.62  3926.7 1123.24
  3987.2 1123.23  3991.3 1123.07  4086.7 1121.32  4152.1 1113.42  4349.1 1092.77
  4436.7 1092.29  4496.7 1100.46  4551.6  1095.1  4586.8 1085.68  4643.8 1080.79
  4646.5 1080.29  4649.8 1080.79  4749.3 1083.82  4949.7 1082.61  5024.7 1082.68
  5247.4 1082.18  5287.2 1083.86  5560.8 1151.56  5669.2 1160.91  5760.5 1168.41
  5762.1 1168.43  5914.7 1186.39  6087.1 1194.65    6285 1212.77  6756.9 1214.47
#Mann= 18 ,-1 , 0
    3392     .05       0  3593.7      .1       0  3987.2     .05       0
  3991.3      .1       0  4152.1     .05       0  4349.1      .1       0
  4551.6     .05       0  4643.8    .033       0  4649.8     .05       0
  4749.3      .1       0  4949.7     .05       0  5024.7      .1       0
  5247.4     .16       0  5560.8      .1       0  5669.2     .05       0
  5760.5      .1       0  5762.1     .05       0  6087.1      .1       0
#XS Ineff= 2 , 0
         4716.45 1085.74
Permanent Ineff=
       T       T
Bank Sta=4749.3,5287.2
XS Rating Curve= 0 ,0
Exp/Cntr=0.3,0.1

Type RM Length L Ch R = 1 ,10834   ,96,96,96
BEGIN DESCRIPTION:
Mapping XS 91e1d71d
END DESCRIPTION:
XS GIS Cut Line= 5
      2941230.35     10052221.15       2942493.4     10052208.13
      2942897.05     10052320.11      2943355.38     10052291.46
      2944269.45     10051512.81
#Sta/Elev= 30
  3414.5 1146.36  3586.7  1134.7  3832.6 1126.15  3902.6 1111.98  4050.3 1112.69
  4152.7 1110.58  4262.7 1096.41  4359.9 1094.42  4422.7 1092.04  4482.7 1100.99
  4535.5 1096.51  4582.7 1084.56  4734.3 1081.05  4890.4 1075.57  5001.6 1069.89
  5004.3 1069.39  5007.6 1069.89  5024.1 1070.67  5077.2 1076.59    5238 1081.55
  5253.2 1082.15  5388.5  1095.3  5653.7 1155.09  5661.7 1155.57  5842.4 1168.47
  5904.3 1174.94  6215.7 1198.75  6370.3 1212.42  6393.5 1212.94  6756.5 1214.63
#Mann= 18 ,-1 , 0
  3414.5     .05       0  3586.7      .1       0  4050.3     .05       0
  4359.9      .1       0  4535.5     .05       0  4734.3      .1       0
  5001.6     .07       0  5007.6      .1       0  5024.1     .05       0
    5238      .1       0  5253.2     .16       0  5653.7      .1       0
  5661.7     .05       0  5842.4      .1       0  5904.3     .05       0
  6215.7      .1       0  6370.3     .05       0  6393.5      .1       0
#XS Ineff= 3 ,-1
 4608.34 4712.59 1082.22 4714.91  4725.4 1081.25 4749.28 4765.58 1079.77
Permanent Ineff=
       T       T       T
Bank Sta=4890.4,5077.2
XS Rating Curve= 0 ,0
Exp/Cntr=0.3,0.1

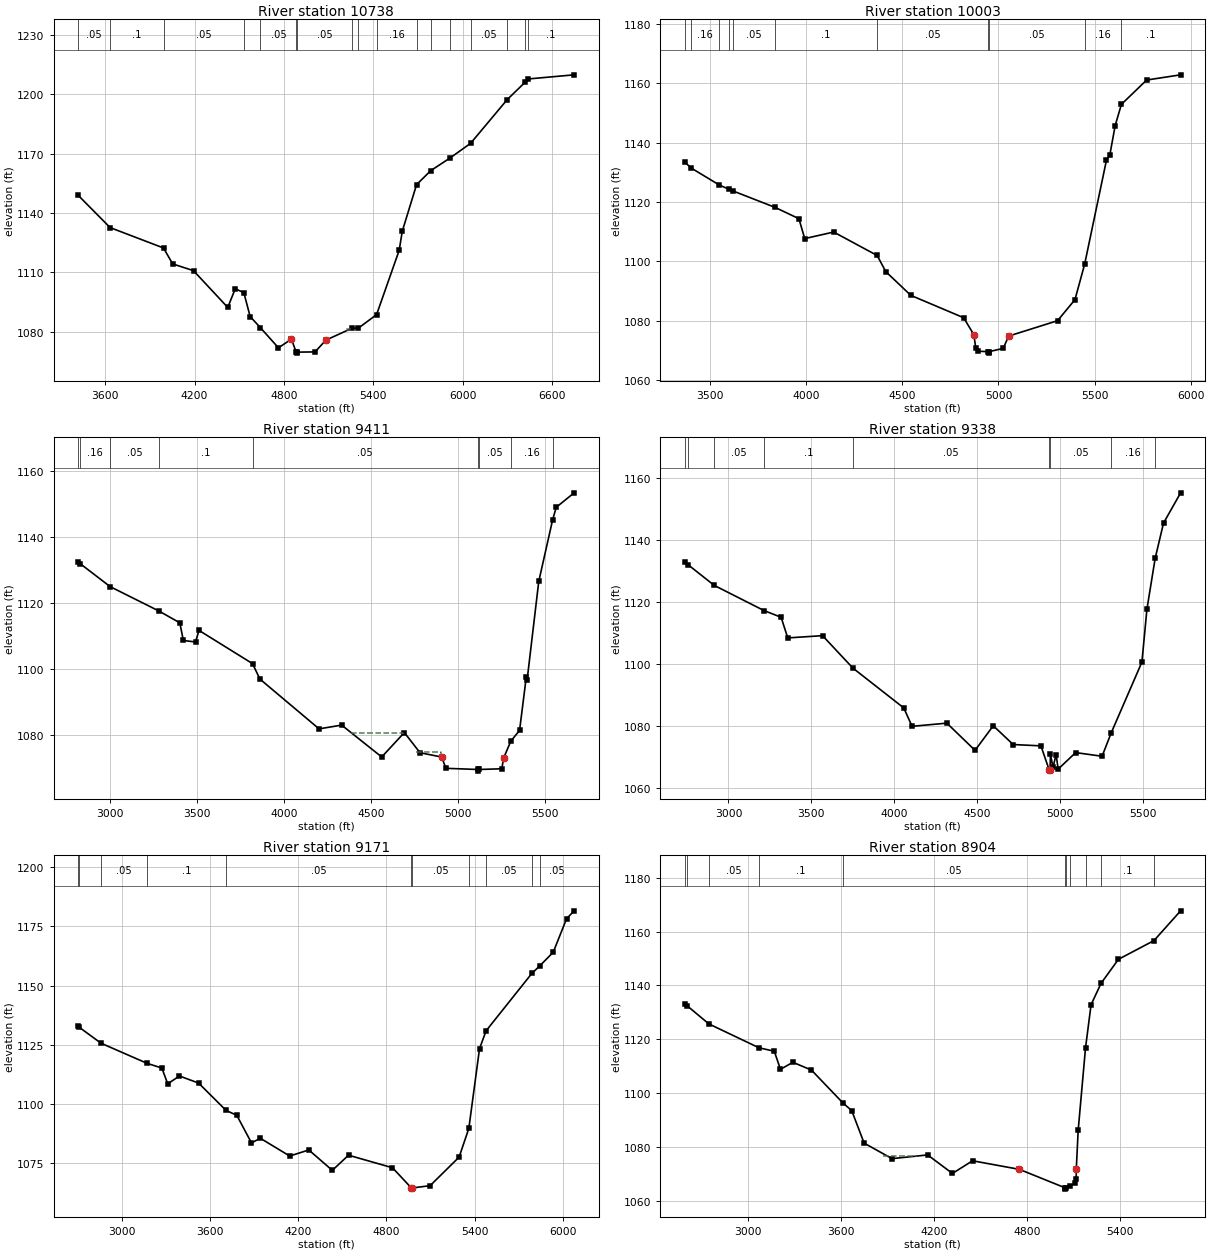
Type RM Length L Ch R = 1 ,10738   ,735,735,735
BEGIN DESCRIPTION:
Mapping XS 4701b3b0
END DESCRIPTION:
XS GIS Cut Line= 5
      2941235.58     10052320.97      2942628.82     10052329.66
      2942910.94      10052399.1      2943362.32     10052360.04
      2944303.78     10051631.17
#Sta/Elev= 30
  3420.2 1148.83  3633.7 1132.58  3991.9 1122.28  4053.1 1114.23  4193.1  1110.8
  4423.1  1092.2  4473.1 1101.64  4530.9 1099.71  4573.1 1087.62  4642.7 1081.91
  4763.1 1071.79  4850.3 1076.17  4882.2  1069.6  4884.9  1069.1  4888.2  1069.6
  5008.8 1069.72  5080.9 1075.64  5257.5 1081.72  5299.8 1081.75  5421.8 1088.58
  5573.4  1121.1  5594.2 1130.75  5690.2 1154.33  5785.7 1161.41  5913.3 1167.72
  6052.3 1175.17  6298.6 1197.33  6417.3 1206.02  6438.8 1207.76  6747.7 1209.85
#Mann= 17 ,-1 , 0
  3420.2     .05       0  3633.7      .1       0  3991.9     .05       0
  4530.9      .1       0  4642.7     .05       0  4882.2    .033       0
  4888.2     .05       0  5257.5      .1       0  5299.8     .05       0
  5421.8     .16       0  5690.2      .1       0  5785.7     .05       0
  5913.3      .1       0  6052.3     .05       0  6298.6      .1       0
  6417.3     .05       0  6438.8      .1       0
#XS Ineff= 1 ,-1
 5220.73 5251.41 1081.17
Permanent Ineff=
       T
Bank Sta=4850.3,5080.9
XS Rating Curve= 0 ,0
Exp/Cntr=0.3,0.1

Type RM Length L Ch R = 1 ,10003   ,592,592,592
BEGIN DESCRIPTION:
YEAGER CREEK 16.0
END DESCRIPTION:
XS GIS Cut Line= 4
      2941687.01     10053158.65      2943132.29     10053050.14
      2943501.21     10052286.25      2943769.28     10052208.43
#Sta/Elev= 30
  3369.8 1133.47  3401.9 1131.51  3549.3 1125.75  3600.4 1124.28  3622.6 1123.69
  3839.3 1118.21  3962.9 1114.41    3993 1107.71  4143.4 1109.92  4369.6 1102.02
  4414.2  1096.6  4544.6 1088.59  4819.1 1081.07    4872 1075.35  4881.8 1070.89
  4894.6 1069.79  4945.4 1069.65  4948.2 1069.15  4951.4 1069.65  5024.7 1070.75
  5052.9 1074.89    5307 1080.07  5397.4 1087.15  5447.5 1099.01  5561.2 1134.12
  5578.3 1135.73  5606.4 1145.75  5638.8 1152.91  5770.1  1161.1  5946.6 1162.85
#Mann= 11 ,-1 , 0
  3369.8     .05       0  3401.9     .16       0  3549.3     .05       0
  3600.4      .1       0  3622.6     .05       0  3839.3      .1       0
  4369.6     .05       0  4945.4    .033       0  4951.4     .05       0
  5447.5     .16       0  5638.8      .1       0
Bank Sta=4872,5052.9
XS Rating Curve= 0 ,0
Exp/Cntr=0.3,0.1

Type RM Length L Ch R = 1 ,9411    ,73,73,73
BEGIN DESCRIPTION:
Mapping XS 17eda15b
END DESCRIPTION:
XS GIS Cut Line= 4
      2941705.16     10053201.62      2943744.18     10053175.58
      2943785.85     10052956.83      2943744.18     10052370.87
#Sta/Elev= 30
  2819.6 1132.39  2831.5 1131.86  3002.5 1124.96  3284.2 1117.54  3402.9    1114
    3423 1108.66    3493 1108.21    3513 1111.71  3820.8 1101.65    3863 1096.98
    4203 1081.91    4333 1083.04    4563 1073.39  4693.1 1080.79  4783.1 1074.68
  4907.4 1073.38  4931.9 1069.96  5114.4 1069.61  5117.1 1069.11  5120.4 1069.61
    5253 1069.82  5263.8  1073.1  5304.7 1078.15  5355.2 1081.45  5393.7 1097.59
  5398.7 1096.75  5465.5 1126.55  5544.6 1145.06  5565.8 1148.98  5668.9 1153.36
#Mann= 9 ,-1 , 0
  2819.6     .05       0  2831.5     .16       0  3002.5     .05       0
  3284.2      .1       0  3820.8     .05       0  5114.4    .035       0
  5120.4     .05       0  5304.7     .16       0  5544.6      .1       0
#XS Ineff= 2 ,-1
  4387.3 4683.49 1080.75 4759.61 4901.29 1074.77
Permanent Ineff=
       T       T
Bank Sta=4907.4,5263.8
XS Rating Curve= 0 ,0
Exp/Cntr=0.3,0.1

Type RM Length L Ch R = 1 ,9338    ,167,167,167
BEGIN DESCRIPTION:
Mapping XS b85bf989
END DESCRIPTION:
XS GIS Cut Line= 4
      2941697.27     10053225.05      2943793.66     10053204.22
      2943871.79     10052925.58      2943905.38     10052320.59
#Sta/Elev= 30
  2736.7 1132.92  2755.5 1132.06  2914.2 1125.37  3214.1 1117.27  3317.9 1115.09
  3357.9 1108.44  3567.9 1109.17  3751.4  1098.7    4058 1085.88    4108 1079.96
    4318 1080.98    4488 1072.21    4598 1080.14    4718 1074.09  4885.6 1073.66
  4934.6 1066.02  4937.3 1065.52  4940.6 1066.02  4943.2 1070.97  4958.3 1066.77
  4977.3 1070.84  4989.5 1066.17  5095.1 1071.49  5254.6 1070.31  5309.5 1077.83
    5495 1100.66    5525 1117.64  5574.9 1134.09  5625.2 1145.43  5728.5 1155.19
#Mann= 9 ,-1 , 0
  2736.7     .05       0  2755.5     .16       0  2914.2     .05       0
  3214.1      .1       0  3751.4     .05       0  4934.6    .035       0
  4940.6     .05       0  5309.5     .16       0  5574.9      .1       0
Bank Sta=4934.6,4940.6
XS Rating Curve= 0 ,0
Exp/Cntr=0.3,0.1

Type RM Length L Ch R = 1 ,9171    ,267,267,267
BEGIN DESCRIPTION:
Mapping XS d8c4d111
END DESCRIPTION:
XS GIS Cut Line= 4
      2941710.32     10053243.28      2943827.52     10053219.85
      2944393.22     10052888.12      2944964.77     10052703.66
#Sta/Elev= 30
  2703.6 1132.99  2708.6 1132.46  2857.9 1125.68  3171.6 1117.17  3271.8 1115.19
  3311.8 1108.54  3391.8 1111.83  3521.8 1108.84  3708.9 1097.29  3781.8 1095.23
  3881.8 1083.57  3941.8 1085.54  4141.8 1078.03  4271.8 1080.59  4431.9 1071.97
  4541.9 1078.38  4841.2 1073.08  4969.7 1064.55  4972.5 1064.05  4975.7 1064.55
  5097.2 1065.51  5294.6 1077.58  5360.7 1089.73  5433.3 1123.35  5477.9  1130.9
  5789.2 1155.14  5843.7 1158.37  5934.9 1164.11  6025.8 1178.27  6077.3 1181.59
#Mann= 11 ,-1 , 0
  2703.6     .05       0  2708.6     .16       0  2857.9     .05       0
  3171.6      .1       0  3708.9     .05       0  4969.7    .035       0
  4975.7     .05       0  5360.7     .16       0  5477.9     .05       0
  5789.2      .1       0  5843.7     .05       0
Bank Sta=4969.7,4975.7
XS Rating Curve= 0 ,0
Exp/Cntr=0.3,0.1

Type RM Length L Ch R = 1 ,8904    ,705,705,705
BEGIN DESCRIPTION:
YEAGER CREEK 15.0
END DESCRIPTION:
XS GIS Cut Line= 3
      2941700.97     10053255.28      2943784.34     10053269.17
      2944873.07     10053518.81
#Sta/Elev= 30
  2591.4 1133.26  2605.2 1132.53  2746.9 1125.73  3070.9 1116.87  3168.9 1115.61
  3208.9 1108.88  3288.9 1111.51  3408.9 1108.61  3612.3  1096.4  3668.9 1093.57
  3748.9 1081.51  3928.9 1075.75  4158.9 1077.13  4318.9 1070.26  4448.9 1074.96
  4750.9 1071.78  5045.4 1064.94  5048.1 1064.44  5051.4 1064.94  5077.6 1065.51
    5110 1066.61  5117.7 1068.38 5118.38 1071.89  5130.5 1086.26  5177.9 1116.82
  5213.7 1132.85  5278.1 1140.79  5390.4 1149.71  5619.8 1156.66  5791.8  1167.7
#Mann= 11 ,-1 , 0
  2591.4     .05       0  2605.2     .16       0  2746.9     .05       0
  3070.9      .1       0  3612.3     .05       0  5045.4    .033       0
  5051.4     .05       0  5077.6      .1       0  5177.9     .05       0
  5278.1      .1       0  5619.8     .05       0
#XS Ineff= 2 ,-1
 3872.25 4087.47 1076.79  4195.9  4448.9 1074.88
Permanent Ineff=
       T       T
Bank Sta=4750.9,5118.38
XS Rating Curve= 0 ,0
Exp/Cntr=0.3,0.1