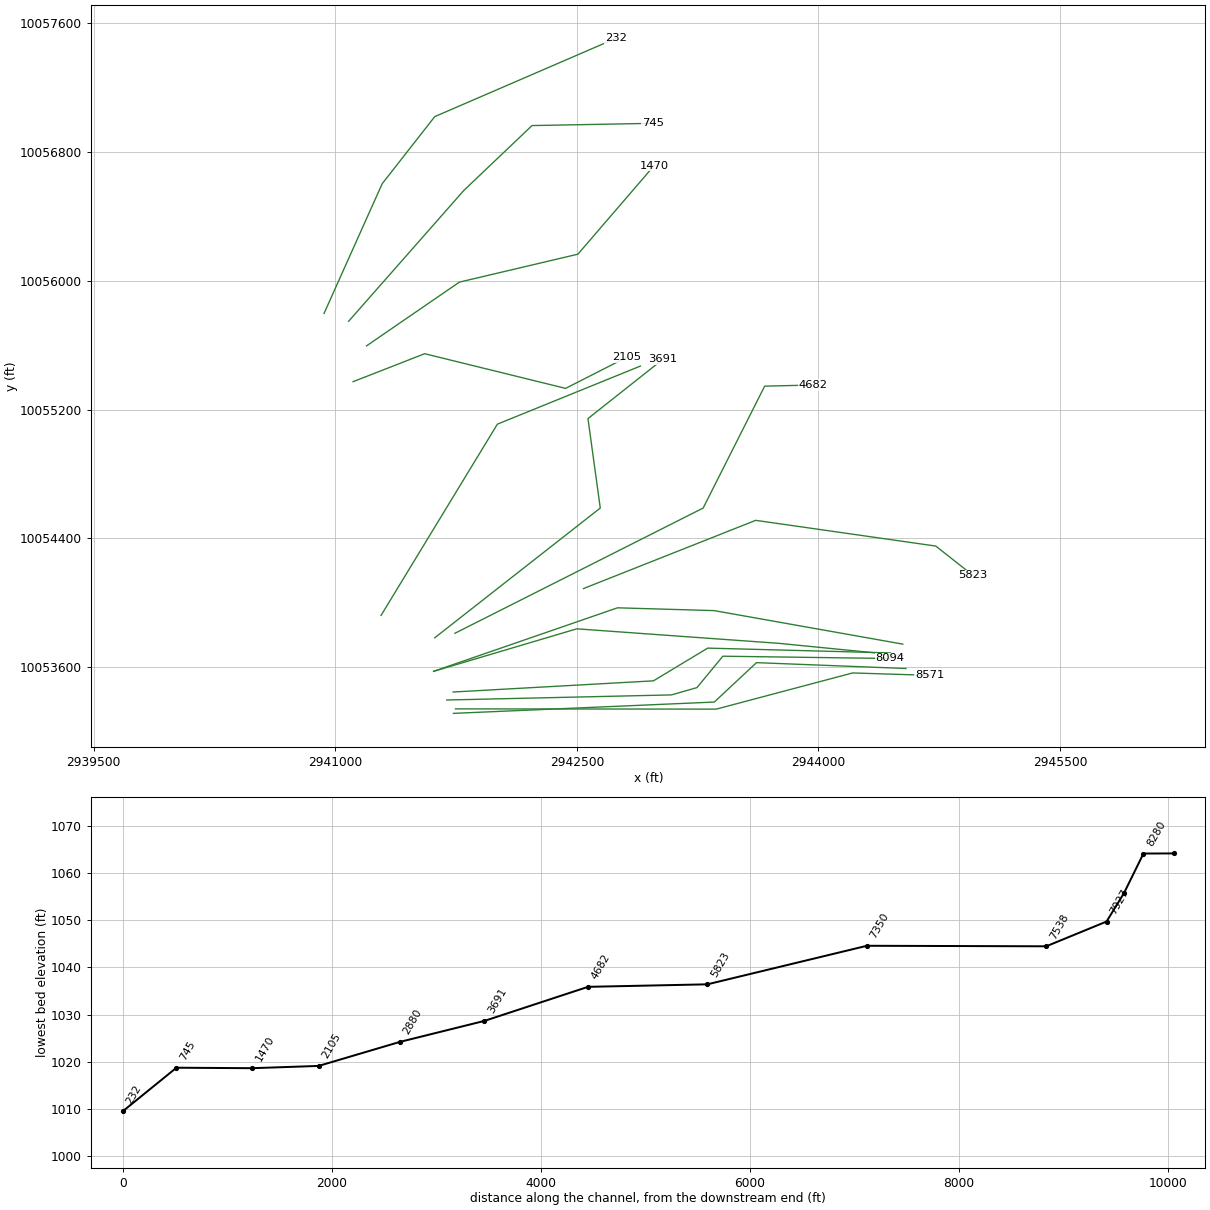
HEC-RAS study YEAGER CREEK.prj: YEAGER CREEK Base Level Engineering

--- YEAGER CREEK.g01 (geometry) --- (continued)

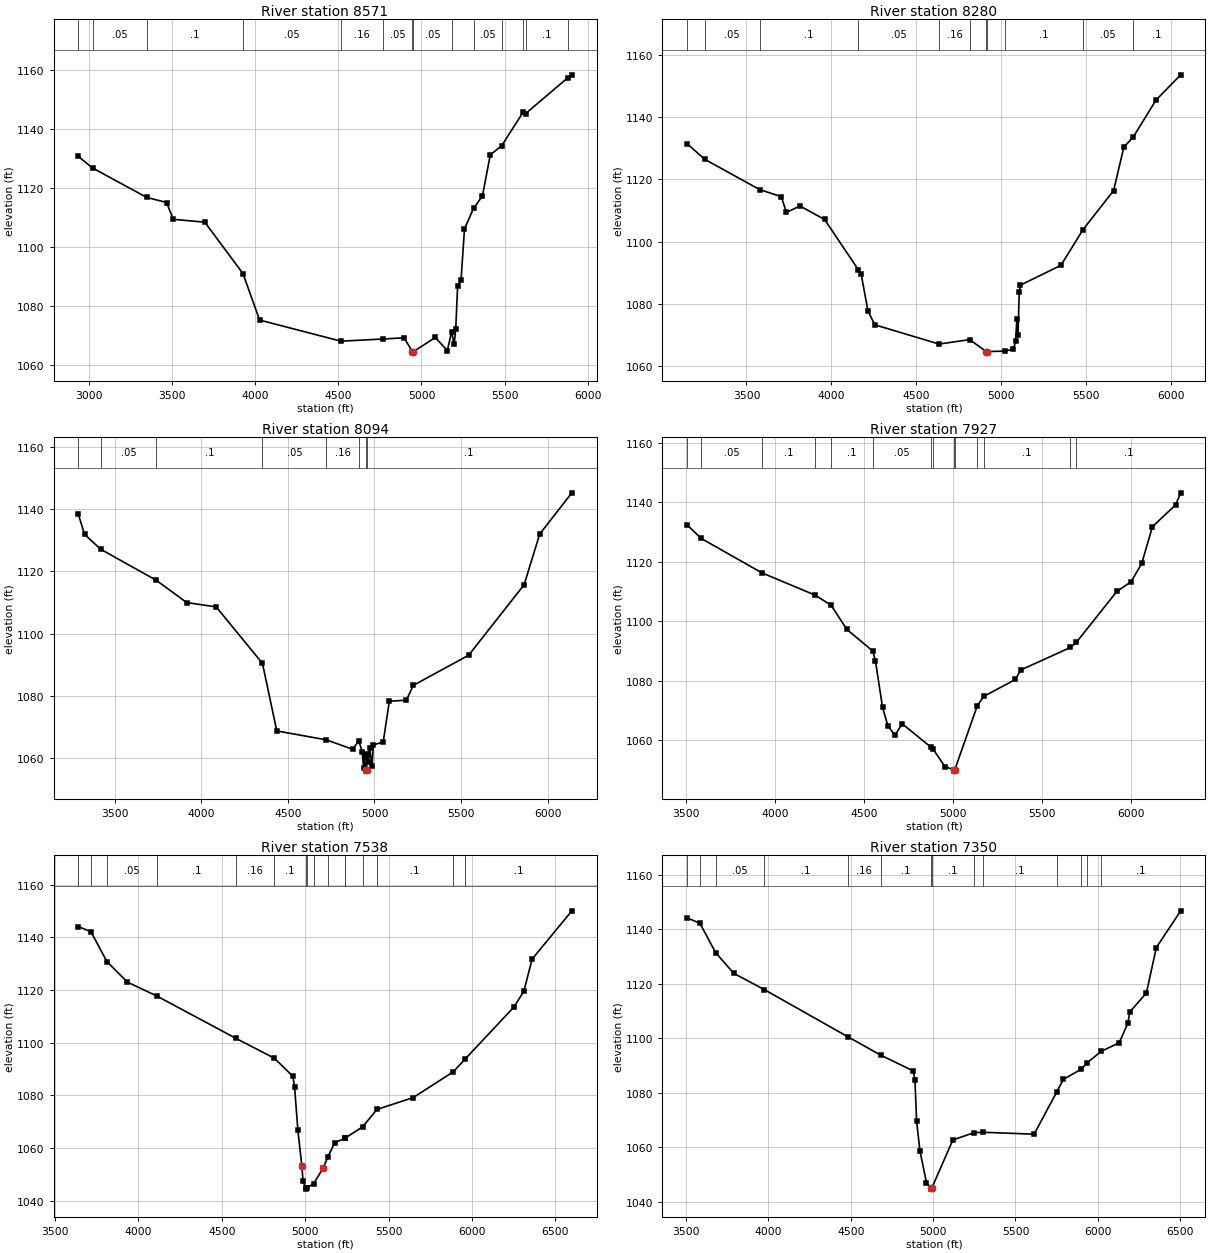
Type RM Length L Ch R = 1 ,8571    ,291,291,291
BEGIN DESCRIPTION:
Mapping XS ad354517
END DESCRIPTION:
XS GIS Cut Line= 4
      2941746.51     10053341.46      2943365.91     10053340.03
      2944212.55     10053564.66      2944689.18     10053549.79
#Sta/Elev= 30
  2933.4 1130.72  3019.5 1126.77    3345 1116.83  3465.4 1115.08  3505.4 1109.39
  3695.4 1108.43  3925.5 1091.02  4025.4  1075.3  4515.8 1068.15  4766.3 1068.89
  4895.2  1069.3  4945.6 1064.61  4948.3 1064.11  4951.6 1064.61  5083.1  1069.4
  5155.5 1064.98  5181.5 1071.26  5196.9 1067.08  5206.4 1072.37  5217.6 1086.66
  5238.3 1088.92    5259 1106.17  5313.4 1113.08  5367.1 1117.31  5414.2 1131.18
  5483.2 1134.34    5613 1145.72  5627.2 1145.18  5882.8 1157.38  5905.6 1158.29
#Mann= 14 ,-1 , 0
  2933.4     .16       0  3019.5     .05       0    3345      .1       0
  3925.5     .05       0  4515.8     .16       0  4766.3     .05       0
  4945.6    .033       0  4951.6     .05       0  5181.5      .1       0
  5313.4     .05       0  5483.2      .1       0    5613     .05       0
  5627.2      .1       0  5882.8     .05       0
Bank Sta=4945.6,4951.6
XS Rating Curve= 0 ,0
Exp/Cntr=0.3,0.1

Type RM Length L Ch R = 1 ,8280    ,186,186,186
BEGIN DESCRIPTION:
Mapping XS 8d80a9d9
END DESCRIPTION:
XS GIS Cut Line= 4
      2941733.81      10053313.6      2943353.56     10053383.91
      2943615.68     10053628.63      2944543.59     10053592.24
#Sta/Elev= 30
  3150.3 1131.53  3253.9  1126.5  3577.4 1116.76  3705.5 1114.45  3735.5 1109.39
  3815.6 1111.46  3960.6 1107.11  4159.6 1090.91  4175.9 1089.53    4216 1077.67
    4256  1073.2  4635.6    1067  4815.1 1068.43  4913.2 1064.58    4916 1064.08
  4919.2 1064.58  5020.5 1064.73  5072.1 1065.32  5086.2 1067.83  5093.1 1075.04
  5100.4 1070.05  5107.2 1083.79  5114.6 1085.98  5353.1 1092.36  5483.5 1103.87
  5663.4 1116.43  5723.4 1130.36  5780.2 1133.77  5913.6 1145.59  6058.8 1153.69
#Mann= 11 ,-1 , 0
  3150.3     .16       0  3253.9     .05       0  3577.4      .1       0
  4159.6     .05       0  4635.6     .16       0  4815.1     .05       0
  4913.2    .033       0  4919.2     .05       0  5020.5      .1       0
  5483.5     .05       0  5780.2      .1       0
Bank Sta=4913.2,4919.2
XS Rating Curve= 0 ,0
Exp/Cntr=0.3,0.1

Type RM Length L Ch R = 1 ,8094    ,167,167,167
BEGIN DESCRIPTION:
Mapping XS 8d4a81cf
END DESCRIPTION:
XS GIS Cut Line= 5
        2941692.     10053396.66      2943087.03     10053428.24
      2943245.73     10053473.48      2943406.76     10053668.57
      2944444.29     10053654.38
#Sta/Elev= 30
  3289.3 1138.48  3325.8 1131.92  3418.3 1127.14  3739.6 1117.14  3915.9 1109.96
    4086 1108.56  4353.2  1090.4  4436.1 1068.65  4721.5  1065.8  4873.5 1062.75
  4909.9 1065.43  4929.5 1061.87  4937.4 1056.58  4943.8 1060.13  4948.7 1056.22
  4951.4 1055.72  4954.7 1056.22  4958.2 1061.36    4966 1058.59  4972.5 1063.14
  4986.9 1057.39  4993.3 1064.16  5050.7 1065.09  5085.9 1078.21  5184.4 1078.54
  5224.4 1083.31  5544.4 1093.03  5864.4 1115.69  5954.5 1132.01  6140.3 1145.27
#Mann= 8 ,-1 , 0
  3289.3     .16       0  3418.3     .05       0  3739.6      .1       0
  4353.2     .05       0  4721.5     .16       0  4909.9      .1       0
  4948.7     .07       0  4954.7      .1       0
Bank Sta=4948.7,4954.7
XS Rating Curve= 0 ,0
Exp/Cntr=0.3,0.1

Type RM Length L Ch R = 1 ,7927    ,577,577,577
BEGIN DESCRIPTION:
Mapping XS c052af2c
END DESCRIPTION:
XS GIS Cut Line= 4
      2941731.68     10053446.22      2942975.62      10053515.6
      2943312.63      10053718.8      2944447.54     10053689.07
#Sta/Elev= 30
  3505.6 1132.42  3584.9 1127.87  3928.1 1116.25  4225.3 1108.82  4315.3 1105.41
  4403.8 1097.28  4548.9 1090.06    4564 1086.85  4604.1 1071.19  4634.1 1064.93
  4674.2 1061.69  4714.3 1065.62  4878.3 1057.64  4887.3  1057.2  4955.2 1051.16
  5004.6 1050.19  5007.3 1049.69  5010.6 1050.19  5137.1 1071.69  5173.5  1074.8
  5350.9 1080.48  5380.9 1083.66  5660.6 1091.24  5693.9 1092.97  5921.1 1110.05
  6001.1 1113.29  6061.2 1119.48  6121.2  1131.8  6251.2 1139.13  6280.3 1143.19
#Mann= 14 ,-1 , 0
  3505.6     .16       0  3584.9     .05       0  3928.1      .1       0
  4225.3     .16       0  4315.3      .1       0  4548.9     .05       0
  4878.3     .16       0  4887.3      .1       0  5004.6     .07       0
  5010.6      .1       0  5137.1     .05       0  5173.5      .1       0
  5660.6     .16       0  5693.9      .1       0
Bank Sta=5004.6,5010.6
XS Rating Curve= 0 ,0
Exp/Cntr=0.3,0.1

Type RM Length L Ch R = 1 ,7538    ,1715,1715,1715
BEGIN DESCRIPTION:
YEAGER CREEK 14.0
END DESCRIPTION:
XS GIS Cut Line= 4
      2941610.71     10053574.72      2942499.62     10053838.61
      2943756.57     10053748.34      2944525.46     10053672.14
#Sta/Elev= 30
  3638.8 1144.12  3714.9 1142.18  3811.5 1130.76  3933.9 1123.02  4110.9 1117.73
  4584.2 1101.69  4815.3 1094.12  4925.8 1087.27  4935.9 1083.36  4955.9 1066.85
 4979.55 1053.22  4987.1  1047.4    5003 1044.95  5005.8 1044.45    5009 1044.95
  5050.1 1046.47  5106.3 1052.34  5136.4 1056.79  5176.5 1062.05  5236.5 1063.73
  5240.1 1063.85  5344.2 1068.11  5429.9 1074.69  5647.7 1079.21    5888 1088.99
  5957.2 1093.71  6250.2 1113.49  6310.5 1119.49  6360.7  1131.8  6598.9 1150.09
#Mann= 16 ,-1 , 0
  3638.8      .1       0  3714.9     .16       0  3811.5     .05       0
  4110.9      .1       0  4584.2     .16       0  4815.3      .1       0
    5003     .07       0    5009      .1       0  5050.1     .05       0
  5136.4      .1       0  5236.5     .05       0  5240.1      .1       0
  5344.2     .05       0  5429.9      .1       0    5888     .16       0
  5957.2      .1       0
Bank Sta=4979.55,5106.3
XS Rating Curve= 0 ,0
Exp/Cntr=0.3,0.1

Type RM Length L Ch R = 1 ,7350    ,1527,1527,1527
BEGIN DESCRIPTION:
YEAGER CREEK 14.0
END DESCRIPTION:
XS GIS Cut Line= 4
      2941610.74     10053574.73      2942752.59     10053969.09
      2943352.28     10053951.74      2944523.97     10053743.66
#Sta/Elev= 30
  3505.5 1144.12    3583 1142.22    3679 1131.39  3788.5  1123.8  3974.9 1117.81
  4480.7 1100.54  4682.2 1093.73  4879.5 1087.95  4889.5 1084.53  4899.5 1069.49
  4919.5 1058.63  4959.5 1046.94  4986.5 1045.06  4989.3 1044.56  4992.5 1045.06
  5119.6 1062.61  5248.2 1065.29  5301.8 1065.44  5612.9 1064.73  5749.7 1080.15
  5790.1 1084.82  5899.3  1088.6  5934.6 1090.92  6021.4 1095.18  6129.3 1098.27
  6183.1 1105.53  6193.4 1109.56  6294.8 1116.54  6355.4 1133.27  6503.5 1146.74
#Mann= 14 ,-1 , 0
  3505.5      .1       0    3583     .16       0    3679     .05       0
  3974.9      .1       0  4480.7     .16       0  4682.2      .1       0
  4986.5     .07       0  4992.5      .1       0  5248.2     .05       0
  5301.8      .1       0  5749.7     .16       0  5899.3      .1       0
  5934.6     .16       0  6021.4      .1       0
Bank Sta=4986.5,4992.5
XS Rating Curve= 0 ,0
Exp/Cntr=0.3,0.1

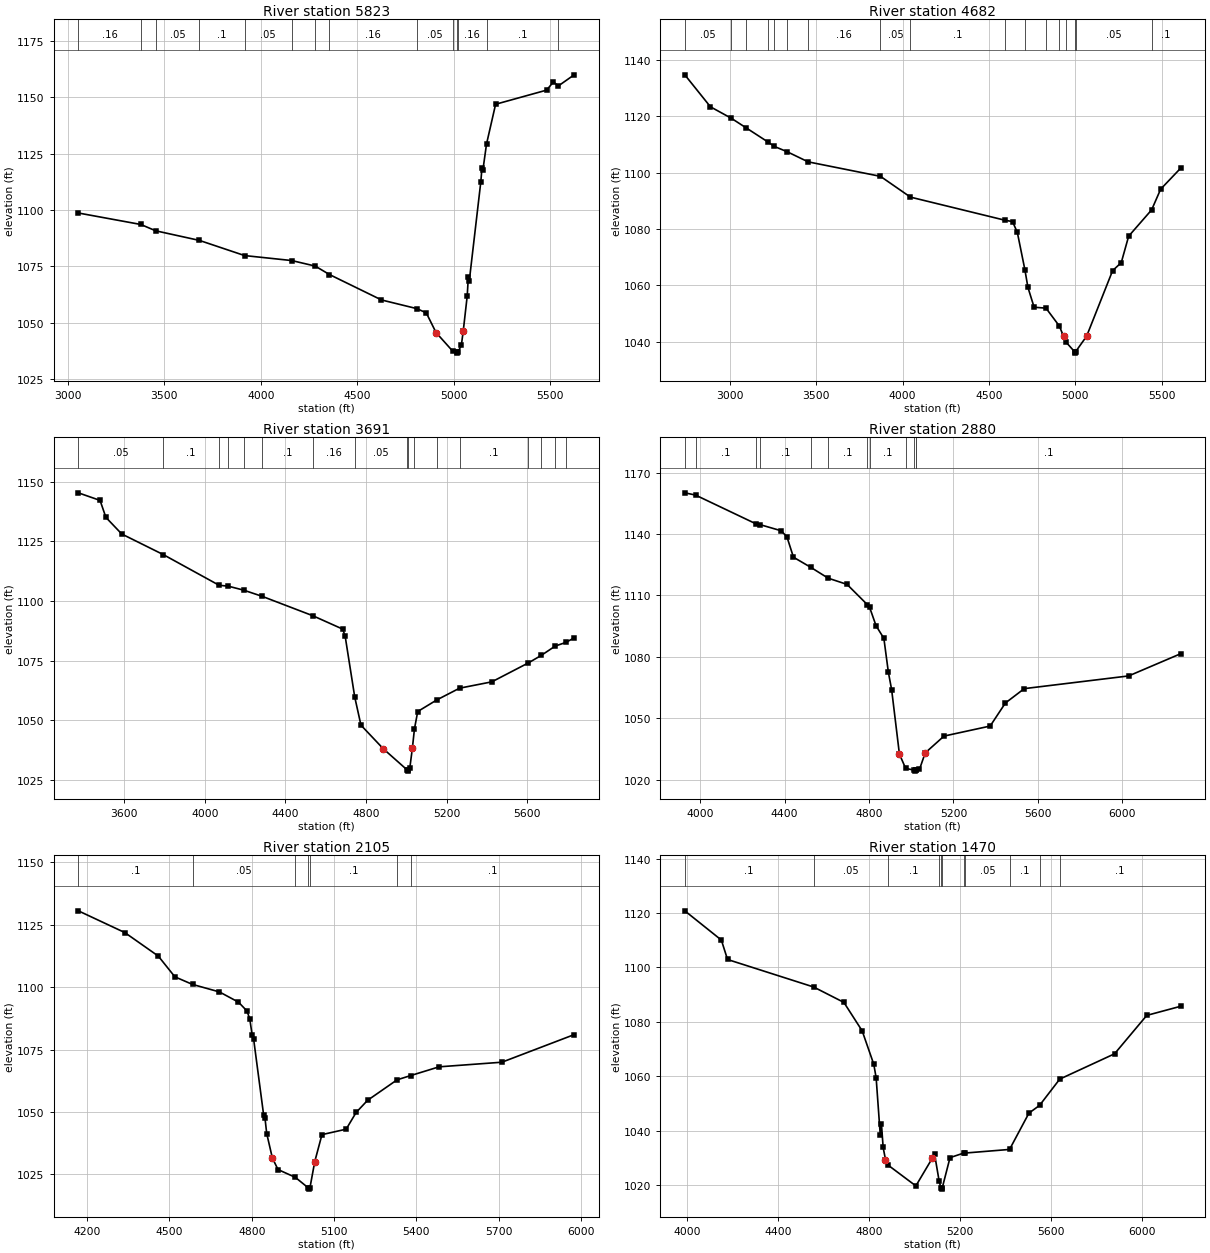
Type RM Length L Ch R = 1 ,5823    ,1141,1141,1141
BEGIN DESCRIPTION:
YEAGER CREEK 11.0
END DESCRIPTION:
XS GIS Cut Line= 4
      2942541.33     10054088.63      2943610.73     10054512.23
      2944728.79      10054352.5      2944957.95     10054171.95
#Sta/Elev= 30
  3053.6 1098.67  3377.7 1093.57  3454.8 1090.76  3681.5 1086.49    3916 1079.75
  4160.2 1077.54  4282.2 1075.08    4356 1071.32  4625.8 1060.03  4809.8 1056.16
  4858.2 1054.27  4908.7 1045.55  4996.5 1037.15  5016.8  1036.9  5019.5  1036.4
  5022.8  1036.9    5040 1039.94  5050.1 1046.45  5070.3 1061.74  5076.2 1070.26
  5081.3 1068.65    5141 1112.59  5146.9 1118.74    5152 1117.92  5170.5 1129.32
  5217.6 1146.99    5482 1153.27  5517.3 1156.91  5543.2 1155.15    5625 1160.07
#Mann= 14 ,-1 , 0
  3053.6     .16       0  3377.7      .1       0  3454.8     .05       0
  3681.5      .1       0    3916     .05       0  4160.2      .1       0
  4282.2     .05       0    4356     .16       0  4809.8     .05       0
  4996.5     .16       0  5016.8     .07       0  5022.8     .16       0
  5170.5      .1       0  5543.2     .05       0
Bank Sta=4908.7,5050.1
XS Rating Curve= 0 ,0
Exp/Cntr=0.3,0.1

Type RM Length L Ch R = 1 ,4682    ,991,991,991
BEGIN DESCRIPTION:
YEAGER CREEK 9.0
END DESCRIPTION:
XS GIS Cut Line= 4
      2941742.67     10053810.83      2943284.34     10054588.61
      2943666.29     10055345.56       2943964.2     10055352.49
#Sta/Elev= 30
  2738.2 1134.81  2886.8 1123.44  3007.6 1119.37  3093.1 1115.98  3219.6 1110.95
  3257.8 1109.33  3330.8 1107.48  3452.7 1103.87  3871.8 1098.72  4045.6 1091.33
  4593.5 1083.11  4636.9 1082.64  4664.8 1078.78  4708.4 1065.56  4726.1 1059.26
  4761.9 1052.19  4830.8 1051.86  4908.1 1045.51  4932.4 1041.86  4946.5 1039.82
  4996.3 1036.37    4999 1035.87  5002.3 1036.37  5066.2 1041.89  5216.7 1065.19
  5266.9 1068.05  5309.7 1077.45  5442.9 1086.81    5495 1094.15  5610.8 1101.61
#Mann= 17 ,-1 , 0
  2738.2     .05       0  3007.6      .1       0  3093.1     .16       0
  3219.6      .1       0  3257.8     .16       0  3330.8      .1       0
  3452.7     .16       0  3871.8     .05       0  4045.6      .1       0
  4593.5     .16       0  4708.4      .1       0  4830.8     .16       0
  4908.1      .1       0  4946.5     .05       0  4996.3    .035       0
  5002.3     .05       0  5442.9      .1       0
Bank Sta=4932.4,5066.2
XS Rating Curve= 0 ,0
Exp/Cntr=0.3,0.1

Type RM Length L Ch R = 1 ,3691    ,811,811,811
BEGIN DESCRIPTION:
YEAGER CREEK 7.0
END DESCRIPTION:
XS GIS Cut Line= 4
      2941617.65     10053783.03      2942645.46     10054588.61
      2942569.07     10055144.17      2943033.93      10055511.9
#Sta/Elev= 30
    3373 1145.42  3480.8 1142.24  3509.7 1135.12  3588.3 1128.15  3794.7 1119.49
  4071.4 1106.63  4116.1 1106.27  4192.7  1104.6  4284.6    1102  4536.3 1093.85
  4684.1 1088.25  4696.3 1085.38  4744.1 1059.72  4774.9 1047.94  4885.9 1038.02
  5004.1 1029.16  5006.8 1028.66  5010.1 1029.16  5017.2    1030 5030.11  1038.4
  5040.3 1046.44  5056.5 1053.67  5151.2 1058.54    5264 1063.46  5424.1 1066.12
  5605.4 1074.07  5668.9  1077.2  5738.8 1081.14  5790.6 1082.64  5832.4 1084.55
#Mann= 17 ,-1 , 0
    3373     .05       0  3794.7      .1       0  4071.4     .16       0
  4116.1      .1       0  4192.7     .16       0  4284.6      .1       0
  4536.3     .16       0  4744.1     .05       0  5004.1    .035       0
  5010.1     .05       0  5040.3      .1       0  5151.2     .05       0
    5264      .1       0  5605.4     .05       0  5668.9      .1       0
  5738.8     .05       0  5790.6      .1       0
Bank Sta=4885.9,5030.11
XS Rating Curve= 0 ,0
Exp/Cntr=0.3,0.1

Type RM Length L Ch R = 1 ,2880    ,775,775,775
BEGIN DESCRIPTION:
YEAGER CREEK 5.0
END DESCRIPTION:
XS GIS Cut Line= 3
      2941284.34     10053921.94      2942006.57     10055109.45
      2942894.41     10055470.14
#Sta/Elev= 30
  3927.7 1160.08  3978.4 1158.99  4264.7 1144.94  4284.4 1144.54  4384.1 1141.56
  4411.3 1138.62  4442.3 1128.64  4524.7 1123.68  4606.4 1118.42  4696.1 1115.37
  4792.8 1105.43  4802.8 1104.21  4833.7 1095.13  4870.5 1089.03  4891.8 1072.48
  4907.3 1063.96  4944.1 1032.52  4973.7 1025.51  5014.7  1024.7  5017.4  1024.2
  5020.7  1024.7  5024.5  1024.9    5039 1025.01  5066.2 1033.09  5155.3 1041.31
  5373.9 1046.21  5446.1 1057.47  5535.5 1064.48  6029.8 1070.68  6275.9 1081.51
#Mann= 12 ,-1 , 0
  3927.7     .16       0  3978.4      .1       0  4264.7     .05       0
  4284.4      .1       0  4524.7     .05       0  4606.4      .1       0
  4792.8     .05       0  4802.8      .1       0  4973.7     .16       0
  5014.7     .07       0  5020.7     .16       0  5024.5      .1       0
Bank Sta=4944.1,5066.2
XS Rating Curve= 0 ,0
Exp/Cntr=0.3,0.1

Type RM Length L Ch R = 1 ,2105    ,635,635,635
BEGIN DESCRIPTION:
YEAGER CREEK 4.0
END DESCRIPTION:
XS GIS Cut Line= 4
      2941110.69     10055373.32      2941555.18     10055546.95
      2942430.18     10055331.67      2942812.14     10055526.12
#Sta/Elev= 30
  4168.1 1130.61  4337.5  1121.9  4459.4 1112.49    4520 1104.17  4584.2 1101.13
  4682.2 1098.13  4751.7 1094.03  4782.6  1090.5  4792.9 1087.28  4801.6 1080.81
  4806.8 1079.34  4843.2 1048.99  4848.3 1047.57  4854.6 1041.41  4875.2 1031.59
  4895.8 1026.97    4959 1023.84  5006.1 1019.63  5008.9 1019.13  5012.1 1019.63
  5029.7 1030.16  5055.9 1040.96  5144.1 1043.14  5180.5 1049.84    5222 1054.69
  5329.8 1062.92  5379.3 1064.62  5482.8 1068.12  5711.7 1069.97    5975 1081.02
#Mann= 7 ,-1 , 0
  4168.1      .1       0  4584.2     .05       0    4959      .1       0
  5006.1     .07       0  5012.1      .1       0  5329.8     .05       0
  5379.3      .1       0
Bank Sta=4875.2,5029.7
XS Rating Curve= 0 ,0
Exp/Cntr=0.3,0.1

Type RM Length L Ch R = 1 ,1470    ,725,725,725
BEGIN DESCRIPTION:
YEAGER CREEK 3.0
END DESCRIPTION:
XS GIS Cut Line= 4
       2941194.1     10055595.58      2941770.46     10055991.39
      2942506.57       10056165.      2942978.76     10056713.58
#Sta/Elev= 30
  3990.5  1120.8  4151.2 1110.07  4178.3 1102.94  4556.5 1092.85  4689.7 1087.19
  4770.1 1076.74  4821.2 1064.46  4831.5 1059.52  4849.6 1038.54  4854.8  1042.6
  4862.3 1033.95  4872.6 1029.48  4881.8  1027.6  5006.1 1019.83  5078.1 1029.97
  5088.3  1031.5  5108.7 1021.46  5116.2 1019.15  5118.9 1018.65  5122.2 1019.15
  5156.2 1030.21  5216.9  1031.9  5223.4  1031.9  5417.9 1033.22  5503.1 1046.55
  5549.7 1049.38  5638.5 1059.03  5879.4 1068.32    6021 1082.42  6169.8 1085.76
#Mann= 11 ,-1 , 0
  3990.5      .1       0  4556.5     .05       0  4881.8      .1       0
  5108.7     .16       0  5116.2     .07       0  5122.2     .16       0
  5216.9      .1       0  5223.4     .05       0  5417.9      .1       0
  5549.7     .05       0  5638.5      .1       0
#XS Ineff= 1 ,-1
 5087.12 5398.47 1031.25
Permanent Ineff=
       T
Bank Sta=4872.6,5078.1
XS Rating Curve= 0 ,0
Exp/Cntr=0.3,0.1

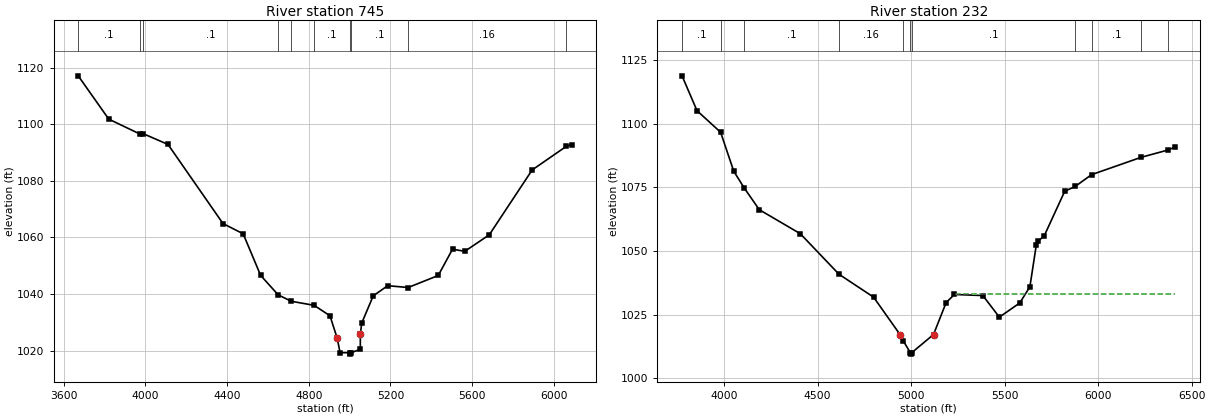
Type RM Length L Ch R = 1 ,745     ,513,513,513
BEGIN DESCRIPTION:
YEAGER CREEK 2.0
END DESCRIPTION:
XS GIS Cut Line= 4
      2941082.98     10055748.36      2941798.23     10056560.84
      2942221.84     10056963.61      2942971.83      10056977.5
#Sta/Elev= 30
  3670.6 1117.14  3820.2 1101.83  3971.9  1096.6  3989.4 1096.67  4110.5 1092.88
  4379.9  1064.9  4478.6  1061.3    4564 1046.61  4650.2  1039.7  4714.3 1037.44
  4826.2    1036  4903.9 1032.31  4939.2 1024.37  4953.3 1019.26  4999.7 1019.25
  5002.4 1018.75  5005.7 1019.25  5052.4  1020.4 5052.84 1025.83  5059.3 1029.71
  5115.9 1039.37  5186.7 1042.94  5286.8  1042.3  5434.2 1046.55  5504.2 1055.85
  5564.2 1055.09  5684.3 1060.94  5894.3 1083.86  6062.4 1092.25  6087.7 1092.85
#Mann= 10 ,-1 , 0
  3670.6      .1       0  3971.9     .16       0  3989.4      .1       0
  4650.2     .05       0  4714.3     .16       0  4826.2      .1       0
  4999.7     .07       0  5005.7      .1       0  5286.8     .16       0
  6062.4      .1       0
Bank Sta=4939.2,5052.84
XS Rating Curve= 0 ,0
Exp/Cntr=0.3,0.1

Type RM Length L Ch R = 1 ,232     ,0,0,0
BEGIN DESCRIPTION:
YEAGER CREEK 1.0
END DESCRIPTION:
XS GIS Cut Line= 4
      2940930.19     10055796.97      2941291.29      10056602.5
      2941617.68     10057019.17       2942742.7     10057505.29
#Sta/Elev= 30
  3775.9 1118.73  3855.9 1105.05  3982.1 1096.59  4052.3  1081.3  4108.6 1074.69
  4188.8 1066.21    4408 1056.79  4614.9 1040.88    4800 1031.88    4942 1017.13
  4957.7 1014.84  4996.8 1010.04  4999.5 1009.54  5002.8 1010.04  5120.1 1017.24
  5187.7 1029.78  5232.1 1032.95    5384 1032.52    5472 1024.05    5581  1029.6
  5635.3 1035.96  5669.7 1052.44    5679 1053.89  5711.3 1055.85  5821.6 1073.45
  5877.1 1075.31  5964.8 1079.95    6230 1086.76  6371.8 1089.59  6413.5 1090.85
#Mann= 11 ,-1 , 0
  3775.9      .1       0  3982.1     .16       0  4108.6      .1       0
  4614.9     .16       0  4957.7      .1       0  4996.8     .07       0
  5002.8      .1       0  5877.1     .16       0  5964.8      .1       0
    6230     .05       0  6371.8      .1       0
#XS Ineff= 2 , 0
                         5240.34         1033.19
Permanent Ineff=
       T       T
Bank Sta=4942,5120.1
XS Rating Curve= 0 ,0
Exp/Cntr=0.3,0.1

Chan Stop Cuts=-1
Use User Specified Reach Order=0
Composite Channel Slope=5